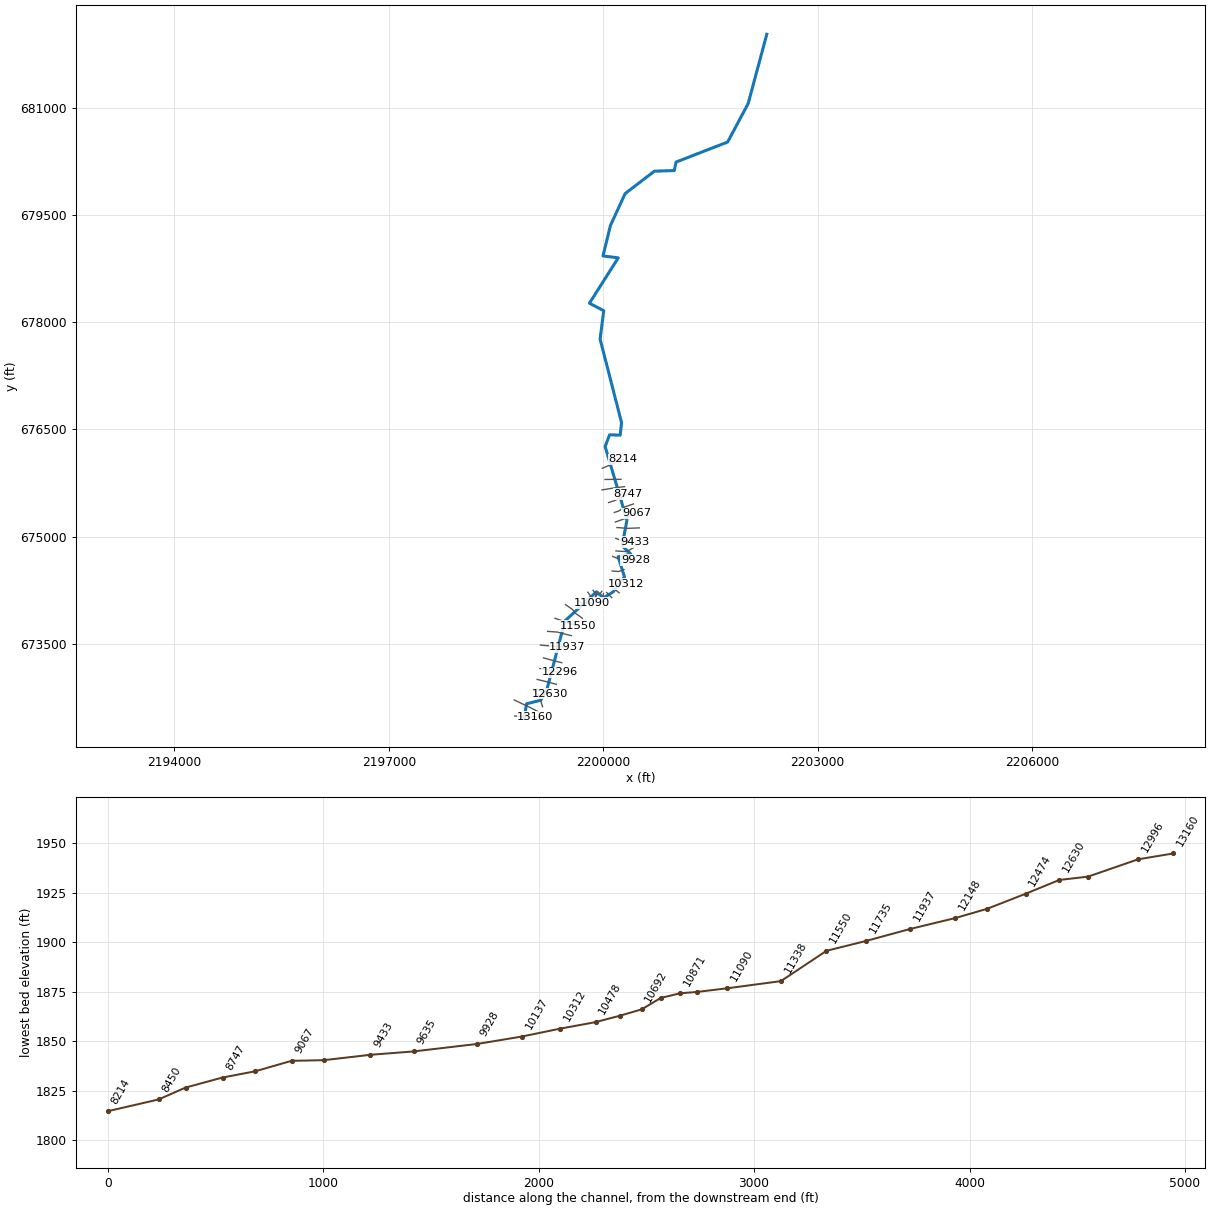
--- RFTENMILCK.prj (project) ---

Proj Title=RFTENMILCK
Current Plan=p01
Default Exp/Contr=0,0
English Units
Geom File=g01
Flow File=f01
Plan File=p01
BEGIN DESCRIPTION:
-------- MODELED AS PART OF WVEMD CTP PROGRAM, 2023----------
Stream Name: Right Fork Tenmile Creek
Flood Zone:  AFH
Upshur County, WV
HEC-RAS Version: RAS 6.3
Vertical Datum: NAVD88
Projection: NAD 1983 StatePlane West Virginia S FIPS 4702 (US Feet)
Terrain: 1-meter LIDAR (FEMA Region III 3DEP collected 2016-2018)
Land Use: 2019 NLCD
Hydrologic Method:
WV SIR2010-5033 regression equations
Additional Model Notes:
None
END DESCRIPTION:
DSS Export Rating Curves= 0
DSS Export Rating Curve Sorted= 0
DSS Export Volume Flow Curves= 0
DXF OffsetX= 0
DXF OffsetY= 0
DXF ScaleX= 0
DXF ScaleY= 0

--- RFTENMILCK.p01 (plan) ---

Plan Title=Floodplain
Program Version=4.00
Geom File=g01
Flow File=f01
K Sum by GR=0
Std Step Tol=0.01
Critical Tol=0.01
Num of Std Step Trials=20
Max Error Tol=0.3
Flow Tol Ratio=0.001
Split Flow NTrial=30
Split Flow Tol=0.02
Split Flow Ratio=0.02
Log Output Level=0
Friction Slope Method=1
Unsteady Friction Slope Method=2
Unsteady Bridges Friction Slope Method=1
Global Log Level=0
CheckData=False
Run HTab=0
Run UNet=0
Run PostProcess=0
UNET Theta=0
UNET Theta Warmup=0
UNET ZTol=0
UNET ZSATol=0
UNET MxIter=0
UNET MaxInSteps=0
UNET DtIC=0
UNET DtMin=0
UNET MaxCRTS=0
UNET WFStab=0
UNET SFStab=0
UNET WFX=0
UNET SFX=0
UNET DSS MLevel=0
UNET DZMax Abort=0
UNET Convert EG Bridges=0
UNET Use Existing IB Tables=0
UNET Froude Limit=0
UNET Froude Power=0
Write IC File=0
Echo Input=False
Echo Output=False
Write Detailed=0

--- RFTENMILCK.f01 (steady flow) ---

Flow Title=Flows
Program Version=6.30
Number of Profiles= 1
Profile Names=01pct
River Rch & RM=RFTENMILCK,Main            ,13160
     346
River Rch & RM=RFTENMILCK,Main            ,10478
     739
River Rch & RM=RFTENMILCK,Main            ,6843
     839
River Rch & RM=RFTENMILCK,Main            ,1519
     985
Boundary for River Rch & Prof#=RFTENMILCK,Main            , 1
Up Type= 0
Dn Type= 3
Dn Slope=0.01652
DSS Import GetInterval= 0
DSS Import GetPeak= 0
DSS Import FillOption= 0

--- RFTENMILCK.g01 (geometry) ---

Geom Title=Geometry
Program Version=6.30

River Reach=RFTENMILCK      ,Main
Reach XY= 30
     2198896.317      672469.513     2198925.935      672660.213
     2199127.222      672711.665     2199214.445      672872.546
     2199463.722       673819.92     2199905.245      674228.477
     2200003.714      674142.599     2200141.215      674229.106
     2200297.117      674435.917     2200207.977      674718.761
     2200387.946      674754.446     2200262.749      674869.198
     2200331.486      675229.134      2200026.12      676259.782
     2200088.733      676424.956     2200237.366      676419.204
     2200255.366      676597.084     2199955.924      677763.574
     2200006.518      678161.084     2199806.461      678265.419
     2200209.666      678900.188      2199996.13      678927.345
     2200100.609        679353.5     2200306.017      679799.515
     2200715.403      680113.065     2200993.182      680121.793
     2201019.023      680240.808     2201739.984      680520.677
     2202027.522      681059.466     2202288.131      682029.046

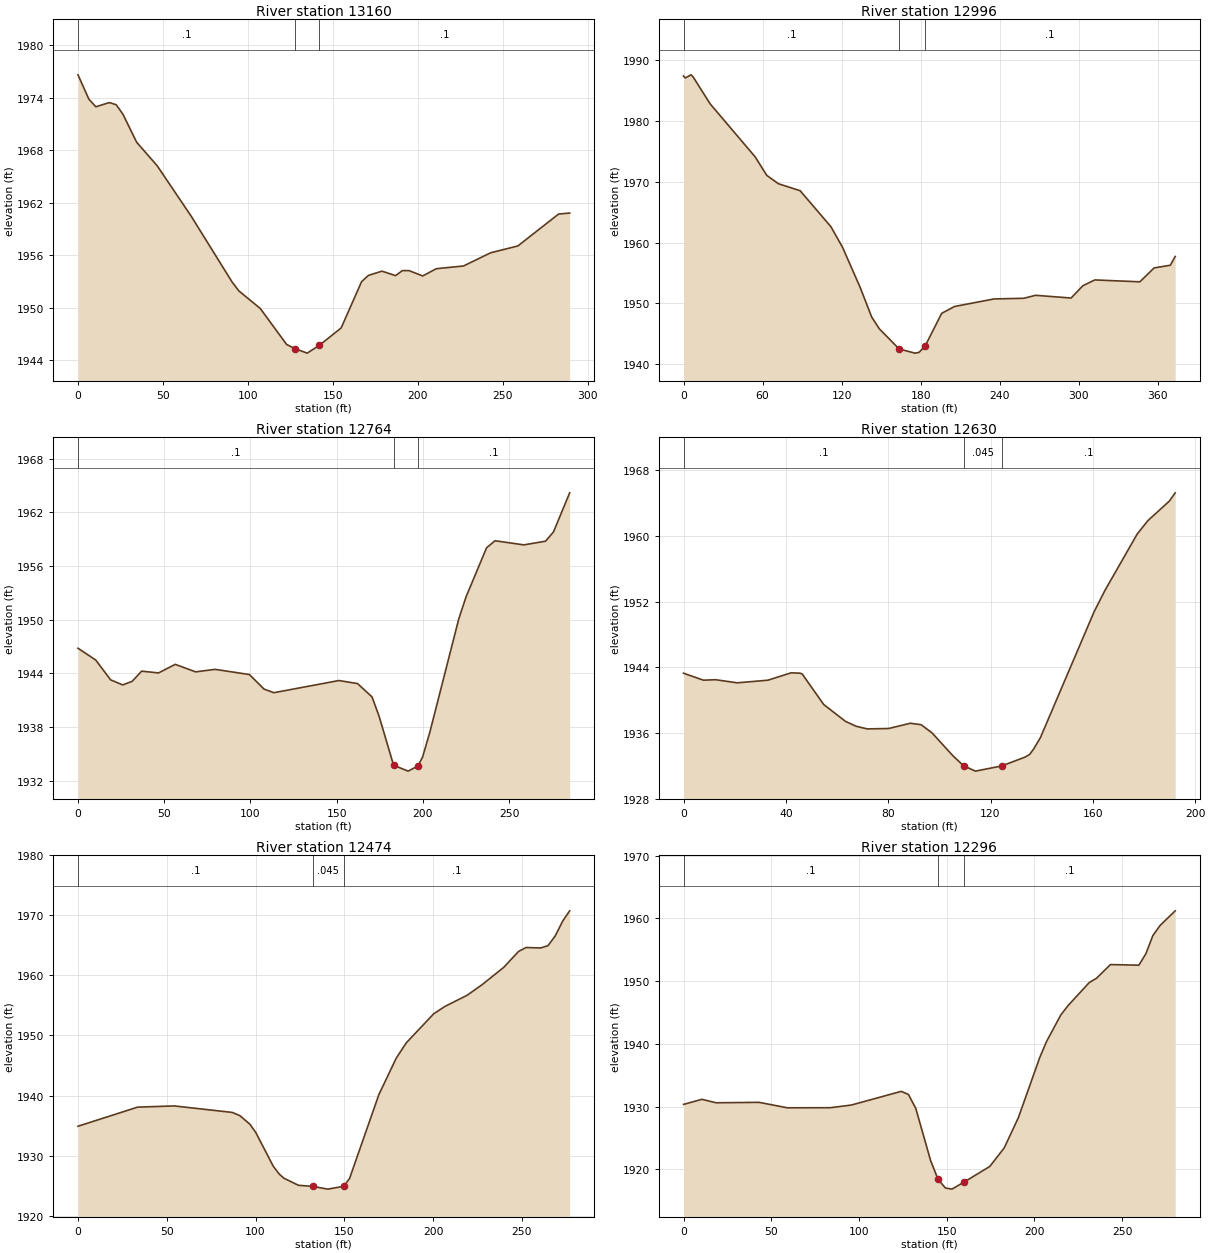
Type RM Length L Ch R = 1 ,13160   ,170,164.3,158.6
XS GIS Cut Line= 3
2198761.74944945672490.253806542     2198896.377      672479.494
2199050.71009895672477.913849979
#Sta/Elev= 30
       0  1976.6     6.4 1973.82    10.5 1972.95    18.5 1973.43    22.5 1973.18
    26.5 1972.08    34.5  1968.9    46.6 1966.21    66.6 1960.45    90.7 1952.92
    94.7  1951.9   107.3 1949.89   122.8 1945.78   127.61945.309   134.9 1944.79
   142.11945.685   154.9 1947.67   166.9 1952.95   170.9 1953.67   178.9 1954.16
   186.9 1953.65   190.9 1954.22   194.9 1954.22   202.9 1953.61   210.9 1954.44
   226.9 1954.75   242.9 1956.26   258.9 1957.04   282.9 1960.69   289.4  1960.8
#Mann= 3, -1 ,  0
       0     0.1       0   127.6   0.045       0   142.1     0.1       0
Bank Sta=127.6,142.1
XS Rating Curve= 0 ,0
Exp/Cntr=0.3,0.1

Type RM Length L Ch R = 1 ,12996   ,245,231.8,220.6
XS GIS Cut Line= 3
2198755.03132877672713.8168277872198967.50919568672613.480057299
2199090.47092422672550.523652286
#Sta/Elev= 30
       0 1987.43     1.3  1987.1     5.7 1987.62     7.3 1987.27    20.2 1982.84
    54.3 1974.13    63.2 1971.06      72 1969.69    88.5 1968.54   111.9  1962.6
   120.7 1959.21     134 1952.64   142.8 1947.74   148.6  1945.8   163.6 1942.49
   175.6  1941.8   178.6 1941.91   183.21942.914   195.9 1948.35   205.7 1949.48
   235.6 1950.72   258.2 1950.83   267.2 1951.32   294.1 1950.87   303.1 1952.91
   312.1 1953.85   346.3 1953.54   357.1 1955.83   369.4 1956.27   373.1 1957.71
#Mann= 3, -1 ,  0
       0     0.1       0   163.6   0.045       0   183.2     0.1       0
Bank Sta=163.6,183.2
XS Rating Curve= 0 ,0
Exp/Cntr(USF)=0,0
Exp/Cntr=0.3,0.1

Type RM Length L Ch R = 1 ,12764   ,120.5,133.7,143.1
XS GIS Cut Line= 3
 2199016.1036708672865.1089385832199108.17741313672754.443382897
2199150.67298652672619.874067183
#Sta/Elev= 30
       0 1946.81    10.3 1945.49    18.9 1943.28    25.9 1942.71    31.4 1943.11
    36.9 1944.25    46.7 1944.05    56.4 1945.01    68.2 1944.17    79.5 1944.45
    99.4 1943.87   107.9 1942.24   113.6 1941.84   151.3  1943.2   162.1 1942.86
   170.5 1941.37   174.6  1939.2     183 1933.73   191.4 1933.07   197.1 1933.64
   199.8 1934.64     204 1937.41   220.8  1950.1     225 1952.55   236.9 1958.04
   241.8 1958.83   258.5 1958.37   271.1 1958.78   275.7 1959.81   285.1 1964.19
#Mann= 3, -1 ,  0
       0     0.1       0     183   0.045       0   197.1     0.1       0
Bank Sta=183,197.1
XS Rating Curve= 0 ,0
Exp/Cntr(USF)=0,0
Exp/Cntr=0.3,0.1

Type RM Length L Ch R = 1 ,12630   ,154.4,156.2,156.9
XS GIS Cut Line= 3
2199068.34475934672863.3142053262199204.31859714672816.264434462
2199250.42737258672801.679005495
#Sta/Elev= 30
       0  1943.3     7.8 1942.45    12.5 1942.51      21 1942.13      33 1942.45
    42.1 1943.35    45.6  1943.3    46.4  1943.2    54.8 1939.49    63.3 1937.44
    67.5 1936.84    71.8 1936.52    80.2 1936.57    88.7 1937.21    92.9 1937.03
    97.2 1936.02   105.3 1933.25   109.51932.027   114.1 1931.38   124.41932.012
   133.6  1933.1   135.3 1933.42   136.8 1934.04   139.5 1935.45   160.5 1950.78
   164.7 1953.36   177.3 1960.22   181.5 1961.87   189.9 1964.25   192.2 1965.26
#Mann= 3, -1 ,  0
       0     0.1       0   109.5   0.045       0   124.4     0.1       0
Bank Sta=109.5,124.4
XS Rating Curve= 0 ,0
Exp/Cntr(USF)=0,0
Exp/Cntr=0.3,0.1

Type RM Length L Ch R = 1 ,12474   ,178.4,178.4,177
XS GIS Cut Line= 3
2199075.59167024673001.7397322692199242.87974442672960.498575092
2199343.94962257672933.198090764
#Sta/Elev= 30
       0 1934.89    33.6 1938.07    54.2 1938.27    86.9 1937.19    91.2 1936.65
    96.8 1935.24   100.1 1933.88     110 1928.24   113.3 1926.95     116 1926.24
   124.2 1925.06   132.4 1924.87   140.7 1924.42   149.7 1924.89     153  1926.2
   169.5 1940.15   179.3 1946.23     185 1948.79   200.4 1953.61   206.8 1954.85
   219.2 1956.69   227.5 1958.42   239.9 1961.35   248.2 1963.99   252.4 1964.64
   260.6 1964.57   264.8 1964.95   268.9 1966.59   273.1 1969.06     277 1970.75
#Mann= 3, -1 ,  0
       0     0.1       0   132.4   0.045       0   149.7     0.1       0
Bank Sta=132.4,149.7
XS Rating Curve= 0 ,0
Exp/Cntr(USF)=0,0
Exp/Cntr=0.3,0.1

Type RM Length L Ch R = 1 ,12296   ,147.3,147.9,147.9
XS GIS Cut Line= 4
2199113.80063053673154.6021331972199239.00852556673133.303883012
2199288.05904114673117.1688449932199388.74167838673102.970011536
#Sta/Elev= 30
       0 1930.34    10.5 1931.15    18.6  1930.6      43 1930.67    59.2  1929.8
    83.6 1929.81    95.7 1930.24   124.1 1932.42   128.2 1931.93   132.4 1929.71
   140.9 1921.35   145.1 1918.39   149.3 1917.01     153 1916.83   160.11917.977
   174.6 1920.45   182.8 1923.39   190.9 1928.23     203 1937.76     207  1940.4
   215.1 1944.61   219.2 1946.09   231.3 1949.77   235.4 1950.45   243.4 1952.64
   259.6 1952.54   263.6 1954.38   267.6 1957.28   271.7 1958.88   280.3 1961.21
#Mann= 3, -1 ,  0
       0     0.1       0   145.1   0.045       0   160.1     0.1       0
Bank Sta=145.1,160.1
XS Rating Curve= 0 ,0
Exp/Cntr(USF)=0,0
Exp/Cntr=0.3,0.1

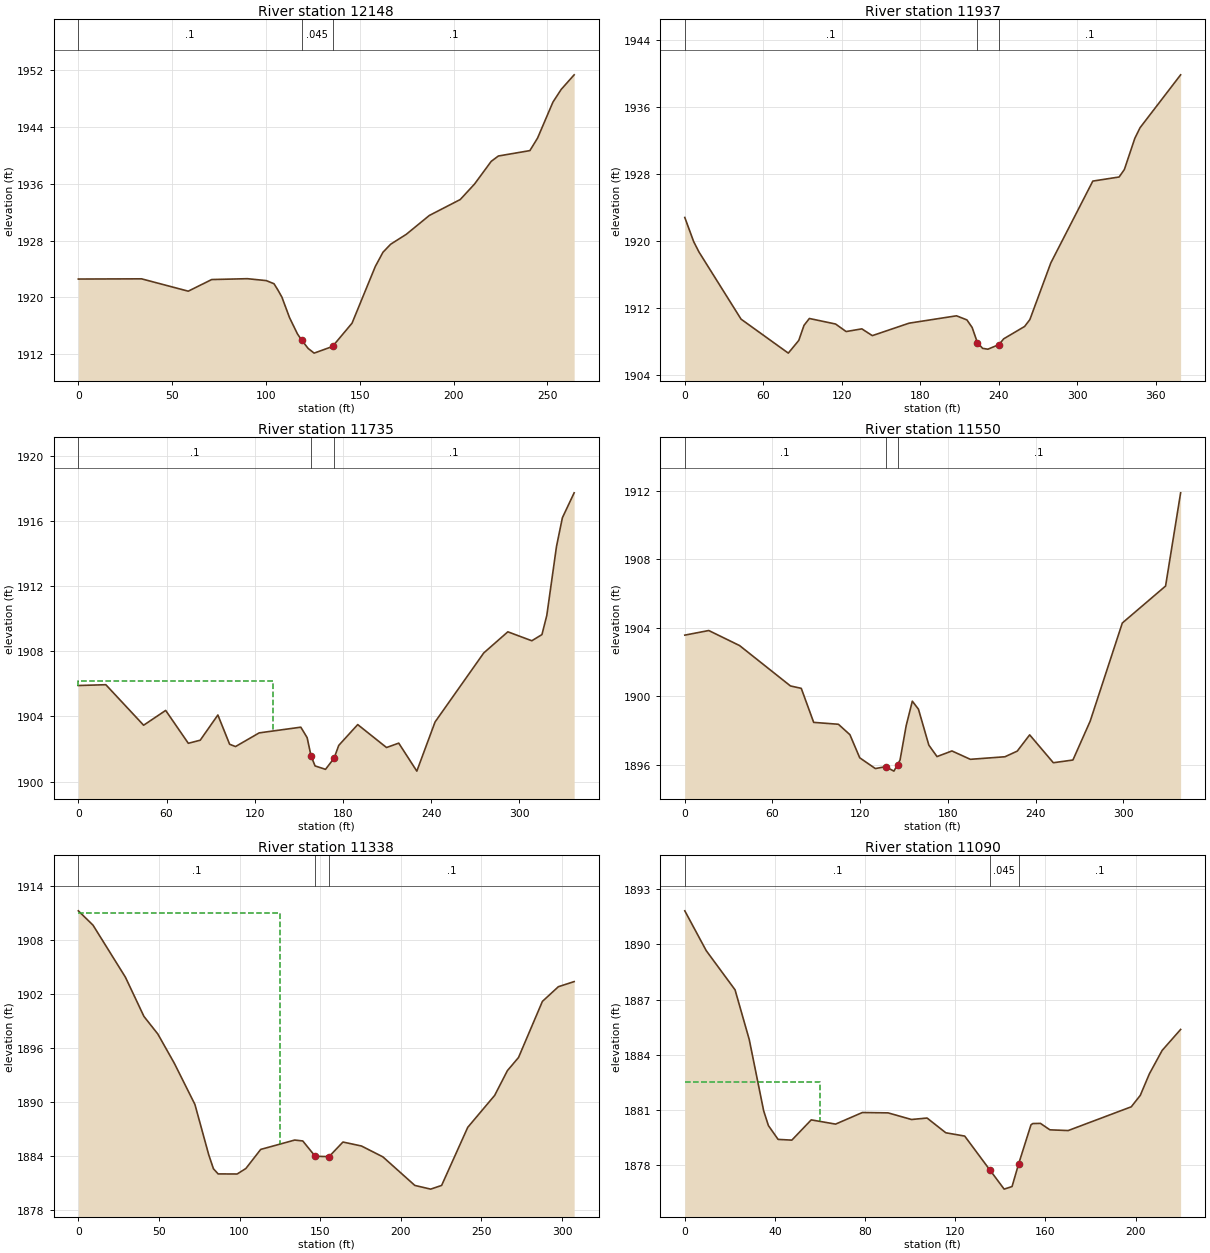
Type RM Length L Ch R = 1 ,12148   ,207.2,210.5,212.8
XS GIS Cut Line= 3
 2199163.7729656673303.9215443892199308.62975137673263.046114741
 2199419.0651227673235.795828309
#Sta/Elev= 30
       0  1922.6    33.7 1922.63    58.6 1920.89    71.1 1922.53    90.1 1922.65
   100.2 1922.38   104.3 1921.94   106.3 1921.09   108.5 1920.06   112.6 1917.15
   116.8 1914.87     1191914.017   122.5 1912.82   125.7 1912.16   135.5  1913.1
   145.9 1916.38   158.3 1924.37   162.4 1926.38   166.5 1927.51   174.8  1928.9
   187.1 1931.56   203.6 1933.81   211.2 1935.99   220.1 1939.19   223.9 1939.94
   240.7  1940.7   244.8 1942.47     253 1947.54   257.4 1949.33   264.3 1951.38
#Mann= 3, -1 ,  0
       0     0.1       0     119   0.045       0   135.5     0.1       0
Bank Sta=119,135.5
XS Rating Curve= 0 ,0
Exp/Cntr(USF)=0,0
Exp/Cntr=0.3,0.1

Type RM Length L Ch R = 1 ,11937   ,204.4,202.2,198.6
XS GIS Cut Line= 4
2199121.36178343673482.0392409152199334.10524768673463.713024894
 2199436.0946238673457.3386888862199499.04119188 673451.76114488
#Sta/Elev= 30
       0 1922.83     6.8 1919.94    10.9 1918.69      43 1910.68    79.1 1906.62
    87.1 1908.14    91.1 1909.94    95.2 1910.76   115.2  1910.1   123.3  1909.2
   135.3 1909.52   143.3 1908.71   171.4  1910.2   207.6 1911.08   215.6 1910.59
   219.6 1909.68   223.6 1907.88   227.6 1907.19   231.6 1907.09     2401907.635
   243.7 1908.33   259.7 1909.81   263.7 1910.63   279.7  1917.4   311.8 1927.18
   331.9 1927.67   335.9 1928.56   343.9 1932.29   347.9 1933.56   378.9 1939.88
#Mann= 3, -1 ,  0
       0     0.1       0   223.6   0.045       0     240     0.1       0
Bank Sta=223.6,240
XS Rating Curve= 0 ,0
Exp/Cntr(USF)=0,0
Exp/Cntr=0.3,0.1

Type RM Length L Ch R = 1 ,11735   ,185.2,185.2,183.2
XS GIS Cut Line= 4
 2199221.5201447673673.9829350122199361.62390683673664.050205607
2199415.46975571673648.3669486532199551.91409121673614.386558584
#Sta/Elev= 30
       0  1905.9    18.7 1905.95    44.4 1903.46    59.4 1904.37    74.8 1902.35
    82.9 1902.54    94.9 1904.09   102.9 1902.29   106.9 1902.15     123 1902.99
   151.3 1903.34   155.6  1902.7   158.31901.561     161 1900.96   168.1 1900.75
   173.9 1901.43   177.1 1902.22     190  1903.5   209.6 1902.09   217.9 1902.36
   230.2 1900.64   242.6 1903.66   275.7  1907.9   292.1  1909.2   308.4 1908.65
   315.3 1909.03   318.6 1910.21   325.2 1914.45   329.2 1916.21   337.2 1917.74
#Mann= 3, -1 ,  0
       0     0.1       0   158.3   0.045       0   173.9     0.1       0
#XS Ineff= 2 , 0
        132.4932 1906.16
Permanent Ineff=
       T       F
Bank Sta=158.3,173.9
XS Rating Curve= 0 ,0
Exp/Cntr(USF)=0,0
Exp/Cntr=0.3,0.1

Type RM Length L Ch R = 1 ,11550   ,215.2,211.6,205.2
XS GIS Cut Line= 3
 2199324.6155478673857.272611112 2199482.2032991673804.153144382
2199645.98832151673748.377704317
#Sta/Elev= 30
       0 1903.57    16.4 1903.84    37.5 1902.96    72.3  1900.6    79.7 1900.46
    88.2 1898.47   105.1 1898.36     113 1897.75   119.7  1896.4   130.4 1895.77
   137.4 1895.88   143.1 1895.62   145.6    1896   147.3 1896.27   151.5 1898.28
   155.7 1899.71   159.9 1899.24     167 1897.14   172.6 1896.47   182.8  1896.8
   195.4 1896.31   219.1 1896.46   227.5 1896.79     236 1897.74   252.2 1896.11
   265.6 1896.27   277.4 1898.54   299.4 1904.28     329 1906.44   339.3 1911.89
#Mann= 3, -1 ,  0
       0     0.1       0   137.4   0.045       0   145.6     0.1       0
Bank Sta=137.4,145.6
XS Rating Curve= 0 ,0
Exp/Cntr(USF)=0,0
Exp/Cntr=0.3,0.1

Type RM Length L Ch R = 1 ,11338   ,229.5,248.2,259.3
XS GIS Cut Line= 4
2199471.39414027674049.0576231482199571.07281958673979.497681465
2199605.49423403673931.4511238092199708.04136455 673856.87139252
#Sta/Elev= 30
       0 1911.23     9.1 1909.64    29.2 1903.86    40.7  1899.5    49.3 1897.55
    59.5 1894.31    72.3 1889.73    80.9 1884.12    83.8 1882.58    86.7 1882.01
    98.5    1882   103.9 1882.61   113.1 1884.73   134.2 1885.77   139.2 1885.67
   146.9 1883.97   155.5 1883.93   164.1 1885.55   175.6 1885.11   188.9  1883.9
   208.7 1880.73   218.5 1880.32   225.3 1880.73   241.5 1887.18   258.2 1890.73
   266.1 1893.48     273 1894.94   287.8 1901.17   297.7  1902.8   307.5 1903.37
#Mann= 3, -1 ,  0
       0     0.1       0   146.9   0.045       0   155.5     0.1       0
#XS Ineff= 2 , 0
        125.3229 1910.97
Permanent Ineff=
       T       F
Bank Sta=146.9,155.5
XS Rating Curve= 0 ,0
Exp/Cntr(USF)=0,0
Exp/Cntr=0.3,0.1

Type RM Length L Ch R = 1 ,11090   ,158.1,142.7,127
XS GIS Cut Line= 5
2199639.29673411674115.135885496 2199717.6346026674052.042142768
2199777.34076182674071.0972999682199825.89137322674071.489719109
2199834.06623659674071.597211194
#Sta/Elev= 30
       0 1891.82     9.5 1889.66    22.3 1887.53    28.6 1884.83      35 1880.96
    37.1 1880.16    41.4 1879.41    47.5 1879.37    56.1 1880.47    66.9 1880.24
    78.8 1880.87    90.2 1880.85   100.6 1880.49   107.5 1880.57   115.8 1879.77
   124.2 1879.59   135.3 1877.76   141.7 1876.71   145.2 1876.85   148.1 1878.07
   153.6  1880.2   154.4 1880.27   157.8 1880.28     162 1879.93   170.1 1879.89
   198.1 1881.18   202.1  1881.8   206.1 1882.96   211.8 1884.24     220 1885.38
#Mann= 3, -1 ,  0
       0     0.1       0   135.3   0.045       0   148.1     0.1       0
#XS Ineff= 2 , 0
           59.86 1882.51
Permanent Ineff=
       T       F
Bank Sta=135.3,148.1
XS Rating Curve= 0 ,0
Exp/Cntr(USF)=0,0
Exp/Cntr=0.3,0.1

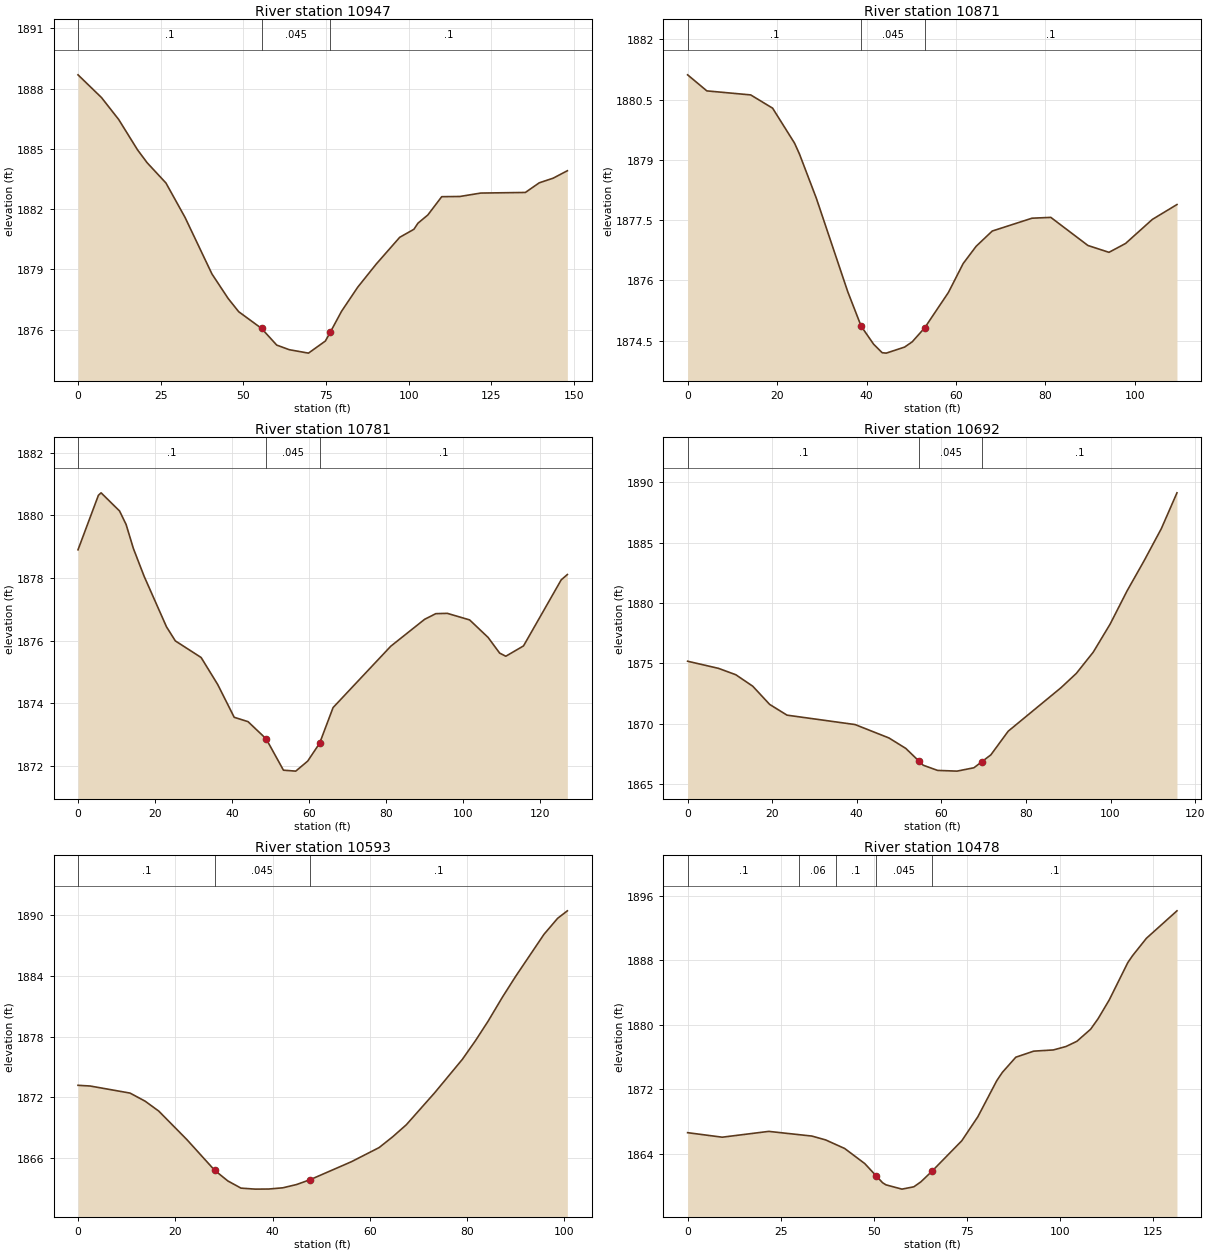
Type RM Length L Ch R = 1 ,10947   ,76,76.1,75.9
XS GIS Cut Line= 3
2199784.08054729674222.2007684332199833.47151475674152.436026893
2199853.22790174674093.166865939
#Sta/Elev= 30
       0 1888.68     7.1 1887.55    12.3 1886.46      18 1884.95    20.9 1884.31
    26.6  1883.3    32.4 1881.58    40.5 1878.78    45.4 1877.56    48.6  1876.9
    55.5 1876.07    60.1 1875.24    63.9 1875.01    69.7 1874.84    74.8 1875.44
    76.3 1875.88    79.7 1876.92    84.6 1878.12    90.2 1879.27    97.3  1880.6
   101.6    1881   102.8  1881.3   105.8 1881.71     110 1882.62   115.5 1882.63
   121.8  1882.8   135.3 1882.83   139.5 1883.31   143.7 1883.54     148 1883.91
#Mann= 3, -1 ,  0
       0     0.1       0    55.5   0.045       0    76.3     0.1       0
Bank Sta=55.5,76.3
XS Rating Curve= 0 ,0
Exp/Cntr(USF)=0,0
Exp/Cntr=0.3,0.1

Type RM Length L Ch R = 1 ,10871   ,112.4,90.4,68.4
XS GIS Cut Line= 3
2199857.66640165674248.6454989542199899.20664435674190.336717923
2199888.32691179674154.122772767
#Sta/Elev= 26
       0 1881.12     4.3 1880.72    14.1 1880.62      19 1880.29    23.9 1879.42
      25 1879.15    28.8 1878.04    35.8 1875.72    38.8 1874.86    41.6 1874.41
    43.5  1874.2    44.4 1874.19    48.5 1874.34    50.2 1874.47      53 1874.82
    58.3  1875.7    61.6 1876.42    64.5 1876.85    68.1 1877.23      77 1877.55
    81.2 1877.57    89.5 1876.87    94.2  1876.7    97.9 1876.92   103.9 1877.52
   109.4 1877.89
#Mann= 3, -1 ,  0
       0     0.1       0    38.8   0.045       0      53     0.1       0
Bank Sta=38.8,53
XS Rating Curve= 0 ,0
Exp/Cntr(USF)=0,0
Exp/Cntr=0.3,0.1

Type RM Length L Ch R = 1 ,10781   ,73.9,88.8,101.1
XS GIS Cut Line= 4
2199979.17542257674234.1361400562199962.78379524674209.965435354
2199914.44238584674191.351214492 2199891.3829779674151.344530848
#Sta/Elev= 30
       0  1878.9     5.3 1880.64       6 1880.72    10.8 1880.14    12.5 1879.71
    14.4 1878.94    17.2 1878.05      23 1876.44    25.3 1875.99      32 1875.46
    36.3  1874.6    40.6 1873.55    44.2 1873.41    48.91872.862    53.4 1871.86
    56.6 1871.83    59.7 1872.15    62.8 1872.72    66.3 1873.86    81.3 1875.82
    90.1 1876.68      93 1876.86      96 1876.87   101.8 1876.66   106.6  1876.1
   109.6  1875.6   111.2  1875.5   115.8 1875.83   125.6 1877.94   127.2 1878.11
#Mann= 3, -1 ,  0
       0     0.1       0    48.9   0.045       0    62.8     0.1       0
Bank Sta=48.9,62.8
XS Rating Curve= 0 ,0
Exp/Cntr(USF)=0,0
Exp/Cntr=0.3,0.1

Type RM Length L Ch R = 1 ,10692   ,86.9,98.7,109.7
XS GIS Cut Line= 3
2200002.40251589674204.4628318772199997.00161359674159.905387969
2199989.80041054674089.468620577
#Sta/Elev= 25
       0 1875.17     7.3 1874.58    11.4 1874.05    15.4  1873.1    19.4 1871.59
    23.5  1870.7    39.6 1869.92    47.6 1868.81    51.6 1867.94    54.71866.889
    55.7 1866.55    59.1 1866.12    63.7 1866.06    67.7 1866.34    69.61866.848
    71.7 1867.41    75.8 1869.37    88.3 1872.98    91.9 1874.16    95.9 1875.92
    99.9 1878.25   103.9    1881   107.9 1883.48     112 1886.16   115.7 1889.13
#Mann= 3, -1 ,  0
       0     0.1       0    54.7   0.045       0    69.6     0.1       0
Bank Sta=54.7,69.6
XS Rating Curve= 0 ,0
Exp/Cntr(USF)=0,0
Exp/Cntr=0.3,0.1

Type RM Length L Ch R = 1 ,10593   ,113.8,115.3,116
XS GIS Cut Line= 2
2200048.63249573674217.1296599722200119.39431742674145.617712958
#Sta/Elev= 27
       0 1873.19     2.5 1873.12    10.7 1872.42    13.8 1871.62    16.6 1870.64
    22.4 1867.81    28.1 1864.78    30.8 1863.73    33.5 1863.02    36.4 1862.92
    39.2 1862.93    42.1 1863.05    44.9 1863.37    47.7 1863.85    56.2 1865.63
    61.9 1867.03    64.7  1868.1    67.5 1869.29    73.3 1872.44      79 1875.75
    81.7  1877.6    84.3 1879.53    87.3 1881.95      90 1883.99    95.8 1888.13
    98.6 1889.71   100.6 1890.45
#Mann= 3, -1 ,  0
       0     0.1       0    28.1   0.045       0    47.7     0.1       0
Bank Sta=28.1,47.7
XS Rating Curve= 0 ,0
Exp/Cntr(USF)=0,0
Exp/Cntr=0.3,0.1

Type RM Length L Ch R = 1 ,10478   ,165.5,165.8,164.9
XS GIS Cut Line= 3
2200119.08439164674294.950824583 2200190.4269002  674238.3570077
2200222.66822618674214.004516798
#Sta/Elev= 30
       0 1866.61     9.3 1866.05    21.8 1866.77    33.4 1866.19    37.1 1865.71
    42.2 1864.65    47.6 1862.78    50.61861.292    52.4  1860.4    53.3 1860.14
    57.6 1859.61    60.8  1859.9    62.7 1860.52    65.61861.799    73.7 1865.62
      78 1868.59    83.1 1873.08    84.6  1874.1    88.2 1875.97      93 1876.72
    98.3 1876.87   101.7  1877.3   104.6 1877.94   108.3 1879.44   110.3 1880.74
   113.3 1883.07   118.3 1887.71   119.6 1888.58   123.3 1890.72   131.5 1894.12
#Mann= 5, -1 ,  0
       0     0.1       0      30    0.06       0      40     0.1       0
    50.6   0.045       0    65.6     0.1       0
Bank Sta=50.6,65.6
XS Rating Curve= 0 ,0
Exp/Cntr(USF)=0,0
Exp/Cntr=0.3,0.1

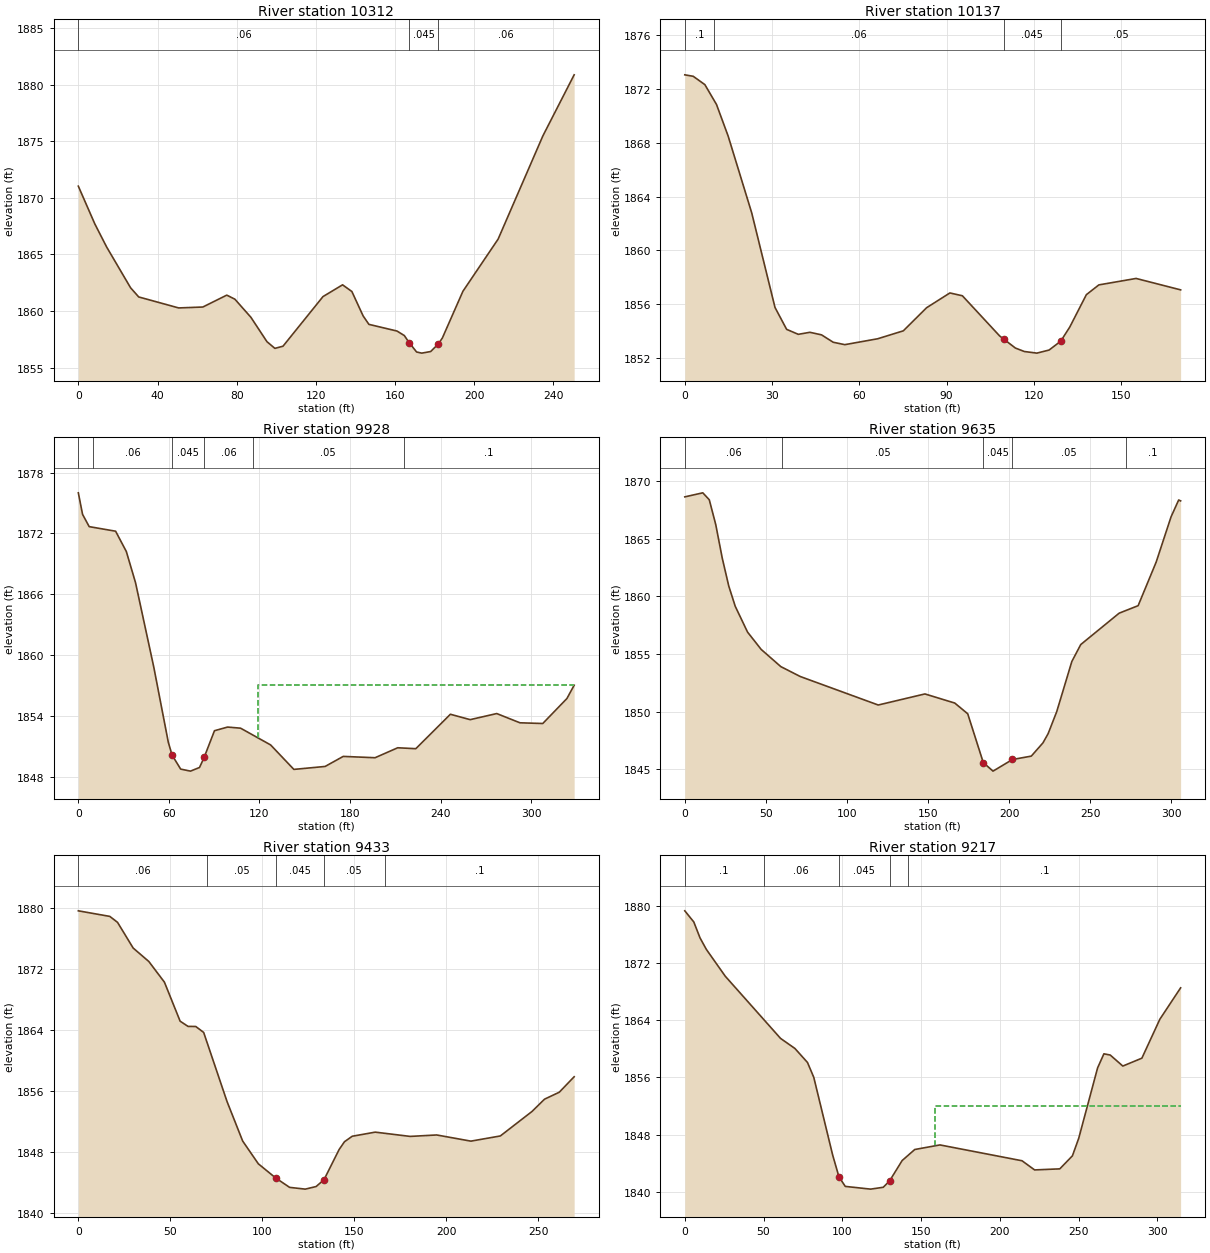
Type RM Length L Ch R = 1 ,10312   ,159.7,175.6,184.8
XS GIS Cut Line= 4
2200098.05385143674393.8331852752200228.01002353 674414.41275505
2200283.65108255674367.9181714832200318.33146866674337.048816819
#Sta/Elev= 30
       0 1871.03     8.3 1867.71    14.3 1865.66    26.4 1862.06    30.5 1861.25
    50.7 1860.28    62.9 1860.36      75 1861.41    79.1 1861.05    87.2 1859.45
    95.3  1857.3    99.3 1856.71   103.4  1856.9   123.6 1861.28   133.5 1862.32
   138.2 1861.73   143.9 1859.57   146.8 1858.83     161 1858.24   164.7 1857.84
   167.21857.201   170.9 1856.39   173.5 1856.29     178 1856.43   181.91857.102
   183.9 1857.62   194.3 1861.75   212.1 1866.36   234.7 1875.47   250.5 1880.86
#Mann= 3, -1 ,  0
       0    0.06       0   167.2   0.045       0   181.9    0.06       0
Bank Sta=167.2,181.9
XS Rating Curve= 0 ,0
Exp/Cntr(USF)=0,0
Exp/Cntr=0.3,0.1

Type RM Length L Ch R = 1 ,10137   ,220.1,208.6,196.1
XS GIS Cut Line= 3
2200125.27410568674518.4454981142200216.16720552674512.271627182
2200290.59664954674539.711053549
#Sta/Elev= 30
       0 1873.07     2.9 1872.96     6.9 1872.34    10.9 1870.86    14.9 1868.51
      23 1862.79      31 1855.75      35 1854.12      39 1853.75      43  1853.9
      47 1853.71      51 1853.16      55 1852.98    66.3 1853.42    75.1 1854.01
    83.1 1855.73    91.1 1856.83    95.4 1856.62   108.2 1853.63   109.7 1853.38
   113.6 1852.73   116.7 1852.47     121 1852.35   125.2 1852.58   129.2 1853.24
   132.3 1854.29     138  1856.7   142.3 1857.43   155.1 1857.91   170.4 1857.06
#Mann= 4, -1 ,  0
       0     0.1       0      10    0.06       0   109.7   0.045       0
   129.2    0.05       0
Bank Sta=109.7,129.2
XS Rating Curve= 0 ,0
Exp/Cntr(USF)=0,0
Exp/Cntr=0.3,0.1

Type RM Length L Ch R = 1 ,9928    ,285.5,292.9,308.5
XS GIS Cut Line= 3
2200129.56433331 674724.38768885 2200226.2777512674682.042895072
2200448.97999996674672.632940899
#Sta/Elev= 30
       0    1876     2.8 1873.88     7.2 1872.67    24.7 1872.22    31.8 1870.22
    37.9 1867.15      50 1858.83    59.6 1851.44    62.1 1850.17    67.8 1848.79
    74.3 1848.59    80.3 1848.95    83.4 1849.96    90.2 1852.57    98.9 1852.93
   107.5 1852.82   127.4 1851.17   142.8 1848.76   163.5 1849.05   175.5 1850.04
   196.6 1849.91   211.6 1850.89   223.6  1850.8   246.5 1854.19   259.6 1853.66
   277.2 1854.26   292.6 1853.35   307.7 1853.28   323.7 1855.74   328.5 1857.05
#Mann= 6, -1 ,  0
       0    0.05       0      10    0.06       0    62.1   0.045       0
    83.4    0.06       0  115.58    0.05       0  215.58     0.1       0
#XS Ineff= 2 , 0
                        118.7966         1857.05
Permanent Ineff=
       F       T
Bank Sta=62.1,83.4
XS Rating Curve= 0 ,0
Exp/Cntr(USF)=0,0
Exp/Cntr=0.3,0.1

Type RM Length L Ch R = 1 ,9635    ,216.1,201.9,181.4
XS GIS Cut Line= 3
2200177.13687941   674799.1445472200328.74169664674789.734592827
2200463.09493122674869.196428064
#Sta/Elev= 30
       0 1868.61    11.1 1868.96    15.1 1868.36    19.1  1866.2    23.1  1863.3
    27.1 1860.89    31.1 1859.13    38.7 1856.89    47.1 1855.39    59.2  1853.9
    71.2 1853.04   119.3 1850.57   148.1 1851.53   166.5 1850.74   174.5 1849.81
   184.11845.577   190.1 1844.84   202.11845.848   213.7 1846.14   220.9 1847.29
   224.1 1848.09   229.4    1850   238.7 1854.34   244.2 1855.81   267.9 1858.53
   279.6 1859.18   290.7 1862.95   299.9 1866.88   304.6 1868.34   305.8 1868.26
#Mann= 5, -1 ,  0
       0    0.06       0      60    0.05       0   184.1   0.045       0
   202.1    0.05       0   271.9     0.1       0
Bank Sta=184.1,202.1
XS Rating Curve= 0 ,0
Exp/Cntr(USF)=0,0
Exp/Cntr=0.3,0.1

Type RM Length L Ch R = 1 ,9433    ,196.5,216.2,209.1
XS GIS Cut Line= 3
2200176.11309907674974.3747782512200323.26464581674921.451853548
2200436.20991194674924.678861152
#Sta/Elev= 30
       0  1879.6    17.1 1878.87    21.3 1878.09    29.8 1874.72    38.3 1872.96
    46.8 1870.24    55.3 1865.14    59.6 1864.45    63.8 1864.44    68.1 1863.66
    80.8  1854.6    89.3 1849.42    97.8 1846.44   107.3 1844.57   114.8 1843.35
   123.3 1843.12   129.2 1843.46   133.5 1844.36   141.7 1848.31   144.6 1849.33
   148.8 1850.05   161.3 1850.59   180.3 1850.03   194.7 1850.22   213.3 1849.41
   229.3 1850.09   246.5  1853.3   253.3 1854.91   261.3 1855.82   269.4 1857.85
#Mann= 5, -1 ,  0
       0    0.06       0      70    0.05       0   107.3   0.045       0
   133.5    0.05       0  166.38     0.1       0
Bank Sta=107.3,133.5
XS Rating Curve= 0 ,0
Exp/Cntr(USF)=0,0
Exp/Cntr=0.3,0.1

Type RM Length L Ch R = 1 ,9217    ,144.1,150,160.9
XS GIS Cut Line= 4
2200190.53710235675127.0033747112200262.05275407675121.357402207
  2200350.976821675115.7114297042200504.82957173675122.298397625
#Sta/Elev= 30
       0 1879.26     5.7 1877.71     9.7 1875.47    13.7 1873.87    25.7 1870.13
    60.8 1861.45    69.9 1860.05    77.9 1858.09    81.9 1856.01    93.9 1845.15
    97.9 1842.11   101.9 1840.79     118 1840.41     126 1840.67     130 1841.55
     138  1844.4     146 1845.94     162 1846.58   214.1 1844.37   222.1 1843.09
   238.1 1843.24   246.1 1845.06   250.1  1847.5   262.1 1857.34   266.1  1859.3
   270.1 1859.13   278.1 1857.59   290.2 1858.69   301.6 1864.12   314.8 1868.51
#Mann= 5, -1 ,  0
       0     0.1       0      50    0.06       0    97.9   0.045       0
     130    0.06       0  141.74     0.1       0
#XS Ineff= 2 , 0
                          158.73         1851.96
Permanent Ineff=
       F       T
Bank Sta=97.9,130
XS Rating Curve= 0 ,0
Exp/Cntr(USF)=0,0
Exp/Cntr=0.3,0.1

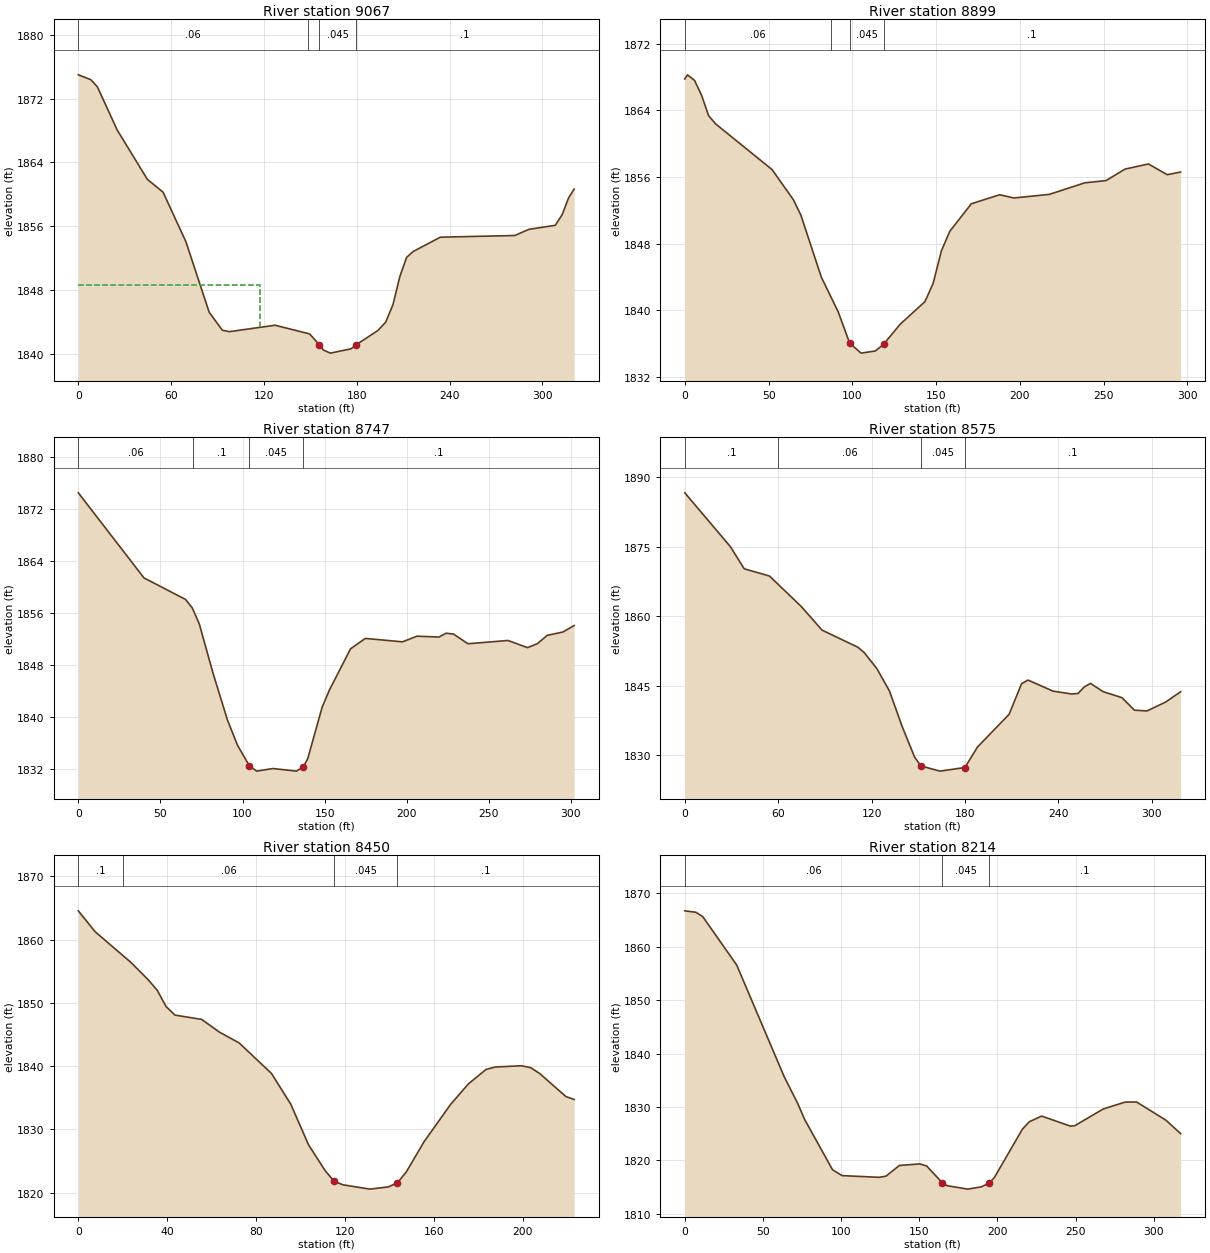
Type RM Length L Ch R = 1 ,9067    ,161.3,167.8,159.7
XS GIS Cut Line= 4
2200168.59691058675203.6579314762200289.27957285675247.273069067
2200365.07675371675285.3833834672200463.31667528 675328.57507312
#Sta/Elev= 30
       0 1874.97     8.1 1874.36    12.3 1873.47    25.1 1868.06    44.6 1861.87
    54.8 1860.25    69.6 1854.01    84.6 1845.19    93.1 1842.94    97.7 1842.76
   127.1 1843.57   149.5 1842.48   155.7 1841.14   158.4 1840.46   162.9 1840.07
   176.3 1840.61   179.6 1841.12   193.6  1842.9   198.7 1843.96   203.4 1846.16
   207.7 1849.59   212.2 1852.08   216.5 1852.82     234 1854.61   282.1 1854.82
   291.2 1855.59   308.3  1856.1   312.7 1857.42     317 1859.58   320.5 1860.64
#Mann= 4, -1 ,  0
       0    0.06       0  148.32     0.1       0   155.7   0.045       0
   179.6     0.1       0
#XS Ineff= 2 , 0
          117.52 1848.57
Permanent Ineff=
       T       F
Bank Sta=155.7,179.6
XS Rating Curve= 0 ,0
Exp/Cntr(USF)=0,0
Exp/Cntr=0.3,0.1

Type RM Length L Ch R = 1 ,8899    ,153.7,152.5,148.8
XS GIS Cut Line= 4
2200154.64668579675337.9619219192200218.42526408675358.872931192
2200293.70489746675413.2415553012200422.30760449675457.154674775
#Sta/Elev= 30
       0 1867.79     1.6 1868.29     5.8 1867.62      10 1865.84    14.2 1863.38
    18.4 1862.39    52.1 1856.89    64.8 1853.27    69.3  1851.4    81.5 1843.95
    91.6 1839.76    98.4 1836.02   105.2 1834.82   113.7 1835.08   118.6 1835.87
   128.5 1838.29   143.3 1841.01   148.2  1843.2   153.1  1847.1   158.1 1849.46
     171 1852.78   187.9 1853.87   196.4 1853.48   217.5 1853.91   238.7  1855.3
   251.4 1855.57   262.7 1856.95   276.7 1857.57   287.9 1856.28   295.9  1856.6
#Mann= 4, -1 ,  0
       0    0.06       0   87.12     0.1       0    98.4   0.045       0
   118.6     0.1       0
Bank Sta=98.4,118.6
XS Rating Curve= 0 ,0
Exp/Cntr(USF)=0,0
Exp/Cntr=0.3,0.1

Type RM Length L Ch R = 1 ,8747    ,176.7,171.7,165.3
XS GIS Cut Line= 3
 2200074.1733359675476.087021292  2200154.848526675502.548483644
2200350.40518679675596.777105676
#Sta/Elev= 30
       0 1874.48      40 1861.38    65.3 1858.07    69.5 1856.72    73.7 1854.28
    82.1 1846.67    90.8 1839.53    96.9 1835.65   104.1 1832.49   108.6 1831.64
   118.6 1832.04   132.8 1831.64     137 1832.27   139.7 1833.54   148.5 1841.47
     153 1844.16   165.8 1850.46   174.8 1852.07   197.4 1851.54   206.3 1852.41
   219.7 1852.28     224 1852.87   228.5 1852.74   237.3 1851.25   261.7 1851.75
   273.6 1850.65   279.6 1851.26   285.6 1852.54   295.1 1853.05     302 1854.05
#Mann= 4, -1 ,  0
       0    0.06       0      70     0.1       0   104.1   0.045       0
     137     0.1       0
Bank Sta=104.1,137
XS Rating Curve= 0 ,0
Exp/Cntr(USF)=0,0
Exp/Cntr=0.3,0.1

Type RM Length L Ch R = 1 ,8575    ,125.8,124.8,120
XS GIS Cut Line= 4
 2199982.5107448675653.1154372112200086.97902937675670.821926121
 2200188.7913406 675686.75776614 2200297.6862474675699.152308377
#Sta/Elev= 30
       0 1886.64    29.3 1875.02    38.2 1870.24    54.4 1868.68    74.7 1862.15
    88.2    1857   111.2 1853.31   115.3 1852.15   123.4  1848.7   131.5 1843.88
   139.6 1836.25   147.7 1829.57   151.7 1827.68   163.9 1826.56     180 1827.34
   188.1 1831.78   208.4 1838.83   216.4 1845.43   220.5 1846.22   236.6 1843.83
   248.6 1843.21   252.7 1843.33   256.7 1844.75   260.7  1845.5   268.8 1843.72
   280.9 1842.42   288.9 1839.72     297 1839.55     309 1841.48   318.6  1843.7
#Mann= 4, -1 ,  0
       0     0.1       0      60    0.06       0   151.7   0.045       0
     180     0.1       0
Bank Sta=151.7,180
XS Rating Curve= 0 ,0
Exp/Cntr(USF)=0,0
Exp/Cntr=0.3,0.1

Type RM Length L Ch R = 1 ,8450    ,224.8,236.6,241.6
XS GIS Cut Line= 3
2200024.62836945675799.7372893152200208.68732167675801.330873316
2200247.73012971675801.330873316
#Sta/Elev= 30
       0 1864.54     7.5 1861.26    23.5 1856.44    31.5 1853.63    35.5 1851.99
    39.5 1849.41    43.5 1848.07    55.5 1847.39    63.5 1845.38    72.4 1843.66
    86.9 1838.86    95.6 1833.99   103.6 1827.57   111.1 1823.48   115.1 1821.81
   119.1 1821.26   131.2 1820.58   139.6 1820.94   143.6 1821.59   147.6 1823.31
   155.6 1828.09   167.5 1833.96   175.5  1837.2   183.4 1839.47   187.6 1839.87
   199.4 1840.07   203.6 1839.76   207.6 1838.84   219.4  1835.2   223.1 1834.74
#Mann= 4, -1 ,  0
       0     0.1       0      20    0.06       0   115.1   0.045       0
   143.6     0.1       0
Bank Sta=115.1,143.6
XS Rating Curve= 0 ,0
Exp/Cntr(USF)=0,0
Exp/Cntr=0.3,0.1

Type RM Length L Ch R = 1 ,8214    ,192.5,195.6,196.9
XS GIS Cut Line= 3
2199985.59716003 675955.982872022200116.42843919676011.069726405
2200276.77053321676081.895682044
#Sta/Elev= 30
       0 1866.71     7.1 1866.44    11.5 1865.62    33.2 1856.57    63.6 1835.66
    72.2 1830.69    76.6 1827.71    94.5 1818.26   100.6 1817.16   124.3 1816.84
   128.7 1817.06   137.3 1819.06   150.4 1819.35   154.8 1818.95   164.6 1815.86
   167.9 1815.27     181 1814.63   189.8 1815.06   194.9  1815.8     198 1816.78
     216 1825.86   220.4 1827.24   228.3  1828.3   246.6 1826.43   249.5  1826.5
   267.7 1829.63   281.6 1830.91     289 1830.94   307.8 1827.53   317.2 1825.02
#Mann= 3, -1 ,  0
       0    0.06       0   164.6   0.045       0   194.9     0.1       0
Bank Sta=164.6,194.9
XS Rating Curve= 0 ,0
Exp/Cntr(USF)=0,0
Exp/Cntr=0.3,0.1