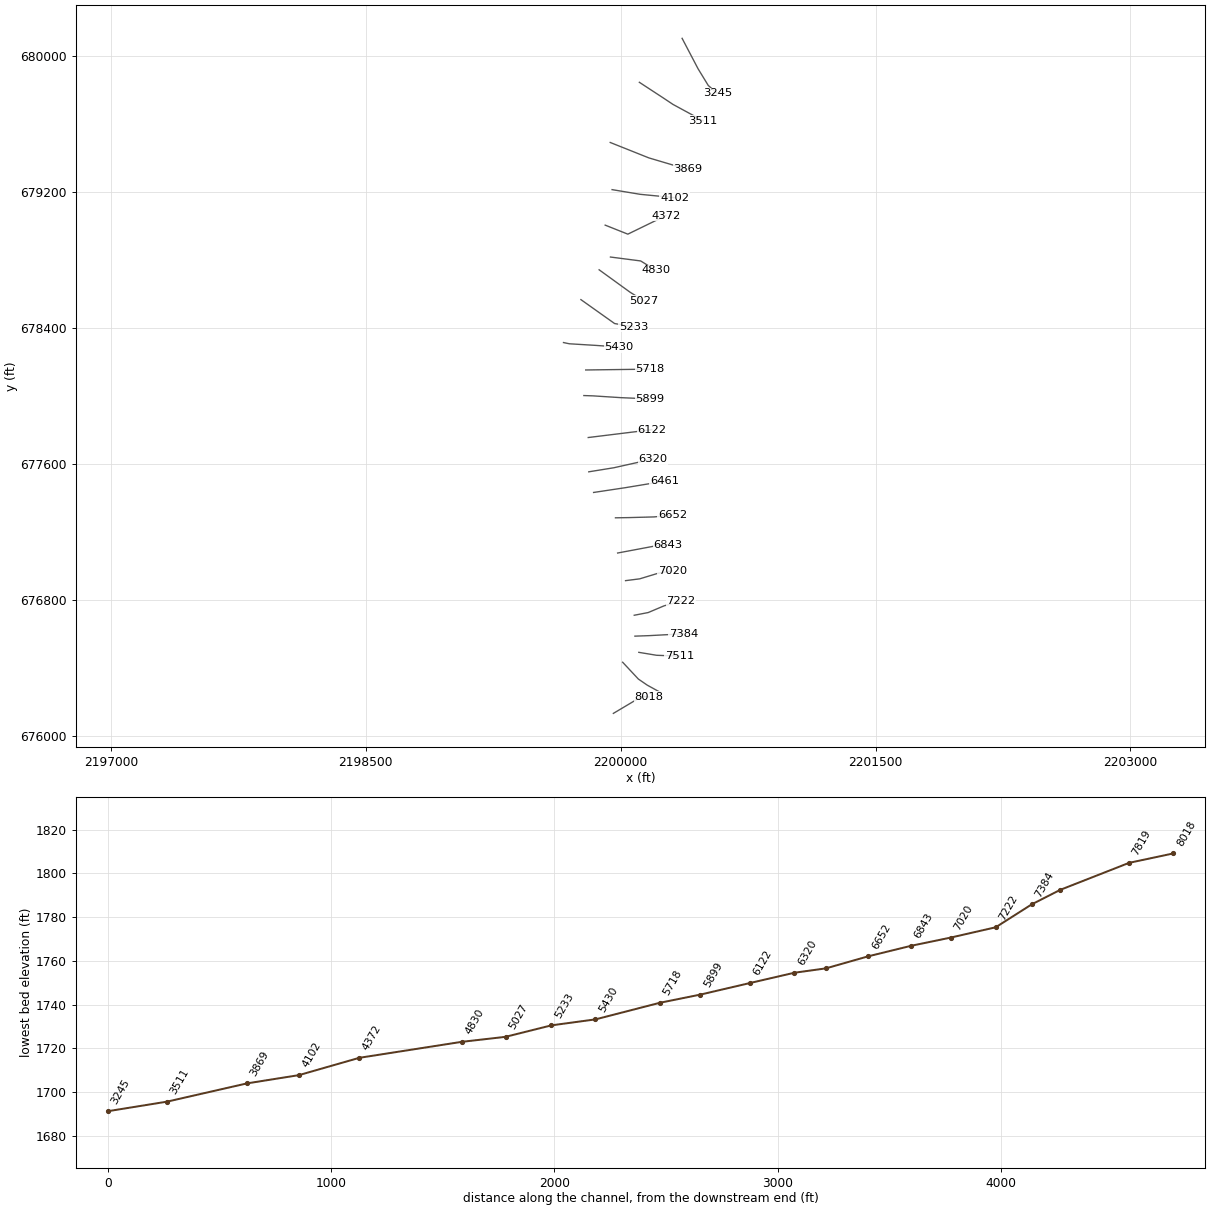
HEC-RAS study RFTENMILCK.prj: RFTENMILCK

--- RFTENMILCK.g01 (geometry) --- (continued)

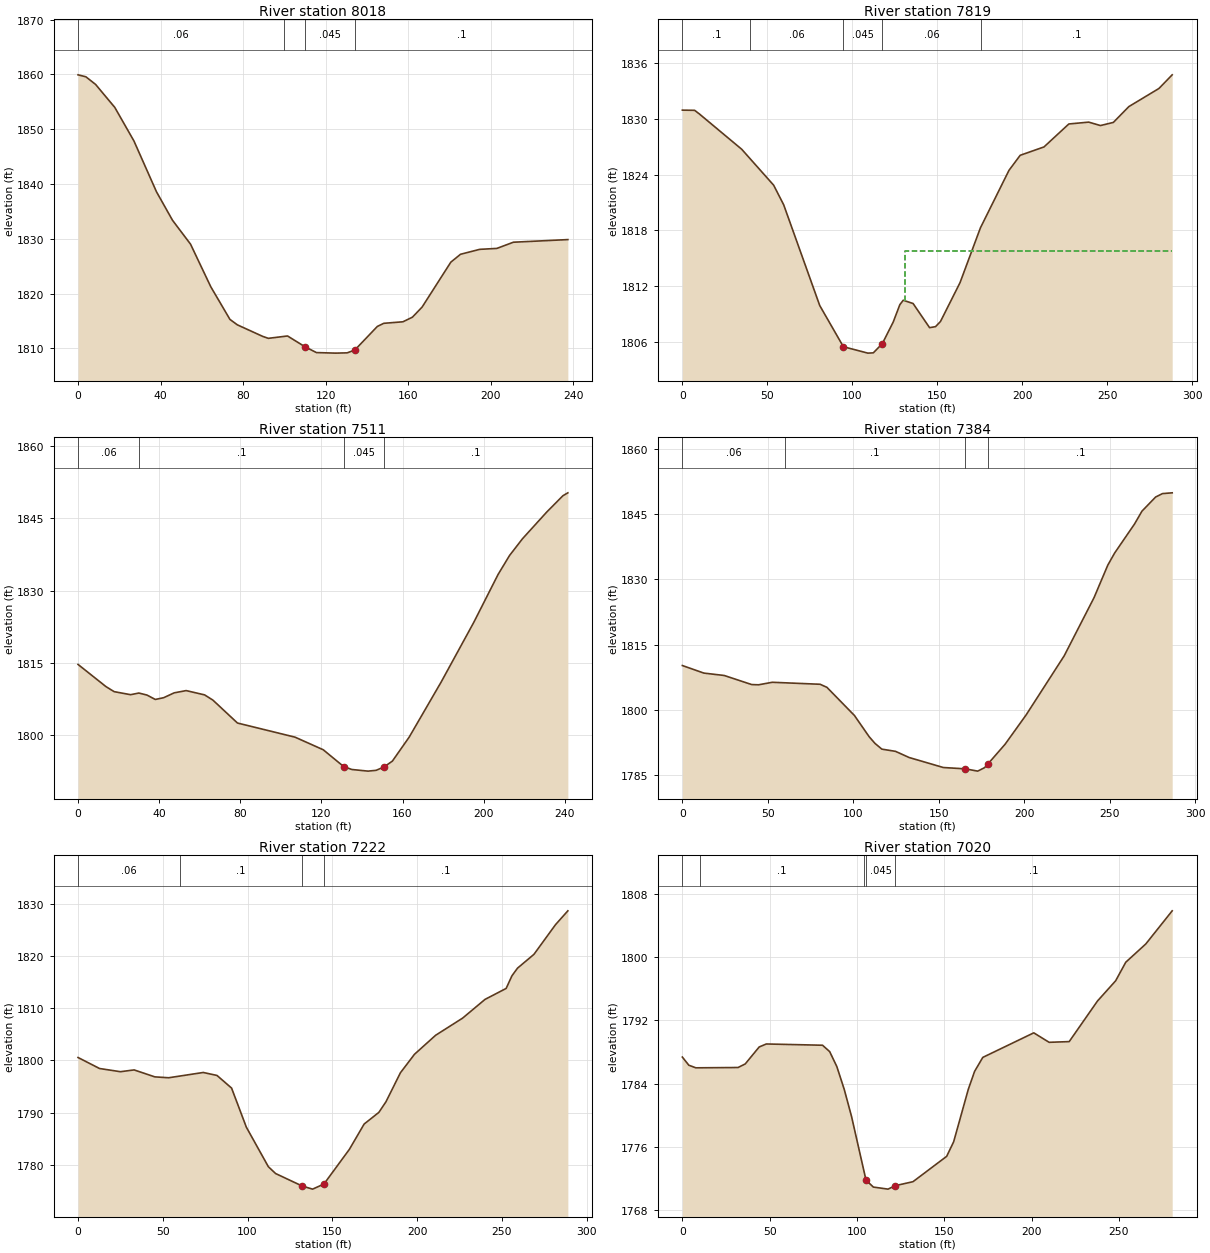
Type RM Length L Ch R = 1 ,8018    ,218.5,198.7,172.5
XS GIS Cut Line= 3
2199956.88240851676133.7464266232200125.80231271676234.142218741
2200166.43870476676230.158258736
#Sta/Elev= 30
       0 1859.91     3.8 1859.55     8.5 1858.16    17.8 1853.97    27.1 1847.83
      38 1838.57    45.8 1833.35    54.5 1829.01    64.3 1821.24    73.6 1815.27
    77.2 1814.28    89.5 1812.17    92.2 1811.82   101.5 1812.25     110 1810.27
   115.5 1809.22   124.8 1809.12   130.4 1809.17   134.1 1809.69     145 1813.99
   148.1 1814.56   157.4 1814.84     162 1815.68   166.7 1817.53   180.6 1825.72
   185.3 1827.16   194.6 1828.06   202.9 1828.23   210.9 1829.36   237.3 1829.84
#Mann= 4, -1 ,  0
       0    0.06       0     100     0.1       0     110   0.045       0
   134.1     0.1       0
Bank Sta=110,134.1
XS Rating Curve= 0 ,0
Exp/Cntr(USF)=0,0
Exp/Cntr=0.3,0.1

Type RM Length L Ch R = 1 ,7819    ,290,308,313.9
XS GIS Cut Line= 4
2200011.47198745676434.6399699882200103.97953876676335.678403471
2200156.32877322676299.8227634292200234.49406852676256.795995378
#Sta/Elev= 30
       0 1830.95     7.2 1830.93      10 1830.54    34.9 1826.74    53.7 1822.87
    59.6 1820.76    80.8 1809.92    94.7 1805.49   109.1  1804.8   112.3 1804.83
   117.6 1805.82     124 1808.14   127.9 1810.01   129.9 1810.49   135.7 1810.14
   145.4 1807.54   148.9 1807.65   151.8  1808.2   163.3 1812.38   175.3 1818.28
   192.1 1824.47   198.7 1826.09   212.7 1826.99   227.3 1829.46     239 1829.66
   245.9 1829.29   253.5 1829.63   262.6 1831.33   280.3 1833.28   288.1 1834.75
#Mann= 5, -1 ,  0
       0     0.1       0      40    0.06       0    94.7   0.045       0
   117.6    0.06       0  175.47     0.1       0
#XS Ineff= 2 , 0
                          130.65         1815.74
Permanent Ineff=
       F       T
Bank Sta=94.7,117.6
XS Rating Curve= 0 ,0
Exp/Cntr(USF)=0,0
Exp/Cntr=0.3,0.1

Type RM Length L Ch R = 1 ,7511    ,125.3,126.9,127.2
XS GIS Cut Line= 3
2200106.58656251676492.8989310412200211.14160887676475.647348391
2200346.54039391676470.419596073
#Sta/Elev= 30
       0 1814.65    13.8 1810.03    17.8 1808.99    25.9 1808.36      30  1808.7
      34 1808.28    38.1 1807.37    42.2 1807.73    47.4 1808.74    53.3 1809.21
    62.4 1808.32    66.5 1807.23    78.6 1802.47     107 1799.53   120.9 1796.91
     131 1793.41     135 1792.81     143 1792.47     147 1792.64     151 1793.37
     155 1794.56   163.3 1799.56   179.1 1811.04   195.1 1823.38   207.1 1833.35
   212.7 1837.26   219.1 1840.76   231.1 1846.33   239.1 1849.73   241.5 1850.32
#Mann= 4, -1 ,  0
       0    0.06       0      30     0.1       0     131   0.045       0
     151     0.1       0
Bank Sta=131,151
XS Rating Curve= 0 ,0
Exp/Cntr(USF)=0,0
Exp/Cntr=0.3,0.1

Type RM Length L Ch R = 1 ,7384    ,158.2,162.5,166.1
XS GIS Cut Line= 3
 2200083.5937368676588.2523530882200167.20771221676591.203434573
2200369.84864084676602.024066685
#Sta/Elev= 30
       0 1810.18    12.6 1808.44    24.5 1807.89    40.6  1805.8    44.6 1805.75
    52.6 1806.33    80.6 1805.87    84.6 1805.16   100.7 1798.68   109.3  1793.8
   112.7 1792.27   116.7 1790.95   124.7 1790.44   132.7 1789.02   152.7 1786.72
   165.61786.413   172.8 1785.89   176.8 1786.68     1791787.644   188.8 1792.06
   201.1  1798.8   223.4 1812.41   240.9 1825.82   248.9 1833.26   252.9 1836.05
   264.6 1842.76   268.9 1845.69   276.9 1848.94   280.9 1849.73   286.6 1849.91
#Mann= 4, -1 ,  0
       0    0.06       0      60     0.1       0   165.6   0.045       0
     179     0.1       0
Bank Sta=165.6,179
XS Rating Curve= 0 ,0
Exp/Cntr(USF)=0,0
Exp/Cntr=0.3,0.1

Type RM Length L Ch R = 1 ,7222    ,203,202.2,200.2
XS GIS Cut Line= 4
2200079.65896148676711.2140816282200161.77798015 676727.05438595
2200254.68239727676766.4021390832200355.23776639 676794.81996079
#Sta/Elev= 30
       0 1800.56    12.7 1798.45      25 1797.84    33.1 1798.18    45.3 1796.85
    53.5 1796.68    73.9 1797.69      82 1797.12    90.6  1794.7    99.3 1787.22
   112.3 1779.64   116.6 1778.33   132.41775.925   138.4 1775.35   145.1 1776.33
   160.1 1782.97   168.8 1787.81   177.5 1790.05   181.7 1792.09   190.2 1797.63
   198.5 1801.17     211 1804.82   226.9  1808.1   240.1 1811.68   252.6 1813.79
     256  1816.2   259.3 1817.67     269 1820.32   281.7 1825.99     289 1828.65
#Mann= 4, -1 ,  0
       0    0.06       0      60     0.1       0   132.4   0.045       0
   145.1     0.1       0
Bank Sta=132.4,145.1
XS Rating Curve= 0 ,0
Exp/Cntr(USF)=0,0
Exp/Cntr=0.3,0.1

Type RM Length L Ch R = 1 ,7020    ,178,177.1,175.7
XS GIS Cut Line= 4
2200028.50688241 676914.838704092200111.93494253676925.501257008
2200219.50186266676958.1697290472200302.36823076676972.511985063
#Sta/Elev= 30
       0 1787.35     3.7 1786.32     7.7 1785.99    31.9 1786.03      36 1786.48
      44 1788.63    48.1 1789.01    80.3 1788.85    84.4 1788.04    88.5 1786.14
    92.7 1783.28    96.9 1779.84   105.21771.769   109.4 1770.89   117.8 1770.63
     122 1771.07   132.1 1771.57   151.4 1774.78   155.4 1776.62   163.8 1783.27
   167.4 1785.54   172.1 1787.31   201.3 1790.42   210.1 1789.22   221.6 1789.31
   237.8 1794.45   248.2 1797.01     254 1799.36   265.5 1801.68   280.6 1805.87
#Mann= 5, -1 ,  0
       0    0.06       0      10     0.1       0  104.11    0.06       0
   105.2   0.045       0     122     0.1       0
Bank Sta=105.2,122
XS Rating Curve= 0 ,0
Exp/Cntr(USF)=0,0
Exp/Cntr=0.3,0.1

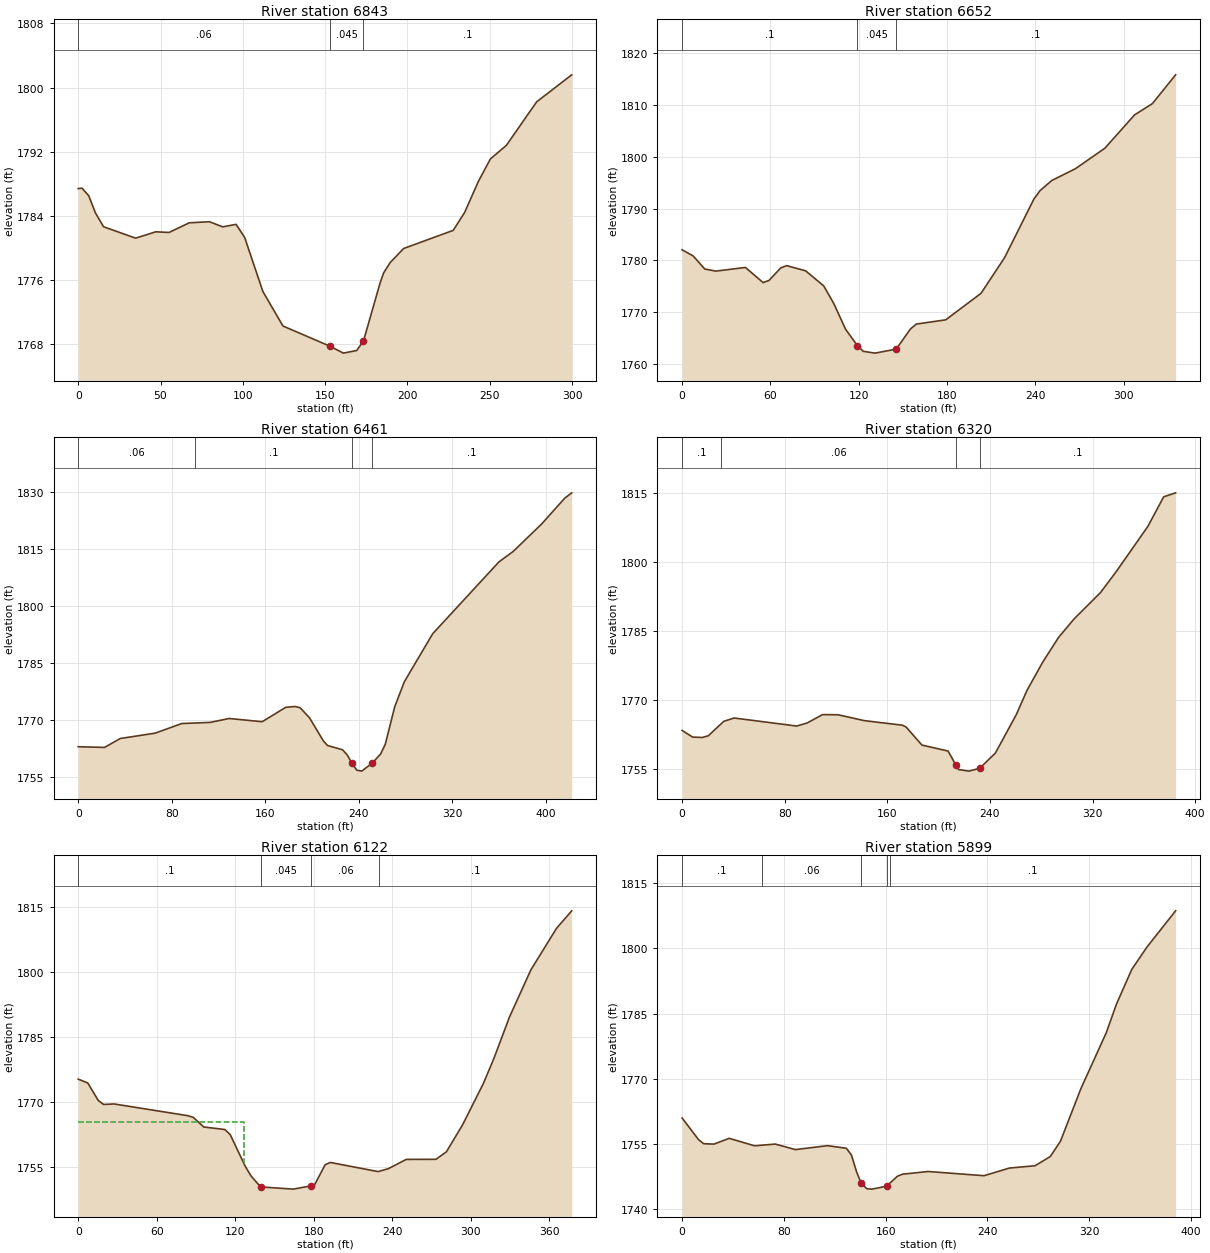
Type RM Length L Ch R = 1 ,6843    ,192.6,190.5,185.8
XS GIS Cut Line= 3
2199981.89322306677077.4396572642200216.31469466677121.512089239
 2200277.5030554 677125.24717732
#Sta/Elev= 30
       0  1787.4     2.3 1787.46     6.4 1786.51    10.5 1784.35    15.4 1782.64
    34.9 1781.22    47.1 1782.01    55.2 1781.93    67.4 1783.13    79.7 1783.27
    87.8 1782.63    95.9 1782.94   101.1 1781.32   112.2 1774.56   124.4 1770.26
     1531767.736   161.1 1766.88   169.2 1767.21   173.3 1768.39   183.3 1775.57
   185.5 1776.87   189.5 1778.17   197.7 1779.93   227.8 1782.19   234.7  1784.4
     243 1788.25   250.4  1791.1   260.1 1792.79   278.5 1798.22   299.8 1801.59
#Mann= 3, -1 ,  0
       0    0.06       0     153   0.045       0   173.3     0.1       0
Bank Sta=153,173.3
XS Rating Curve= 0 ,0
Exp/Cntr(USF)=0,0
Exp/Cntr=0.3,0.1

Type RM Length L Ch R = 1 ,6652    ,187.3,190.9,191.4
XS GIS Cut Line= 4
2199969.14455104677284.6055775082200049.17628206677285.900509109
2200195.74666248677289.835284422 2200303.9529836677299.672222705
#Sta/Elev= 30
       0 1782.07     7.5 1780.89    15.4 1778.35      23 1777.95      43 1778.66
      55 1775.74      59 1776.14      67 1778.56      71 1779.01    83.9 1778.01
    96.2  1775.1     103 1771.72   111.1 1766.71   119.1 1763.56   123.1 1762.46
   131.1 1762.11   145.5 1762.89   155.1 1766.76   159.1 1767.72   179.1 1768.54
   203.1 1773.66   219.1 1780.55   239.1 1791.91   243.2  1793.5   251.2 1795.46
   267.3 1797.74   287.3  1801.7   307.4 1808.12   319.5 1810.29   335.3 1815.86
#Mann= 3, -1 ,  0
       0     0.1       0   119.1   0.045       0   145.5     0.1       0
Bank Sta=119.1,145.5
XS Rating Curve= 0 ,0
Exp/Cntr(USF)=0,0
Exp/Cntr=0.3,0.1

Type RM Length L Ch R = 1 ,6461    ,138.8,140.9,140.3
XS GIS Cut Line= 4
2199840.53740379677433.8218299382200027.53501784677461.981704377
2200170.17062295677485.5903562572200257.71937367677498.378376025
#Sta/Elev= 30
       0    1763    22.5 1762.82      36 1765.17    65.9 1766.58    88.6 1769.11
   112.9 1769.41   129.1 1770.44   157.4 1769.59   177.6 1773.39   185.7  1773.6
   189.8 1773.28   197.9 1770.62   209.8  1764.5   213.3 1763.33   226.2 1762.19
   230.3 1760.78   234.2  1758.6   238.4 1756.82   242.5 1756.57   251.51758.659
   258.7 1761.08   262.7 1763.64   270.8 1773.54     279 1780.12   303.3 1792.78
     360 1811.72   372.1 1814.45   396.3 1821.63   416.2 1828.48   422.2  1829.9
#Mann= 4, -1 ,  0
       0    0.06       0     100     0.1       0   234.2   0.045       0
   251.5     0.1       0
Bank Sta=234.2,251.5
XS Rating Curve= 0 ,0
Exp/Cntr(USF)=0,0
Exp/Cntr=0.3,0.1

Type RM Length L Ch R = 1 ,6320    ,198.8,198.6,190.5
XS GIS Cut Line= 3
2199812.05061406677555.2655124462199959.88205968677579.254388003
 2200189.2756822677630.530609507
#Sta/Elev= 30
       0 1763.44     8.2 1761.99    15.7  1761.9    20.4 1762.27    32.5 1765.42
    40.6 1766.14    89.3 1764.39    97.4 1765.04   109.5 1766.88   121.7 1766.84
     142 1765.57   171.7 1764.58   174.7 1764.17     187 1760.25   207.4 1758.95
   213.6 1755.83   215.6 1754.92   223.8 1754.58   232.11755.213   244.3 1758.52
   260.7 1766.94   268.9 1772.14   281.2  1778.3   293.5 1783.66   305.8 1787.75
   326.3 1793.45   338.6 1798.03   363.2 1807.85   375.5 1814.27   384.8 1815.14
#Mann= 4, -1 ,  0
       0     0.1       0      30    0.06       0   213.6   0.045       0
   232.1     0.1       0
Bank Sta=213.6,232.1
XS Rating Curve= 0 ,0
Exp/Cntr(USF)=0,0
Exp/Cntr=0.3,0.1

Type RM Length L Ch R = 1 ,6122    ,225.5,222.3,220.8
XS GIS Cut Line= 2
2199808.96919636 677757.06873395 2200183.1130711677803.104864175
#Sta/Elev= 30
       0 1775.23     7.3 1774.34    15.3 1770.32    19.4 1769.39    27.4 1769.51
    83.8  1766.8    87.9 1766.42    95.9  1764.2     112 1763.62   116.1 1762.46
   127.6 1755.15   131.9 1752.97   139.3 1750.39   164.4 1749.88   178.2 1750.66
   180.6 1750.88   188.6 1755.49   192.6 1756.03   229.1 1753.92     237  1754.6
   250.6 1756.73   273.3 1756.75   281.3 1758.49   293.7 1764.73   309.5 1774.21
   317.6 1780.02   329.5 1789.57   345.8  1800.4   365.4 1809.98     377 1814.01
#Mann= 4, -1 ,  0
       0     0.1       0   139.3   0.045       0   178.2    0.06       0
     230     0.1       0
#XS Ineff= 2 , 0
          126.65 1765.33
Permanent Ineff=
       F       F
Bank Sta=139.3,178.2
XS Rating Curve= 0 ,0
Exp/Cntr(USF)=0,0
Exp/Cntr=0.3,0.1

Type RM Length L Ch R = 1 ,5899    ,176,181.8,186.4
XS GIS Cut Line= 4
2199783.23617962678004.0838347982199836.27366029678002.295669585
2199999.69787503677991.8005365292200170.61861337677984.304012918
#Sta/Elev= 30
       0 1760.96    12.9 1755.99    16.9 1755.05      25 1754.95      37 1756.28
      57 1754.56    73.2 1754.96      89 1753.69   114.3 1754.59   129.1    1754
   133.1 1752.44   137.1 1748.61   140.7 1745.98   145.2 1744.68   149.2 1744.59
   160.71745.259   169.2 1747.55   173.2 1748.02   193.3 1748.65   237.3 1747.68
   257.3 1749.44   277.4 1749.97   289.4 1752.09   297.4 1755.61   313.4 1767.68
   333.4 1780.58   341.4 1787.16   353.4 1795.13   365.4 1800.31   387.9 1808.64
#Mann= 5, -1 ,  0
       0     0.1       0   63.07    0.06       0   140.7   0.045       0
   160.7    0.06       0  163.07     0.1       0
Bank Sta=140.7,160.7
XS Rating Curve= 0 ,0
Exp/Cntr(USF)=0,0
Exp/Cntr=0.3,0.1

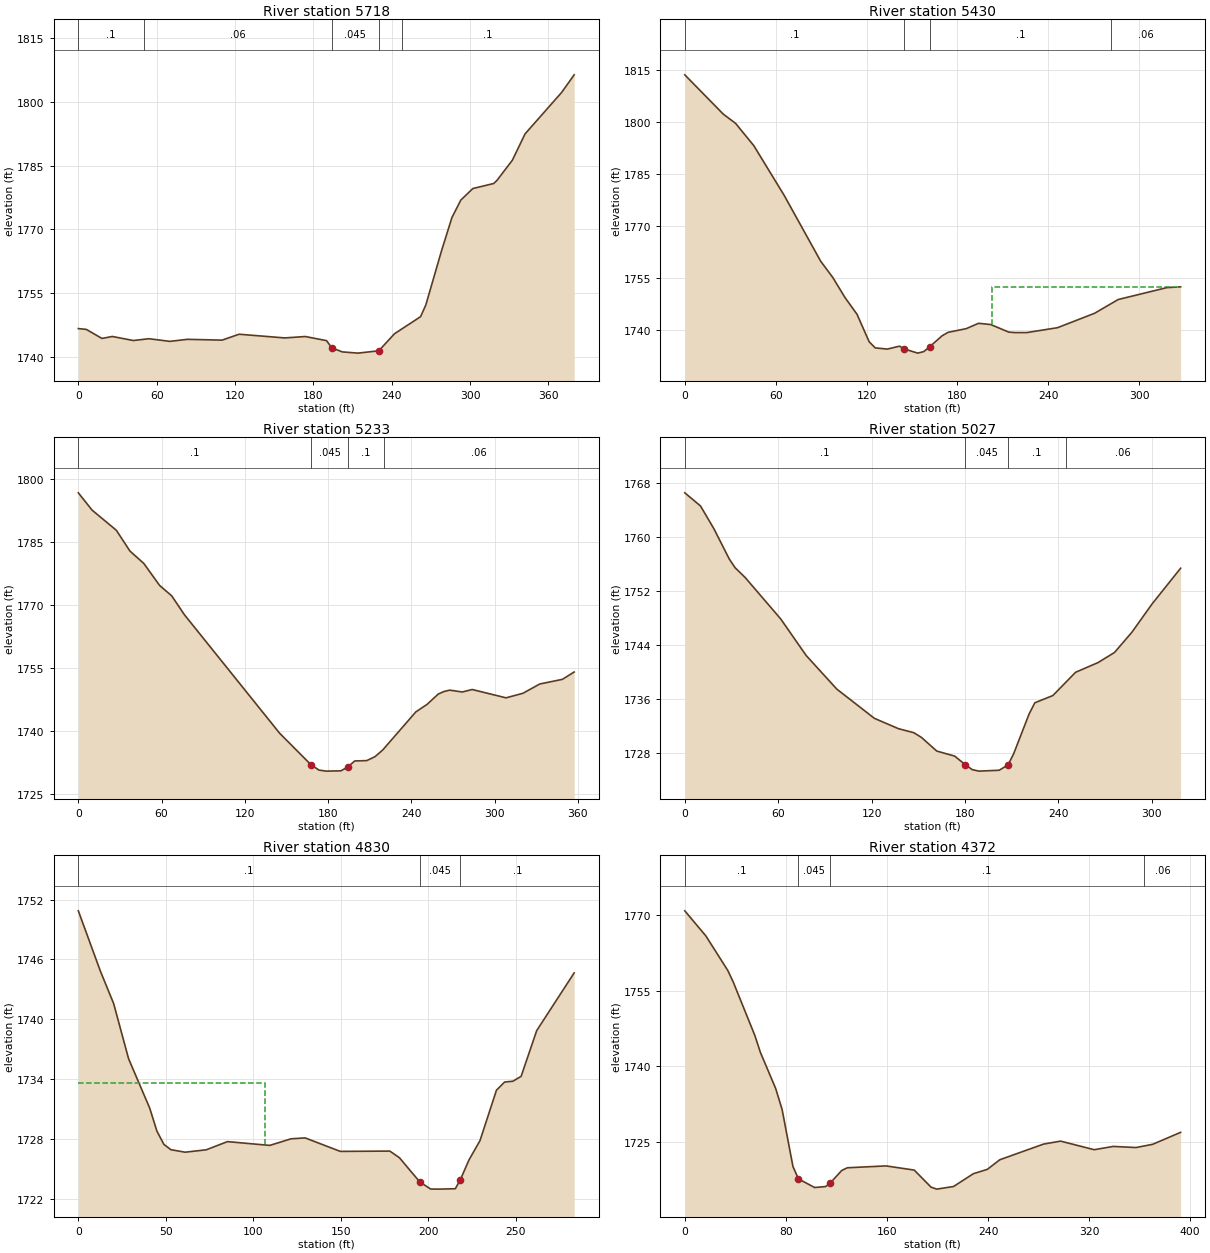
Type RM Length L Ch R = 1 ,5718    ,272.4,287.7,290.2
XS GIS Cut Line= 3
2199794.05681173 678154.588990532199941.61088598678156.556378187
2200173.76262946678159.507459672
#Sta/Elev= 30
       0 1746.62     6.1 1746.43    18.1  1744.3    26.1 1744.76    42.1 1743.81
    54.1 1744.23    70.1 1743.61    83.6 1744.09   110.1  1743.9   123.1 1745.29
   158.1 1744.42   173.8 1744.75   190.1 1743.78   194.2 1742.06   202.2 1741.13
   214.1 1740.84   230.1 1741.39   242.1  1745.4   262.1 1749.43   266.1 1752.17
   278.1  1764.9   286.1 1772.77   292.9 1776.88   302.1  1779.6   318.1 1780.79
   320.6 1781.52   332.4 1786.28   342.1 1792.47   370.1 1802.23   379.7 1806.38
#Mann= 5, -1 ,  0
       0     0.1       0      50    0.06       0   194.2   0.045       0
   230.1    0.06       0  247.57     0.1       0
Bank Sta=194.2,230.1
XS Rating Curve= 0 ,0
Exp/Cntr(USF)=0,0
Exp/Cntr=0.3,0.1

Type RM Length L Ch R = 1 ,5430    ,202.2,197.2,186.7
XS GIS Cut Line= 4
2199663.35988526678315.956508523 2199697.6219413678308.785380514
2199853.79317348678299.2238765032199989.24781364678289.662372492
#Sta/Elev= 30
       0 1813.62    25.4 1802.27    33.5 1799.62    45.6 1793.14    65.6 1778.82
    89.7 1759.81    97.7 1755.11   105.7 1749.35   113.7 1744.47   121.7 1736.56
   125.7 1734.78   133.7 1734.44   141.8 1735.28   144.9 1734.47   153.8 1733.27
   157.8 1733.72   161.7 1735.12   169.8 1738.26   173.8 1739.27   185.8 1740.34
   193.9 1741.88   201.9 1741.53   213.9 1739.33   217.9 1739.21   225.9 1739.21
     246 1740.61   270.5 1744.77   286.1 1748.75   318.2 1752.18   327.3 1752.42
#Mann= 4, -1 ,  0
       0     0.1       0   144.9   0.045       0   161.7     0.1       0
  281.47    0.06       0
#XS Ineff= 2 , 0
                        202.7852         1752.42
Permanent Ineff=
       F       T
Bank Sta=144.9,161.7
XS Rating Curve= 0 ,0
Exp/Cntr(USF)=0,0
Exp/Cntr=0.3,0.1

Type RM Length L Ch R = 1 ,5233    ,204.6,205.3,204.6
XS GIS Cut Line= 3
2199765.83597499678568.6052785992199964.14865078678427.838691767
2200076.58485536678408.361553966
#Sta/Elev= 30
       0 1796.72     9.9 1792.61    27.4 1787.81    37.2 1782.87    47.2 1779.92
    58.6 1774.69    67.3 1772.22    76.4 1767.75   145.1 1739.54   167.7 1732.04
   173.4 1730.79   178.7 1730.54   189.3 1730.61   194.2 1731.55   199.2 1732.96
   207.8 1733.04   213.8 1733.98   219.3 1735.55   243.2 1744.62   251.3 1746.41
   259.4 1748.88   263.5 1749.47   267.6  1749.8   276.7 1749.36   283.8 1749.95
   308.2 1747.97   320.4 1749.05   332.5 1751.26   348.8 1752.36   357.3 1754.11
#Mann= 4, -1 ,  0
       0     0.1       0   167.7   0.045       0   194.2     0.1       0
     220    0.06       0
Bank Sta=167.7,194.2
XS Rating Curve= 0 ,0
Exp/Cntr(USF)=0,0
Exp/Cntr=0.3,0.1

Type RM Length L Ch R = 1 ,5027    ,193.6,197.2,197.1
XS GIS Cut Line= 3
2199873.02422547678744.1433748712200055.17087689678612.194619516
2200134.77039778678562.713836258
#Sta/Elev= 30
       0 1766.61    10.1 1764.66    18.7 1761.28    28.6 1756.78    32.3  1755.5
    38.8 1754.04    61.7 1747.87      78 1742.46    97.7 1737.47   121.8 1733.14
   137.3  1731.6   147.1 1731.01   152.1  1730.3   161.9 1728.28   173.4 1727.53
   180.1 1726.28   184.8 1725.51   189.1  1725.3     202 1725.43   207.7 1726.22
   211.3 1727.87   221.2 1733.76   224.9 1735.44   236.5 1736.52   251.1 1739.97
   265.6 1741.42   276.1 1742.91   287.3 1745.92   300.4 1750.16   318.6 1755.42
#Mann= 4, -1 ,  0
       0     0.1       0   180.1   0.045       0   207.7     0.1       0
  244.92    0.06       0
Bank Sta=180.1,207.7
XS Rating Curve= 0 ,0
Exp/Cntr(USF)=0,0
Exp/Cntr=0.3,0.1

Type RM Length L Ch R = 1 ,4830    ,453.7,458,455.7
XS GIS Cut Line= 3
2199939.66982073678819.2619447172200117.51795459678796.207556994
2200205.97152382678741.629822792
#Sta/Elev= 30
       0 1750.87    12.6 1744.83    20.2 1741.57    28.7 1736.06    40.8  1731.1
    44.9  1728.8    48.9 1727.47    52.9 1726.94      61 1726.69    73.1 1726.93
    85.2 1727.75   109.4 1727.37   121.5 1728.03   129.6 1728.12   149.7 1726.77
     178  1726.8   183.5 1726.13   195.1 1723.71   201.3    1723     206 1722.99
   215.4 1723.03   218.3 1723.95   223.2 1725.91   229.5 1727.85   238.9  1732.9
   243.6 1733.72   248.3  1733.8     253 1734.29   261.9 1738.87   283.3 1744.65
#Mann= 3, -1 ,  0
       0     0.1       0   195.1   0.045       0   218.3     0.1       0
#XS Ineff= 2 , 0
          106.48 1733.63
Permanent Ineff=
       T       F
Bank Sta=195.1,218.3
XS Rating Curve= 0 ,0
Exp/Cntr(USF)=0,0
Exp/Cntr=0.3,0.1

Type RM Length L Ch R = 1 ,4372    ,262,269.8,268.5
XS GIS Cut Line= 3
2199908.61459014679006.977043625 2200041.9975711678953.910696363
2200265.73676496679062.911842091
#Sta/Elev= 30
       0 1770.83    16.7 1765.85      34 1759.03    38.3 1756.75    55.5  1746.1
    59.8 1742.81    71.9 1735.65      77 1731.49    85.6 1720.18    89.9 1717.74
   102.7 1716.02   111.5 1716.21     115 1716.88   124.2  1719.4   128.7 1719.93
   159.3  1720.3   181.6 1719.47   194.9 1716.09   199.4  1715.7   212.7 1716.22
   228.4 1718.76   239.4 1719.61   249.3 1721.52   283.9 1724.62   297.4 1725.21
     324 1723.51   339.1 1724.16   357.1 1723.94   370.2 1724.57   392.4 1726.95
#Mann= 4, -1 ,  0
       0     0.1       0    89.9   0.045       0     115     0.1       0
  363.55    0.06       0
Bank Sta=89.9,115
XS Rating Curve= 0 ,0
Exp/Cntr(USF)=0,0
Exp/Cntr=0.3,0.1

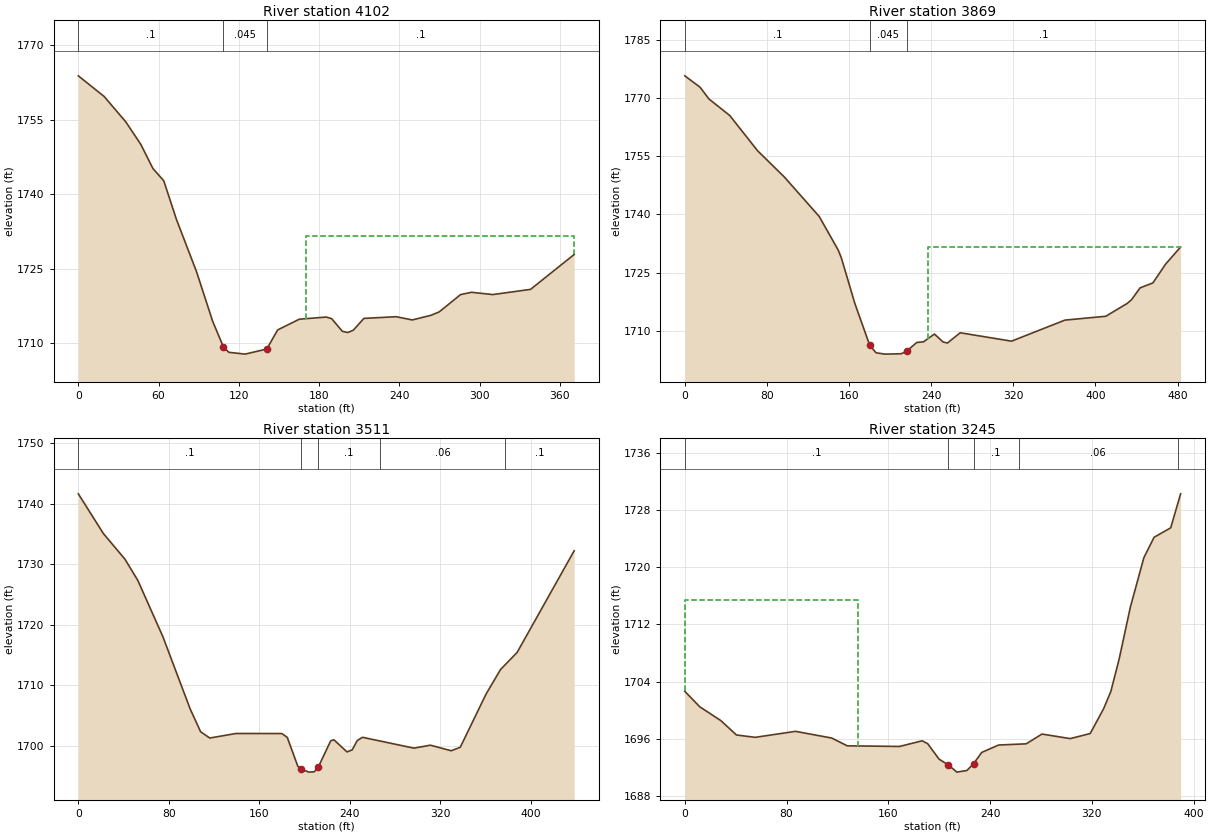
Type RM Length L Ch R = 1 ,4102    ,237.7,233.3,228.5
XS GIS Cut Line= 4
2199949.18180015679215.8821297822200016.04860673679204.739064693
2200114.41798956679188.3441675552200316.62172094679168.670290988
#Sta/Elev= 30
       0 1763.88    19.3 1759.72    35.5  1754.6    46.7 1750.07    55.8 1745.19
    63.9 1742.72    73.3 1734.98    88.4 1724.39   100.4 1714.45   108.5 1709.23
   112.5 1708.17   124.7  1707.8   140.9 1708.83     149 1712.67   165.2 1714.84
   185.4 1715.27   189.4 1714.95   197.4  1712.4   201.4 1712.16   205.5  1712.6
   213.5    1715   237.6 1715.34   249.7 1714.69   263.6 1715.62   269.8 1716.31
   285.8  1719.8   293.9 1720.26   309.9  1719.8   338.1 1720.85   370.7 1727.88
#Mann= 3, -1 ,  0
       0     0.1       0   108.5   0.045       0   140.9     0.1       0
#XS Ineff= 2 , 0
                        169.8999          1731.6
Permanent Ineff=
       F       T
Bank Sta=108.5,140.9
XS Rating Curve= 0 ,0
Exp/Cntr(USF)=0,0
Exp/Cntr=0.3,0.1

Type RM Length L Ch R = 1 ,3869    ,359.9,358.3,354.7
XS GIS Cut Line= 3
2199938.29766244679493.397204272 2200165.6402361679402.678773439
 2200394.0758029679334.913198599
#Sta/Elev= 30
       0 1775.68    14.9 1772.74    23.6  1769.7    43.8 1765.46    70.9 1756.39
    96.8 1749.67   130.9 1739.48   149.4 1730.83   152.5  1728.8   165.7 1717.02
   180.2 1706.26   186.3 1704.36   194.9 1704.01   210.9 1704.11     2161704.767
     226 1707.01   232.5 1707.18   243.2 1709.18   251.6 1707.14   255.8 1706.86
   268.3 1709.51   318.3 1707.35   370.3 1712.77   410.1 1713.76     431 1717.07
   435.2 1718.03   443.5 1721.07     456 1722.35   468.5 1727.23     483  1731.6
#Mann= 3, -1 ,  0
       0     0.1       0   180.2   0.045       0     216     0.1       0
#XS Ineff= 2 , 0
                        236.9254          1731.6
Permanent Ineff=
       F       T
Bank Sta=180.2,216
XS Rating Curve= 0 ,0
Exp/Cntr(USF)=0,0
Exp/Cntr=0.3,0.1

Type RM Length L Ch R = 1 ,3511    ,271,265.5,259.3
XS GIS Cut Line= 4
2200109.69068178679847.5494720362200251.77979031679754.645054917
2200307.52244058 679717.483288072200484.58732968679621.299891524
#Sta/Elev= 30
       0 1741.62    22.1 1735.07    41.2 1730.83    52.6 1727.32    74.7 1718.05
    98.9 1706.08   108.1 1702.33   116.2 1701.29   139.3 1702.04   179.9 1702.03
   184.7  1701.4     194 1696.64     1971696.154   203.9 1695.66   208.5 1695.71
     2121696.452   223.1 1700.83   225.9    1701   237.5    1699   242.1 1699.34
   246.6 1700.88   251.2 1701.41   296.7 1699.62   311.2 1700.11   329.6 1699.19
   337.6 1699.76   360.4 1708.54   373.2  1712.6   387.9 1715.43   438.3 1732.21
#Mann= 5, -1 ,  0
       0     0.1       0     197   0.045       0     212     0.1       0
  266.76    0.06       0  376.76     0.1       0
Bank Sta=197,212
XS Rating Curve= 0 ,0
Exp/Cntr(USF)=0,0
Exp/Cntr=0.3,0.1

Type RM Length L Ch R = 1 ,3245    ,217.6,220.5,223
XS GIS Cut Line= 4
2200361.30783183680106.2526693882200455.30524209679927.001794007
2200515.41986493679828.6324111752200570.06952206679781.633706045
#Sta/Elev= 30
       0 1702.62    11.8 1700.45    28.3 1698.52    40.6  1696.5    55.4 1696.17
      87 1697.01   115.5 1696.07   127.7 1694.98   168.8 1694.89   186.6 1695.68
   190.9 1695.29   199.9 1693.11   207.3 1692.29   213.9 1691.29   221.8 1691.52
   227.1  1692.5   233.5 1694.06   246.7 1695.09   268.4 1695.26   280.8 1696.63
     303 1695.99   318.7  1696.7   329.2 1700.16   334.9 1702.58   341.4 1707.09
   350.3 1714.44   360.9 1721.36   368.9 1724.22     382 1725.55   389.8 1730.32
#Mann= 5, -1 ,  0
       0     0.1       0   207.3   0.045       0   227.1     0.1       0
   262.4    0.06       0  387.69     0.1       0
#XS Ineff= 2 , 0
        136.0483 1715.37
Permanent Ineff=
       T       F
Bank Sta=207.3,227.1
XS Rating Curve= 0 ,0
Exp/Cntr(USF)=0,0
Exp/Cntr=0.3,0.1