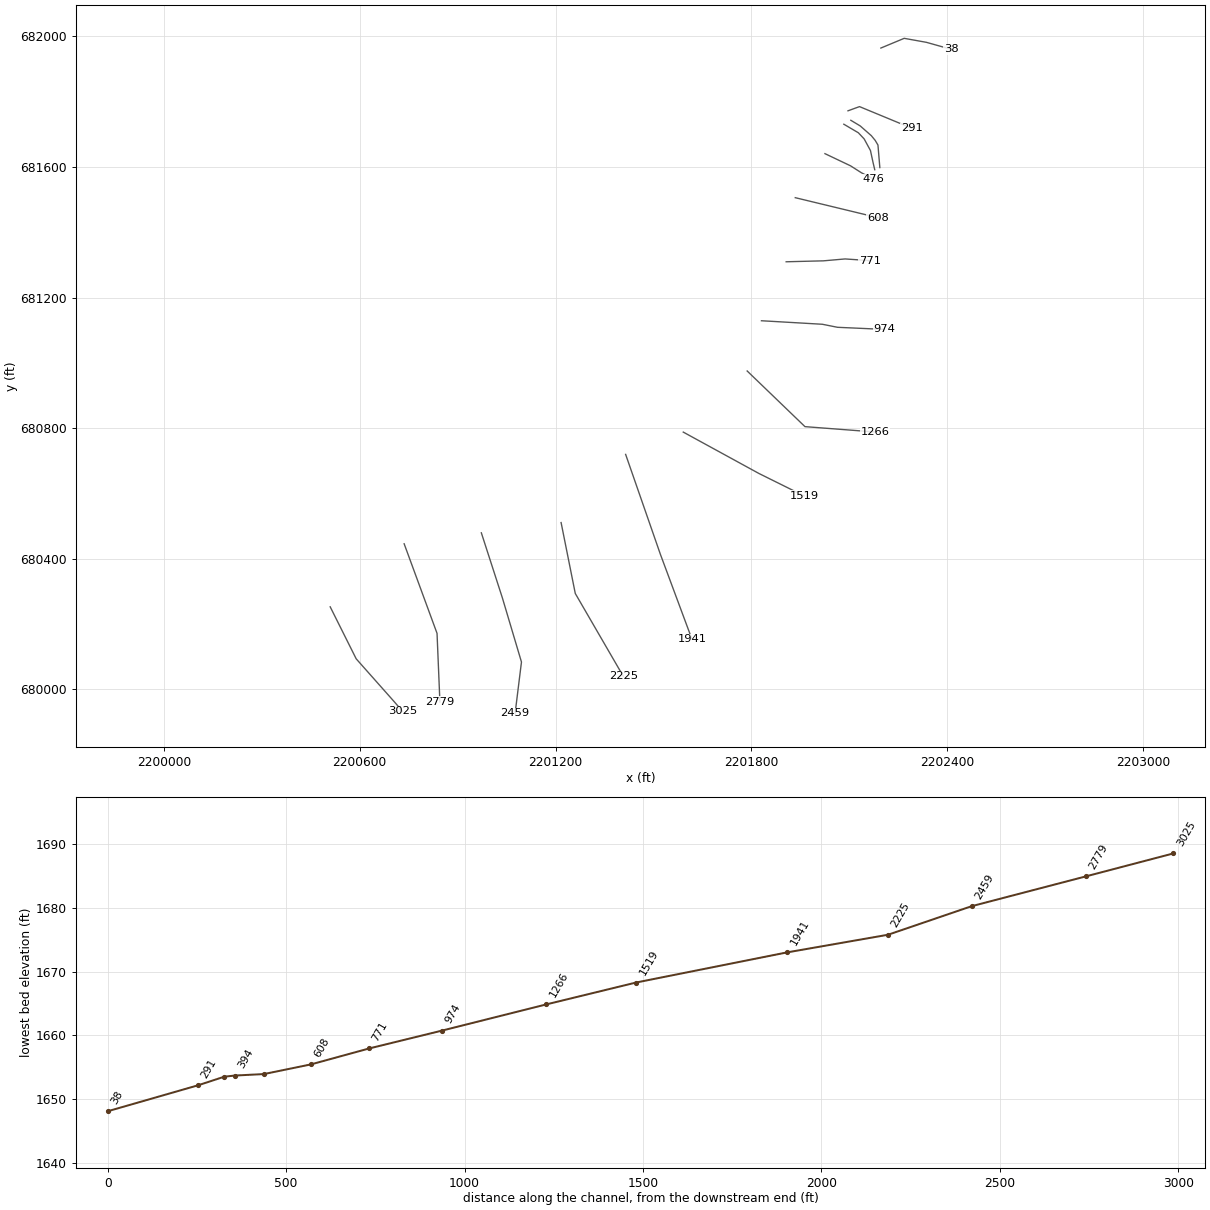
HEC-RAS study RFTENMILCK.prj: RFTENMILCK

--- RFTENMILCK.g01 (geometry) --- (continued)

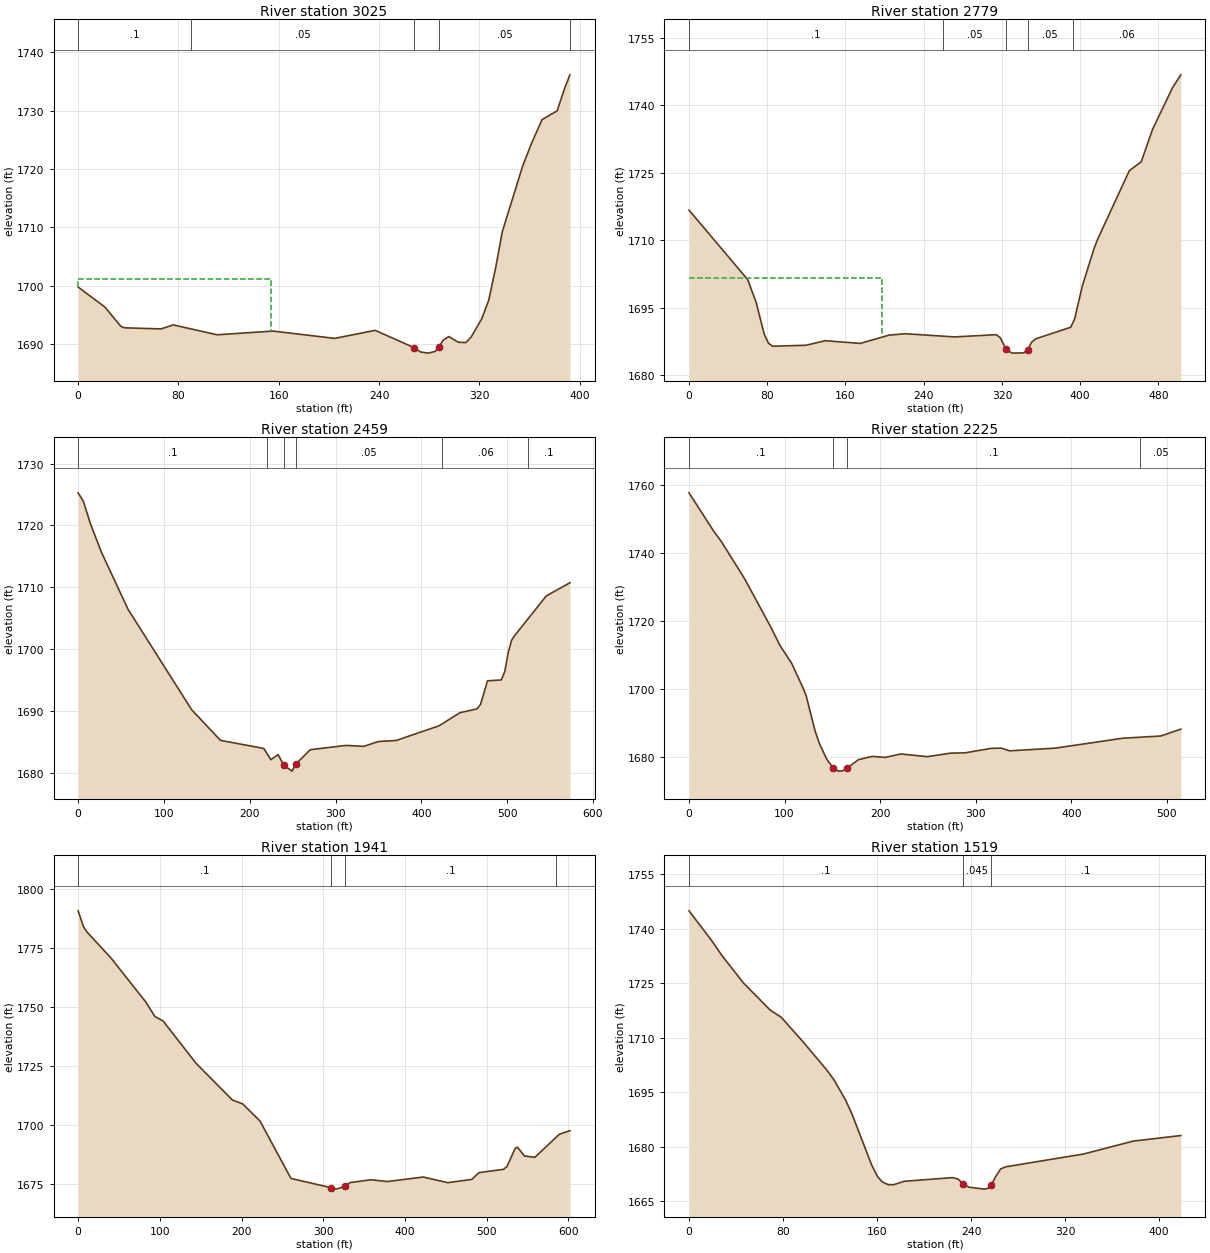
Type RM Length L Ch R = 1 ,3025    ,254.5,245.5,233
XS GIS Cut Line= 4
2200509.51770196680252.2765532362200589.19690206680092.918153049
 2200705.2727738679962.0868738832200730.84881333679932.576059034
#Sta/Elev= 30
       0 1699.81    21.4 1696.37    34.1 1693.07    37.1 1692.83    66.1 1692.64
    75.8 1693.33   110.8 1691.64   155.5 1692.27   204.6 1691.02   236.8  1692.4
   267.9 1689.43   273.1 1688.69   279.1  1688.5   284.8  1688.8   287.8 1689.62
   291.1 1690.73   295.5 1691.33   303.2 1690.36   309.2 1690.31   313.3 1691.25
   321.8 1694.38   327.4 1697.58   332.9 1703.13   338.2 1709.28   354.3 1720.43
   361.4 1724.35   369.9 1728.45   381.9 1729.94     388 1733.88   392.1 1736.11
#Mann= 5, -1 ,  0
       0     0.1       0      90    0.05       0   267.9   0.045       0
   287.8    0.05       0  392.12    0.06       0
#XS Ineff= 2 , 0
          153.46 1701.26
Permanent Ineff=
       T       F
Bank Sta=267.9,287.8
XS Rating Curve= 0 ,0
Exp/Cntr(USF)=0,0
Exp/Cntr=0.3,0.1

Type RM Length L Ch R = 1 ,2779    ,312.7,320.3,323.2
XS GIS Cut Line= 3
2200736.12321742 680445.46301622 2200836.9214739680171.000293752
2200845.70739957679960.662834258
#Sta/Elev= 30
       0 1716.68      60 1701.24    68.5  1696.3      77 1689.05    81.3  1687.1
    85.5 1686.43   119.6 1686.65   139.4 1687.66     175 1687.06   204.8 1688.91
   221.5 1689.21   271.4  1688.5   314.2    1689   318.2 1688.34   324.3 1685.77
   330.2  1684.9   342.3 1684.96   346.3 1685.64   350.3 1687.31   354.3 1688.06
   390.3 1690.65   394.3 1692.48   402.3 1699.91   414.3 1708.24   418.3 1710.42
   450.3 1725.46   462.4  1727.4     474 1734.62   494.4 1743.87   502.9 1746.74
#Mann= 5, -1 ,  0
       0     0.1       0     260    0.05       0   324.3   0.045       0
   346.3    0.05       0  392.39    0.06       0
#XS Ineff= 2 , 0
          197.41 1701.55
Permanent Ineff=
       T       F
Bank Sta=324.3,346.3
XS Rating Curve= 0 ,0
Exp/Cntr(USF)=0,0
Exp/Cntr=0.3,0.1

Type RM Length L Ch R = 1 ,2459    ,235.2,234.2,232.5
XS GIS Cut Line= 4
 2200972.6848122680479.0278214692201037.15491526  680279.6202934
2201095.62779943680083.2113747772201076.13683804679925.784378933
#Sta/Elev= 30
       0 1725.27     6.1 1723.88    14.6 1720.16    27.2 1715.64    58.2 1706.41
   132.3 1690.16   165.9 1685.21   216.3  1683.9   224.6 1682.08     233 1682.91
   239.7 1681.17   249.3 1680.23   253.51681.339   270.5  1683.7   312.3 1684.39
   333.1 1684.24   349.8 1685.02   370.7 1685.19   420.6 1687.57   444.8 1689.68
   464.9 1690.31   468.9 1691.03     477 1694.84   493.1 1694.99   497.2 1696.38
   501.2 1699.47   505.2 1701.45   509.2 1702.26   545.5 1708.58   573.1 1710.72
#Mann= 6, -1 ,  0
       0     0.1       0  219.57    0.05       0   239.7   0.045       0
   253.5    0.05       0   424.5    0.06       0   524.5     0.1       0
Bank Sta=239.7,253.5
XS Rating Curve= 0 ,0
Exp/Cntr(USF)=0,0
Exp/Cntr=0.3,0.1

Type RM Length L Ch R = 1 ,2225    ,280.8,283.6,284.3
XS GIS Cut Line= 3
2201217.07148194680510.5132206372201260.55131888680293.114035901
2201407.48318167680039.731537829
#Sta/Elev= 30
       0 1757.83    25.8 1746.54      34  1743.4    58.2 1732.48    85.4 1718.35
    95.2 1712.81   107.4 1707.57   119.7 1700.06   122.7 1697.86   131.9 1687.64
   136.3    1684   144.1 1679.29   151.1 1676.64   156.4 1675.76   160.5 1675.82
   165.81676.723   177.1 1679.11   191.5  1680.1   205.3 1679.82   221.7 1680.82
   249.4 1680.03   274.1 1681.07   288.7 1681.15   316.6 1682.49   326.7 1682.54
   335.5 1681.74   383.5 1682.55   453.7 1685.46   493.6 1686.12   514.6 1688.14
#Mann= 4, -1 ,  0
       0     0.1       0   151.1   0.045       0   165.8     0.1       0
   471.7    0.05       0
Bank Sta=151.1,165.8
XS Rating Curve= 0 ,0
Exp/Cntr(USF)=0,0
Exp/Cntr=0.3,0.1

Type RM Length L Ch R = 1 ,1941    ,407.8,422.3,430.4
XS GIS Cut Line= 3
2201414.83803906680719.3944074682201521.45526375680412.869886461
2201618.07712364 680152.99040126
#Sta/Elev= 30
       0 1790.81     6.6 1784.05    10.8 1781.87    40.5 1770.72    82.8 1752.21
    93.9 1746.09     104 1744.17   144.2 1726.31   188.7 1710.73   201.4 1709.07
   222.6  1701.8   260.4 1677.52   309.41673.601   315.7 1672.99   326.4 1674.17
   332.7 1675.75   358.3 1676.96   378.3  1676.2   422.4 1678.11   452.2 1675.73
   481.6 1677.11   490.6 1679.98   520.5 1681.36   524.8 1682.58   534.8 1690.27
   537.6 1690.74   546.1 1687.03   558.9 1686.45   588.8 1696.22   601.8 1697.74
#Mann= 4, -1 ,  0
       0     0.1       0   309.4   0.045       0   326.4     0.1       0
  584.54    0.06       0
Bank Sta=309.4,326.4
XS Rating Curve= 0 ,0
Exp/Cntr(USF)=0,0
Exp/Cntr=0.3,0.1

Type RM Length L Ch R = 1 ,1519    ,254.7,252.6,246.9
XS GIS Cut Line= 3
2201591.42281746 680787.696067042201822.98210235680661.088112711
2201961.43641498680592.416254442
#Sta/Elev= 30
       0 1744.96    19.1 1736.85    28.2 1732.57    46.4 1725.06    69.2 1717.58
    78.4 1715.66    96.6 1709.04   117.4 1701.03   123.3 1698.42   133.1 1692.91
   138.7 1688.96   155.3 1675.02   160.4 1671.75   164.5 1670.26   169.5 1669.52
   174.1  1669.5   183.2 1670.44   224.2 1671.45   228.8 1671.09   233.4 1669.71
   238.2 1668.81   251.6 1668.28   255.9 1668.66   257.1 1669.28   260.7  1671.6
   265.2 1673.86   269.7 1674.44   335.7 1677.95   378.1 1681.52   418.5 1683.04
#Mann= 3, -1 ,  0
       0     0.1       0   233.4   0.045       0   257.1     0.1       0
Bank Sta=233.4,257.1
XS Rating Curve= 0 ,0
Exp/Cntr(USF)=0,0
Exp/Cntr=0.3,0.1

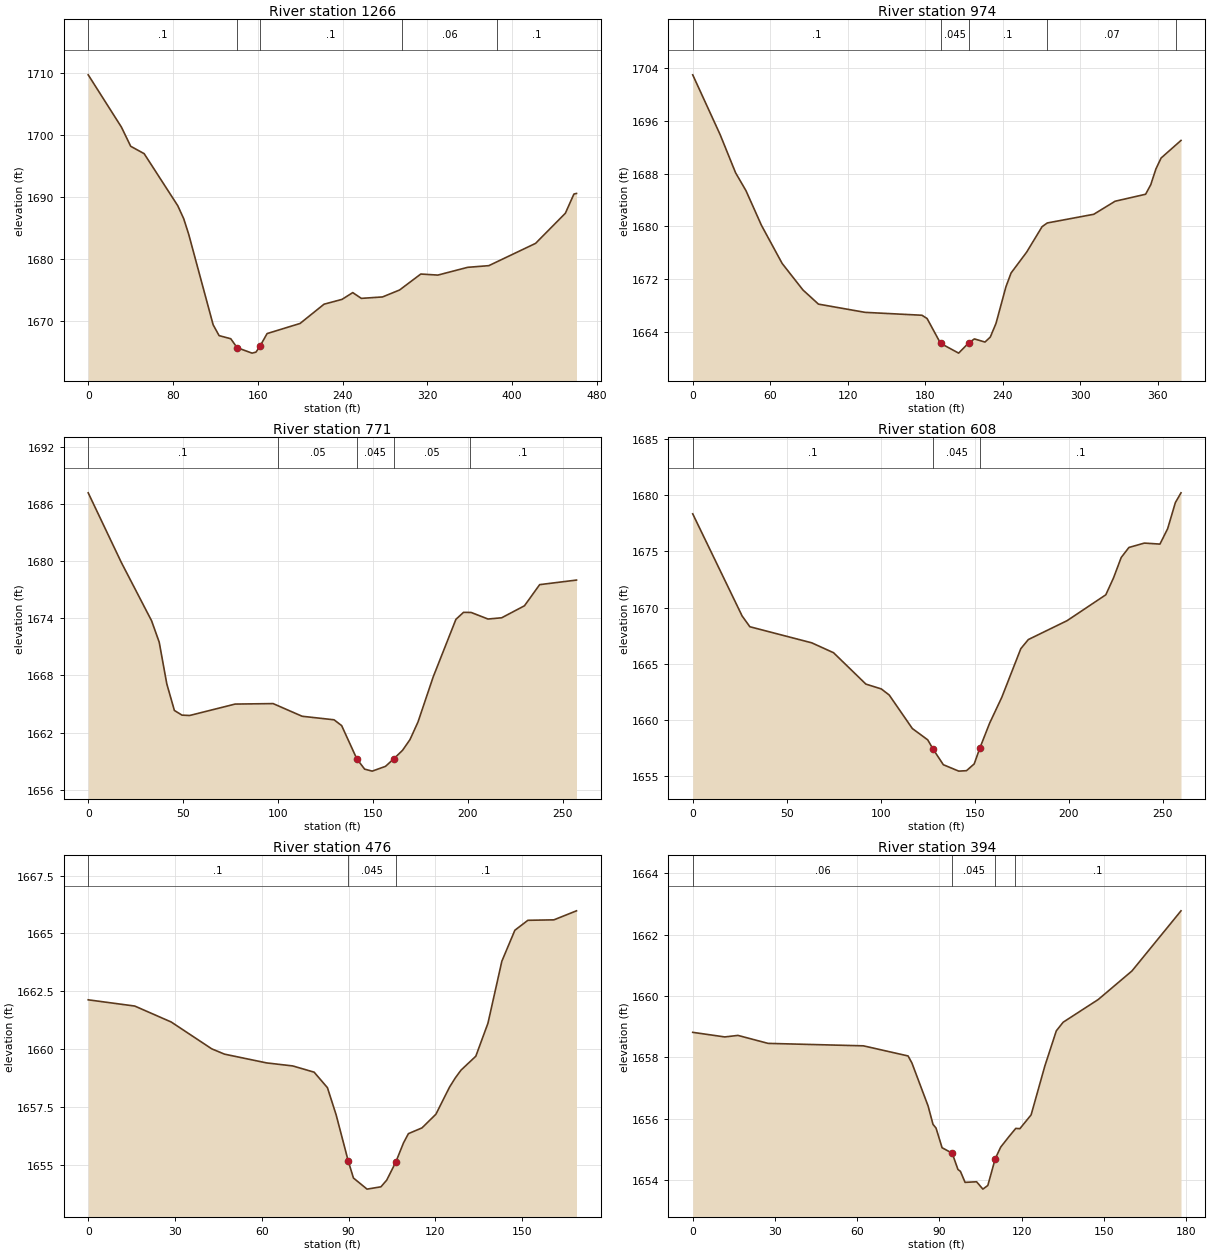
Type RM Length L Ch R = 1 ,1266    ,279.9,292.1,298.6
XS GIS Cut Line= 3
2201787.28999691680974.962632959  2201964.354886680804.455702718
2202178.58154195 680788.06080558
#Sta/Elev= 30
       0 1709.67    31.4 1701.23    40.1 1698.16    52.8 1696.97    84.5 1688.59
    90.1  1686.5    94.8    1684   117.9  1669.4   123.5 1667.66   134.5 1667.16
   140.5 1665.72   154.6 1664.84   158.3    1665   162.3 1666.03   168.8 1667.99
   199.9 1669.62   222.5 1672.72   239.5  1673.5   249.6 1674.59   257.7 1673.66
   277.7 1673.89   293.8 1675.01   313.8 1677.58   329.9 1677.41     358 1678.66
     378 1678.93   422.1 1682.52   450.2 1687.37   458.3 1690.47   460.7 1690.56
#Mann= 5, -1 ,  0
       0     0.1       0   140.5   0.045       0   162.3     0.1       0
  295.81    0.06       0  385.81     0.1       0
Bank Sta=140.5,162.3
XS Rating Curve= 0 ,0
Exp/Cntr(USF)=0,0
Exp/Cntr=0.3,0.1

Type RM Length L Ch R = 1 ,974     ,199.6,203.7,208.1
XS GIS Cut Line= 4
2201831.05956178681128.928851399   2202017.50889681118.172159387
2202064.12122206681108.8496929762202207.54378222681102.395677768
#Sta/Elev= 30
       0 1702.99    21.2 1693.92    33.2 1688.11    41.2 1685.41    53.2 1680.14
    69.2 1674.36    85.3 1670.33    97.3 1668.18   133.4 1666.93   177.4 1666.49
   181.4 1665.99   191.8 1662.23   205.8 1660.74   213.51662.273     218  1662.9
   226.2 1662.42   230.3 1663.18   234.7 1665.24   242.4 1670.81   246.4 1672.91
   258.4 1676.06   270.4 1679.94   274.4  1680.5   310.4 1681.82   326.9  1683.8
   350.5 1684.86   354.5 1686.31   358.5 1688.71   362.5 1690.36   377.9 1693.03
#Mann= 5, -1 ,  0
       0     0.1       0   191.8   0.045       0   213.5     0.1       0
  274.29    0.07       0  374.29    0.06       0
Bank Sta=191.8,213.5
XS Rating Curve= 0 ,0
Exp/Cntr(USF)=0,0
Exp/Cntr=0.3,0.1

Type RM Length L Ch R = 1 ,771     ,166.7,162.7,156.2
XS GIS Cut Line= 4
2201906.77865604681309.6278283622202021.20834567681312.532135206
2202087.42654169681318.3407488932202163.51938099681313.112996574
#Sta/Elev= 30
       0 1687.17    17.4 1679.88    33.4 1673.73    37.4 1671.49    41.4 1667.11
    45.4 1664.32    49.4 1663.83    53.4 1663.79    77.4 1664.99    97.4 1665.04
   112.7 1663.71   129.5 1663.34   133.5 1662.73   141.5 1659.24   145.6 1658.16
   149.6 1657.95   156.6 1658.45     161 1659.25   165.6 1660.14   169.5 1661.26
   173.7  1663.1   181.7 1667.83   193.7 1673.89   197.7 1674.62   201.7 1674.61
   210.6 1673.92   217.8 1674.05   229.8 1675.31   237.8 1677.53   257.2 1678.01
#Mann= 5, -1 ,  0
       0     0.1       0     100    0.05       0   141.5   0.045       0
     161    0.05       0  200.94     0.1       0
Bank Sta=141.5,161
XS Rating Curve= 0 ,0
Exp/Cntr(USF)=0,0
Exp/Cntr=0.3,0.1

Type RM Length L Ch R = 1 ,608     ,136.4,132.3,127.3
XS GIS Cut Line= 2
2201934.64444188681506.0380304492202187.10697259  681445.0564264
#Sta/Elev= 30
       0 1678.34    26.3 1669.25    30.4  1668.3    63.3 1666.87    74.9 1665.99
    92.1  1663.2   100.3 1662.77   104.5 1662.23   116.8 1659.25     125 1658.24
   127.9  1657.4   133.3 1656.03   141.5 1655.46   145.6  1655.5   149.7  1656.1
   152.8 1657.55   157.9 1659.72   164.4 1662.03   174.5 1666.35   178.5 1667.16
   199.1 1668.84   219.7 1671.14   223.8 1672.64   227.9 1674.46     232 1675.35
   240.2 1675.74   248.5 1675.65   252.6 1677.02   256.7 1679.34   259.7 1680.21
#Mann= 3, -1 ,  0
       0     0.1       0   127.9   0.045       0   152.8     0.1       0
Bank Sta=127.9,152.8
XS Rating Curve= 0 ,0
Exp/Cntr(USF)=0,0
Exp/Cntr=0.3,0.1

Type RM Length L Ch R = 1 ,476     ,88.4,81.1,73.8
XS GIS Cut Line= 4
2202025.65815798681640.9297488332202103.99602647 681603.66633031
2202137.87186149681582.0704854842202175.13528002681563.015328284
#Sta/Elev= 30
       0 1662.13    16.1 1661.86    28.7 1661.17    42.7 1660.01    47.1 1659.78
    61.7  1659.4    70.7 1659.27    78.1    1659    82.7 1658.33    85.7 1657.16
    89.91655.154    91.7 1654.42    96.4 1653.94   101.2 1654.04   103.2 1654.33
   106.3  1655.1     109 1655.94   110.7 1656.34   115.4 1656.59   120.2 1657.18
   124.9 1658.35   126.9 1658.75   128.9 1659.09     134 1659.69   138.2 1661.12
     143  1663.8   147.5 1665.14     152 1665.57     161 1665.59   168.8 1665.98
#Mann= 3, -1 ,  0
       0     0.1       0    89.9   0.045       0   106.3     0.1       0
Bank Sta=89.9,106.3
XS Rating Curve= 0 ,0
Exp/Cntr(USF)=0,0
Exp/Cntr=0.3,0.1

Type RM Length L Ch R = 1 ,394     ,26.8,29.8,31.3
XS GIS Cut Line= 6
2202083.49202031681731.1243782972202127.92791501681704.985616707
2202145.70227289681686.1657083612202165.04495647681650.616992598
2202172.80450923681614.6929242192202178.18804857 681591.74884207
#Sta/Elev= 30
       0 1658.82    11.7 1658.67    16.5 1658.72    27.5 1658.46    62.3 1658.38
    78.6 1658.05      80 1657.82    85.9 1656.42    87.7 1655.82    88.8  1655.7
      91 1655.06    94.7 1654.88    96.8 1654.35    97.7 1654.29    99.4 1653.93
   103.6 1653.95   105.9 1653.71   107.7 1653.83   110.4  1654.7   112.4 1655.08
   115.4 1655.42   117.9 1655.69   119.4 1655.68   123.5 1656.13   128.5 1657.72
   132.7 1658.87   135.2 1659.15     148 1659.89   160.3 1660.82   178.2 1662.78
#Mann= 4, -1 ,  0
       0    0.06       0    94.7   0.045       0   110.4    0.06       0
  117.44     0.1       0
Bank Sta=94.7,110.4
XS Rating Curve= 0 ,0
Exp/Cntr(USF)=0,0
Exp/Cntr=0.3,0.1

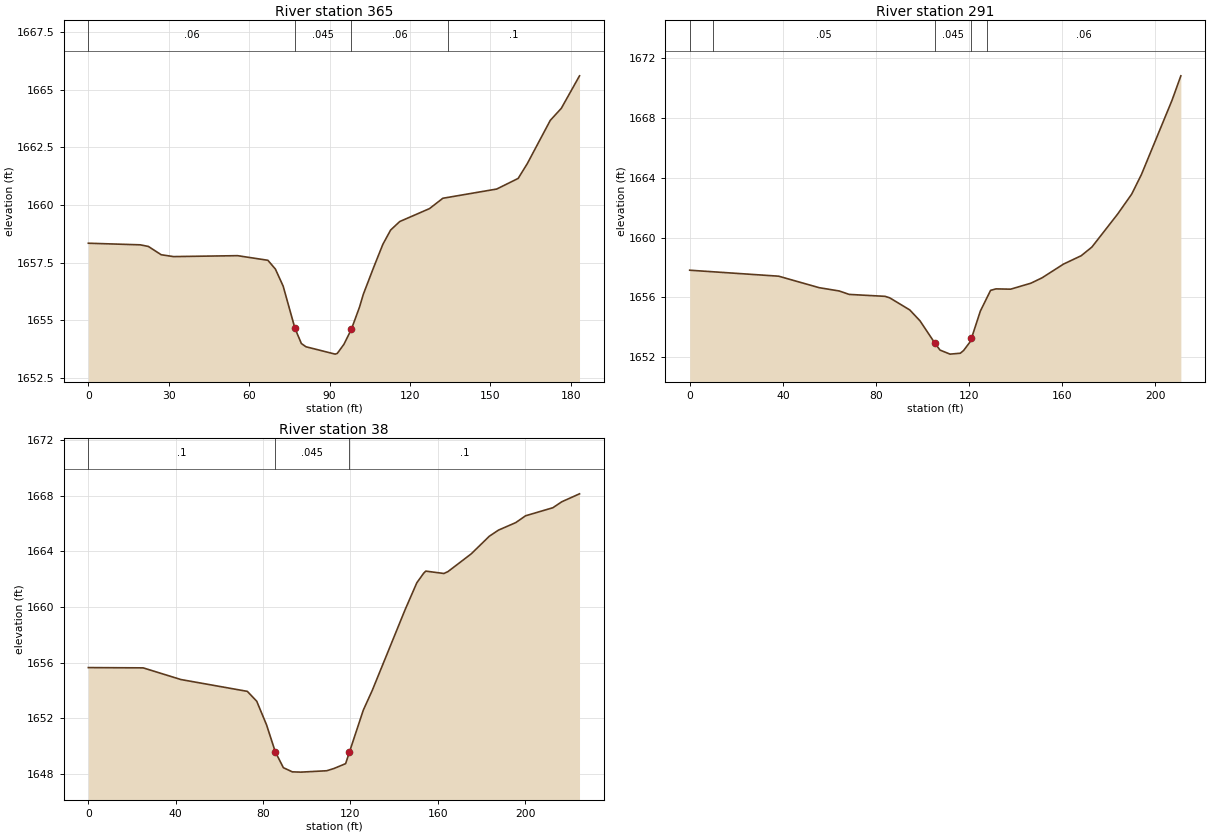
Type RM Length L Ch R = 1 ,365     ,66.3,73.1,81.1
XS GIS Cut Line= 6
2202104.92580481681743.1482086292202133.67844256681725.896625979
2202167.65883263681696.0984377662202179.68266296681681.460731275
2202188.04706667681667.3458000162202193.79759422681598.339469417
#Sta/Elev= 30
       0 1658.34    19.4 1658.27    22.4  1658.2    27.2 1657.84    31.8 1657.76
    55.7  1657.8      67  1657.6    69.8 1657.22    72.7 1656.48    77.1 1654.65
    79.5 1653.99    81.2 1653.85    92.1 1653.53    92.9 1653.56    95.4 1653.96
    98.2 1654.62   101.2 1655.57   102.6 1656.12   106.5  1657.3   109.9 1658.29
   112.8 1658.91   116.2 1659.28   127.3 1659.84   132.3 1660.29   152.4 1660.69
   160.4 1661.15   163.8 1661.79   172.4 1663.67   176.5 1664.19   183.3  1665.6
#Mann= 4, -1 ,  0
       0    0.06       0    77.1   0.045       0    98.2    0.06       0
  134.08     0.1       0
Bank Sta=77.1,98.2
XS Rating Curve= 0 ,0
Exp/Cntr(USF)=0,0
Exp/Cntr=0.3,0.1

Type RM Length L Ch R = 1 ,291     ,249.8,253.5,259.2
XS GIS Cut Line= 3
2202096.24758201681772.2656282052202131.49974774681785.101792274
2202291.66604698681718.831376071
#Sta/Elev= 30
       0 1657.81    38.2 1657.41    55.6 1656.64    64.2 1656.42    68.5 1656.19
    83.9 1656.06    85.9 1655.96    94.5 1655.15    98.9 1654.42   105.3 1652.92
   107.5 1652.46   111.8 1652.19   116.2 1652.25   117.6 1652.43   120.5 1653.03
     121 1653.25   124.8 1655.07   129.2 1656.46   131.5 1656.56   137.8 1656.54
   146.5 1656.94   151.3  1657.3   160.5 1658.22   168.1 1658.78   172.7 1659.36
   183.8 1661.58   189.8 1662.91     194 1664.23   207.1 1669.19   210.9 1670.83
#Mann= 5, -1 ,  0
       0    0.06       0      10    0.05       0   105.3   0.045       0
     121    0.05       0  127.52    0.06       0
Bank Sta=105.3,121
XS Rating Curve= 0 ,0
Exp/Cntr(USF)=0,0
Exp/Cntr=0.3,0.1

Type RM Length L Ch R = 1 ,38      ,,,
XS GIS Cut Line= 4
2202196.98743295681964.5847326292202268.45080078681994.326829172
2202336.45918127681982.088477645 2202411.9040199681960.918565146
#Sta/Elev= 30
       0 1655.64    25.1 1655.62    42.4 1654.78    72.8 1653.93    77.1 1653.22
    81.6 1651.52    85.6 1649.58    89.3 1648.44    93.4 1648.14    97.4 1648.12
   109.2 1648.22   112.6 1648.39   117.8 1648.73   119.5 1649.54   125.9 1652.58
     130    1654     145 1659.79   150.4 1661.74   153.5 1662.42   154.5 1662.58
   162.8 1662.41   164.7 1662.55   175.3 1663.82   183.6 1665.09   187.8 1665.53
   195.7 1666.07   200.2 1666.56   212.7 1667.14   216.8 1667.57   224.9 1668.14
#Mann= 3, -1 ,  0
       0     0.1       0    85.6   0.045       0   119.5     0.1       0
Bank Sta=85.6,119.5
XS Rating Curve= 0 ,0
Exp/Cntr(USF)=0,0
Exp/Cntr=0.3,0.1
LCMann Table=0

Chan Stop Cuts=-1
Use User Specified Reach Order=0
Composite Channel Slope=5