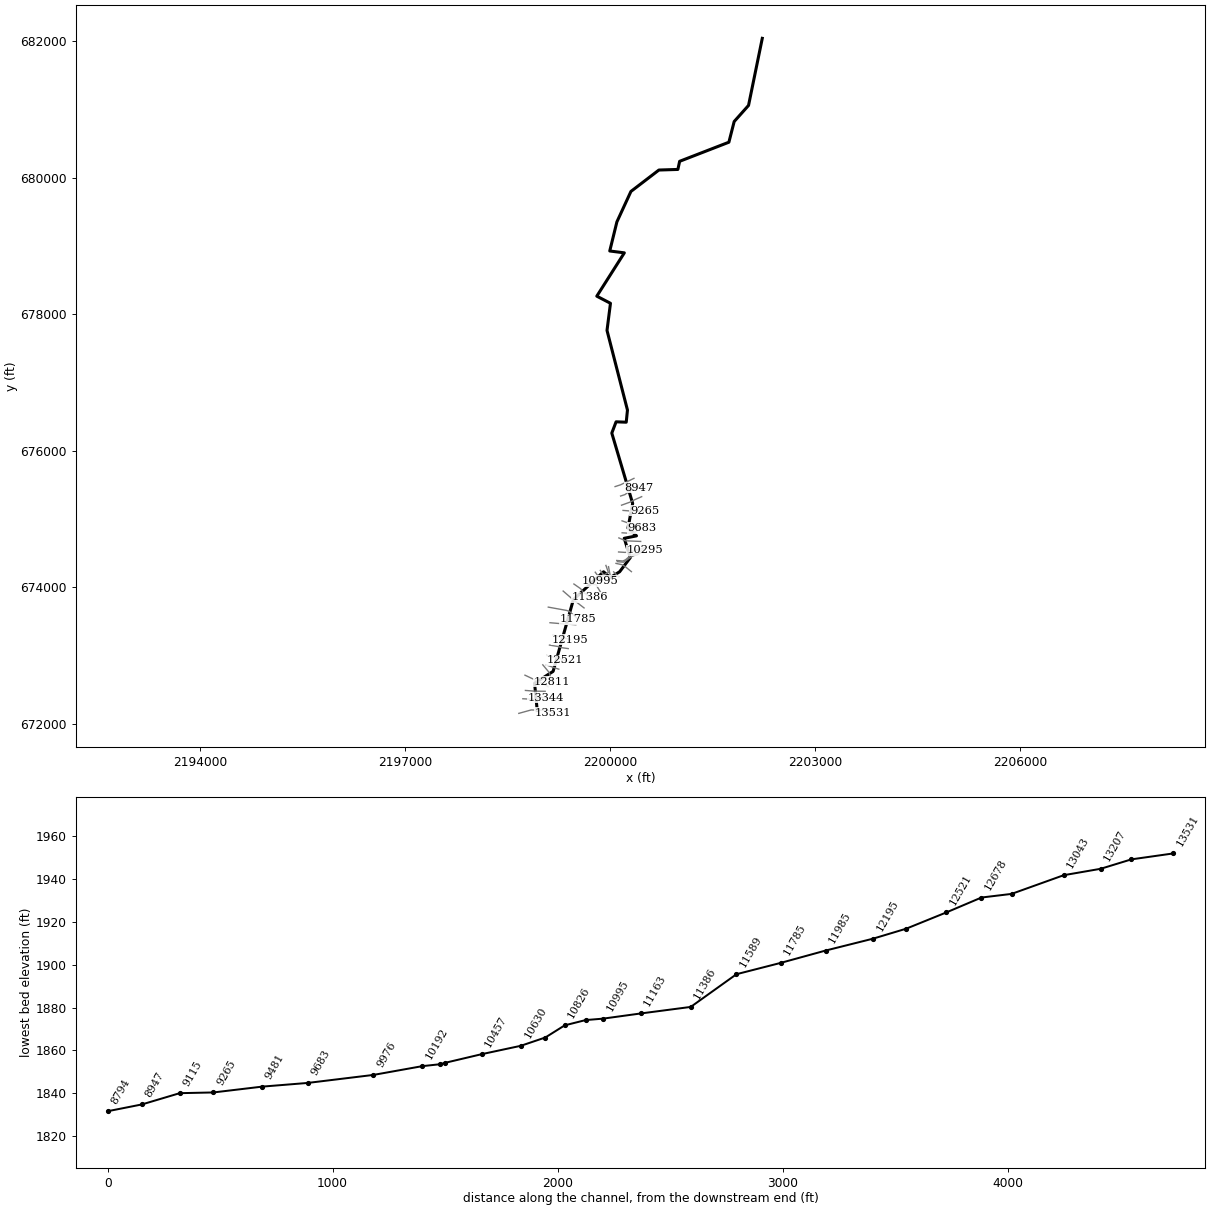
--- RFTENMILCK.prj (project) ---

Proj Title=RFTENMILCK
Current Plan=p01
Default Exp/Contr=0,0
English Units
Geom File=g01
Flow File=f01
Plan File=p01
BEGIN DESCRIPTION:
-------- MODELED AS PART OF WVEMD CTP PROGRAM, 2023----------
Stream Name: Right Fork Tenmile Creek
Flood Zone:  AFH
Upshur County, WV
HEC-RAS Version: RAS 6.3
Vertical Datum: NAVD88
Projection: NAD 1983 StatePlane West Virginia S FIPS 4702 (US Feet)
Terrain: 1-meter LIDAR (FEMA Region III 3DEP collected 2016-2018)
Land Use: 2019 NLCD
Hydrologic Method:
WV SIR2010-5033 regression equations
Additional Model Notes:
Boundary condition is KWSEL due to this model being the dominant flow path
END DESCRIPTION:
DSS Export Rating Curves= 0
DSS Export Rating Curve Sorted= 0
DSS Export Volume Flow Curves= 0
DXF OffsetX= 0
DXF OffsetY= 0
DXF ScaleX= 0
DXF ScaleY= 0

--- RFTENMILCK.p01 (plan) ---

Plan Title=Floodplain
Program Version=6.31
Short Identifier=Floodplain
Geom File=g01
Flow File=f01
Subcritical Flow
K Sum by GR= 0
Std Step Tol= 0.01
Critical Tol= 0.01
Num of Std Step Trials= 20
Max Error Tol= 0.3
Flow Tol Ratio= 0.001
Split Flow NTrial= 30
Split Flow Tol= 0.02
Split Flow Ratio= 0.02
Log Output Level= 0
Friction Slope Method= 1
Unsteady Friction Slope Method= 2
Unsteady Bridges Friction Slope Method= 1
Parabolic Critical Depth
Global Vel Dist= 0 , 0 , 0
Global Log Level= 0
CheckData=True
Encroach Param=-1 ,0,0, 0
Mapping Interval=1HOUR
Computation Time Step Use Courant=        0
Computation Time Step Use Time Series=    0
Computation Time Step Count To Double=0
Computation Time Step Max Doubling=0
Computation Time Step Max Halving=0
Computation Time Step Residence Courant=0
Run HTab= 0
Run UNet= 0
Run Sediment= 0
Run PostProcess= 0
Run WQNet= 0
Run RASMapper=-1
UNET Theta= 0
UNET Theta Warmup= 0
UNET ZTol= 0
UNET ZSATol= 0
UNET MxIter= 0
UNET Max Iter WO Improvement= 0
UNET MaxInSteps= 0
UNET DtIC= 0
UNET DtMin= 0
UNET MaxCRTS= 0
UNET WFStab= 0
UNET SFStab= 0
UNET WFX= 1
UNET SFX= 1
UNET Gravity=32.17405
UNET 1D Methodology=Finite Difference
UNET DSS MLevel= 1
UNET Pardiso=0
UNET DZMax Abort= 0
UNET Use Existing IB Tables= 0
UNET Froude Reduction=False
UNET Froude Limit= 0
UNET Froude Power= 0
UNET D1 Cores= 0
UNET WindReference=Eulerian
UNET WindDragFormulation=Hsu (1988)
UNET D2 Coriolis=0
UNET D2 Cores= 0
UNET D2 Theta= 1
UNET D2 Theta Warmup= 1
UNET D2 Z Tol= 0.01
UNET D2 Volume Tol= 0.01
UNET D2 Max Iterations= 20
UNET D2 Equation= 0
UNET D2 RampUpFraction=0.1
UNET D2 TimeSlices= 1
UNET D2 Turbulence Formulation=Non-Conservative (original)
UNET D2 Eddy Viscosity=0.3
UNET D2 Transverse Eddy Viscosity=0.1
UNET D2 Smagorinsky Mixing=0
UNET D2 BCVolumeCheck=0
UNET D2 Cores=0
UNET D2 SolverType=PARDISO (Direct)
UNET D2 Minimum Iterations= 3
UNET D2 Maximum Iterations= 30
UNET D2 Restart Number= 10
UNET D2 Relaxation Coeff=1.3
UNET D2 SOR Precondition Iterations= 10
UNET D2 ILUT Maximum Fill= 8
UNET D2 ILUT Tolerance=1E-08
UNET D2 Convergence Tolerance=0.00001
UNET D1D2 MaxIter= 0
UNET D1D2 ZTol=0.01
UNET D1D2 QTol=0.1
UNET D1D2 MinQTol=1
Write IC File= 0
Write IC File at Fixed DateTime=0
Write IC File at Sim End=0
Echo Input=False
Echo Parameters=False
Echo Output=False
Write Detailed= 0
HDF Write Warmup=0
HDF Write Time Slices=0
HDF Flush=0
HDF Compression= 1
HDF Chunk Size= 1
HDF Spatial Parts= 1
HDF Use Max Rows=0
HDF Fixed Rows= 1
Calibration Method= 0
Calibration Iterations= 20
Calibration Max Change=0.05
Calibration Tolerance=0.2
Calibration Maximum=1.5
Calibration Minimum=0.5
Calibration Optimization Method= 1
WQ AD Non Conservative
WQ ULTIMATE=-1
WQ Max Comp Step=1HOUR
WQ Output Interval=15MIN
WQ Output Selected Increments= 0
WQ Create Restart=0
WQ Fixed Restart=0
WQ System Summary=0
WQ Write To DSS=0
Sorting and Armoring Iterations= 10
XS Update Threshold= 0.02
Bed Roughness Predictor= 0
Hydraulics Update Threshold= 0.02
Energy Slope Method= 1
Volume Change Method= 1
Sediment Retention Method= 0
Sediment TS Multiplier= 1
Warm Up Method= 0
XS Weighting Method= 0
Number of US Weighted Cross Sections= 1
Number of DS Weighted Cross Sections= 1
Upstream XS Weight=0
Main XS Weight=1
Downstream XS Weight=0
Number of DS XS's Weighted with US Boundary= 1
Upstream Boundary Weight= 1
Weight of XSs Associated with US Boundary= 0
Number of US XS's Weighted with DS Boundary= 1
Downstream Boundary Weight= 0.5
Weight of XSs Associated with DS Boundary= 0.5
Percentile Method= 0
Sediment Output Level= 3
Mass or Volume Output= 0
Output Increment Type= 1
Profile and TS Output Increment= 1
Transport Output Increment 1
XS Output Flag= 0
XS Output Increment= 10
Read HDF5 Sediment Hotstart= 0
Sediment Hotstart Type= 0
Write Gradation File= 0
Read Gradation Hotstart= 0
Write HDF5 File= 1
Write Binary Output= 1
Write DSS Sediment File= 0
DSS Sediment Output Type= 1
SV Curve= 0
Specific Gage Flag= 0
Subcell Erosion Methods= 0
Subcell Deposition Methods= 0
Advection Scheme= 1
Matrix Solver= 0
Implicit Weighting Factor= 1
Maximum Outer Loop Convergence Iterations= 5
Convergence Maximum Absolute= 0.001
Convergence RMSE= 0.0001
Grain Fractions Max Abs Error= 0.001
Max Subgrid Regions= 1
Max Subgrid Length Scale= 3.402823E+38
Initial Layer Thickness= 3.402823E+38
Min Layer Thickness= 3.402823E+38
Max Layer Thickness= 3.402823E+38
Number of Layers= 5

--- RFTENMILCK.f01 (steady flow) ---

Flow Title=Flows
Program Version=6.31
Number of Profiles= 1
Profile Names=01pct
River Rch & RM=RFTENMILCK,Main            ,13531
     346
River Rch & RM=RFTENMILCK,Main            ,10457
     739
River Rch & RM=RFTENMILCK,Main            ,6890
     839
River Rch & RM=RFTENMILCK,Main            ,1566
     985
River Rch & RM=RFTENMILCK,Main            ,0
    1590
Boundary for River Rch & Prof#=RFTENMILCK,Main            , 1
Up Type= 0
Dn Type= 1
Dn Known WS=1651.9
DSS Import GetInterval= 0
DSS Import GetPeak= 0
DSS Import FillOption= 0

--- RFTENMILCK.g01 (geometry) ---

Geom Title=Geometry
Program Version=6.31

River Reach=RFTENMILCK      ,Main
Reach XY= 30
2198934.28928664672195.1372379362198895.94500001672595.768999994
2199166.99900001672769.4989999982199463.72200002673819.920000002
     2199905.245674228.477000013     2200003.714674142.599000007
2200141.21500003674229.1060000212200297.11700003674435.916999996
     2200207.977674718.7610000072200387.94600001 674754.44600001
     2200262.749674869.1980000292200331.48600003675229.134000003
      2200026.12 676259.782000022200088.73299998      676424.956
2200237.36600003676419.2040000112200255.36600001676597.084000021
2199955.92400001677763.5740000012200006.51800001678161.084000021
     2199806.461678265.4190000152200209.66600001678900.188000008
2199996.12999998678927.3450000142200100.60899998        679353.5
2200306.01700002679799.5150000012200715.40300003680113.064999998
2200993.18200001680121.7929999982201019.02300003680240.808000013
2201739.98400003680520.6770000162201817.36300004680823.553000003
2202027.52200003681059.4660000062202228.74297744682042.242999708

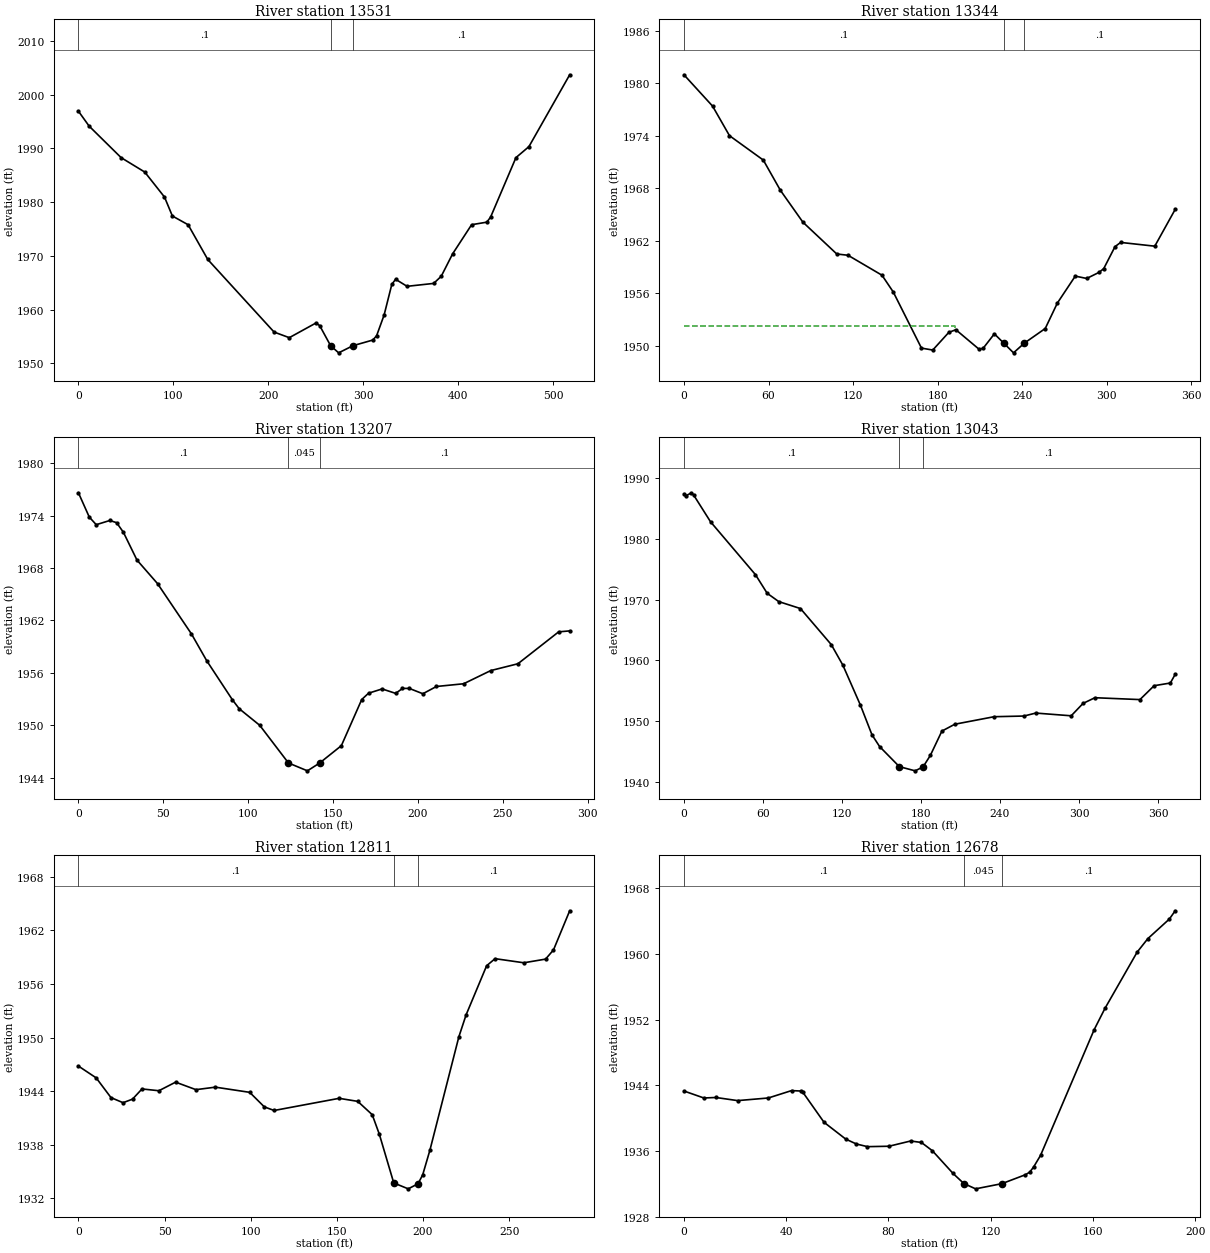
Type RM Length L Ch R = 1 ,13531   ,178,186.9,189.7
XS GIS Cut Line= 4
2198664.80843352672154.1417195562198845.57753463672204.355358753
2199096.64573061672198.7760655092199165.82896684672160.836871449
#Sta/Elev= 30
       0 1996.91    11.3 1994.13      45 1988.27    69.9 1985.59    90.7 1980.94
      99 1977.42   115.6 1975.79   136.3 1969.33   206.2 1955.83   222.2 1954.79
   250.2 1957.51   254.2 1957.04  265.72  1953.3   274.2 1951.97   289.3  1953.3
   310.2 1954.35   314.2 1955.15   322.1    1959   330.2 1964.69   334.2 1965.65
   346.3 1964.34   374.3 1964.88   382.3 1966.21   394.3 1970.38   414.3  1975.8
   430.3 1976.27   434.3 1977.21     461 1988.27   474.7 1990.32517.6469 2003.68
#Mann= 3 ,-1,0
       0      .1       0  265.72    .045       0   289.3      .1       0
Bank Sta=265.72,289.3
XS Rating Curve= 0 ,0
Exp/Cntr(USF)=0,0
Exp/Cntr=0.3,0.1

Type RM Length L Ch R = 1 ,13344   ,142.2,136.5,128.6
XS GIS Cut Line= 4
 2198723.9237147672368.3388343922198913.68788628672357.664599741
 2198979.5123333672393.2453819122199062.53415836672383.757173333
#Sta/Elev= 30
       0 1980.97    20.3 1977.39    32.3 1974.01    56.3 1971.22    68.4 1967.77
    84.4 1964.12   108.4 1960.49   116.4 1960.34   140.5 1958.06   148.5 1956.14
   168.5 1949.73   176.5 1949.51   187.9 1951.53   192.9 1951.83   209.3 1949.61
   212.2  1949.7   220.2 1951.36     227 1950.28   233.8 1949.19  241.39 1950.29
   256.3 1951.97   264.9 1954.88   277.6 1957.96   285.7 1957.69   294.5 1958.39
   297.8 1958.82   305.8 1961.33   309.8 1961.81     334 1961.38   348.5 1965.59
#Mann= 3 ,-1,0
       0      .1       0     227    .045       0  241.39      .1       0
#XS Ineff= 2 , 0
          192.32 1952.29
Permanent Ineff=
       F       F
Bank Sta=227,241.39
XS Rating Curve= 0 ,0
Exp/Cntr(USF)=0,0
Exp/Cntr=0.3,0.1

Type RM Length L Ch R = 1 ,13207   ,169.9,164.3,159.2
XS GIS Cut Line= 3
2198761.74944945672490.253806542     2198896.377      672479.494
2199050.71009895672477.913849979
#Sta/Elev= 30
       0  1976.6     6.4 1973.82    10.5 1972.95    18.5 1973.43    22.5 1973.18
    26.5 1972.08    34.5  1968.9    46.6 1966.21    66.6 1960.45    75.6 1957.38
    90.7 1952.92    94.7  1951.9   106.8    1950  123.72 1945.69   134.9 1944.79
   142.11945.684   154.9 1947.67   166.9 1952.95   170.9 1953.67   178.9 1954.16
   186.9 1953.65   190.9 1954.22   194.9 1954.22   202.9 1953.61   210.9 1954.44
   226.9 1954.75   242.9 1956.26   258.9 1957.04   282.9 1960.69   289.4  1960.8
#Mann= 3 ,-1,0
       0      .1       0  123.72    .045       0   142.1      .1       0
Bank Sta=123.72,142.1
XS Rating Curve= 0 ,0
Exp/Cntr=0.3,0.1

Type RM Length L Ch R = 1 ,13043   ,245,231.8,222.1
XS GIS Cut Line= 3
2198755.03132877672713.8168277872198967.50919568672613.480057299
2199090.47092422672550.523652286
#Sta/Elev= 30
       0 1987.43     1.3  1987.1     5.7 1987.62     7.3 1987.27    20.2 1982.84
    54.3 1974.13    63.2 1971.06      72 1969.69    88.5 1968.54   111.9  1962.6
   120.7 1959.21     134 1952.64   142.8 1947.74   148.6  1945.8   163.6 1942.49
   175.6  1941.8   181.6 1942.45   187.1 1944.33   195.9 1948.35   205.7 1949.48
   235.6 1950.72   258.2 1950.83   267.2 1951.32   294.1 1950.87   303.1 1952.91
   312.1 1953.85   346.3 1953.54   357.1 1955.83   369.4 1956.27   373.1 1957.71
#Mann= 3 ,-1,0
       0      .1       0   163.6    .045       0   181.6      .1       0
Bank Sta=163.6,181.6
XS Rating Curve= 0 ,0
Exp/Cntr(USF)=0,0
Exp/Cntr=0.3,0.1

Type RM Length L Ch R = 1 ,12811   ,120.5,133.7,143.1
XS GIS Cut Line= 3
 2199016.1036708672865.1089385832199108.17741313672754.443382897
2199150.67298652672619.874067183
#Sta/Elev= 30
       0 1946.81    10.3 1945.49    18.9 1943.28    25.9 1942.71    31.4 1943.11
    36.9 1944.25    46.7 1944.05    56.4 1945.01    68.2 1944.17    79.5 1944.45
    99.4 1943.87   107.9 1942.24   113.6 1941.84   151.3  1943.2   162.1 1942.86
   170.5 1941.37   174.6  1939.2     183 1933.73   191.4 1933.07   197.1 1933.64
   199.8 1934.64     204 1937.41   220.8  1950.1     225 1952.55   236.9 1958.04
   241.8 1958.83   258.5 1958.37   271.1 1958.78   275.7 1959.81   285.1 1964.19
#Mann= 3 ,-1,0
       0      .1       0     183    .045       0   197.1      .1       0
Bank Sta=183,197.1
XS Rating Curve= 0 ,0
Exp/Cntr(USF)=0,0
Exp/Cntr=0.3,0.1

Type RM Length L Ch R = 1 ,12678   ,154.5,156.2,156.9
XS GIS Cut Line= 3
2199068.34475934672863.3142053262199204.31859714672816.264434462
2199250.42737258672801.679005495
#Sta/Elev= 30
       0  1943.3     7.8 1942.45    12.5 1942.51      21 1942.13      33 1942.45
    42.1 1943.35    45.6  1943.3    46.4  1943.2    54.8 1939.49    63.3 1937.44
    67.5 1936.84    71.8 1936.52    80.2 1936.57    88.7 1937.21    92.9 1937.03
    97.2 1936.02   105.3 1933.25   109.51932.027   114.1 1931.38   124.41932.012
   133.6  1933.1   135.3 1933.42   136.8 1934.04   139.5 1935.45   160.5 1950.78
   164.7 1953.36   177.3 1960.22   181.5 1961.87   189.9 1964.25   192.2 1965.26
#Mann= 3 ,-1,0
       0      .1       0   109.5    .045       0   124.4      .1       0
Bank Sta=109.5,124.4
XS Rating Curve= 0 ,0
Exp/Cntr(USF)=0,0
Exp/Cntr=0.3,0.1

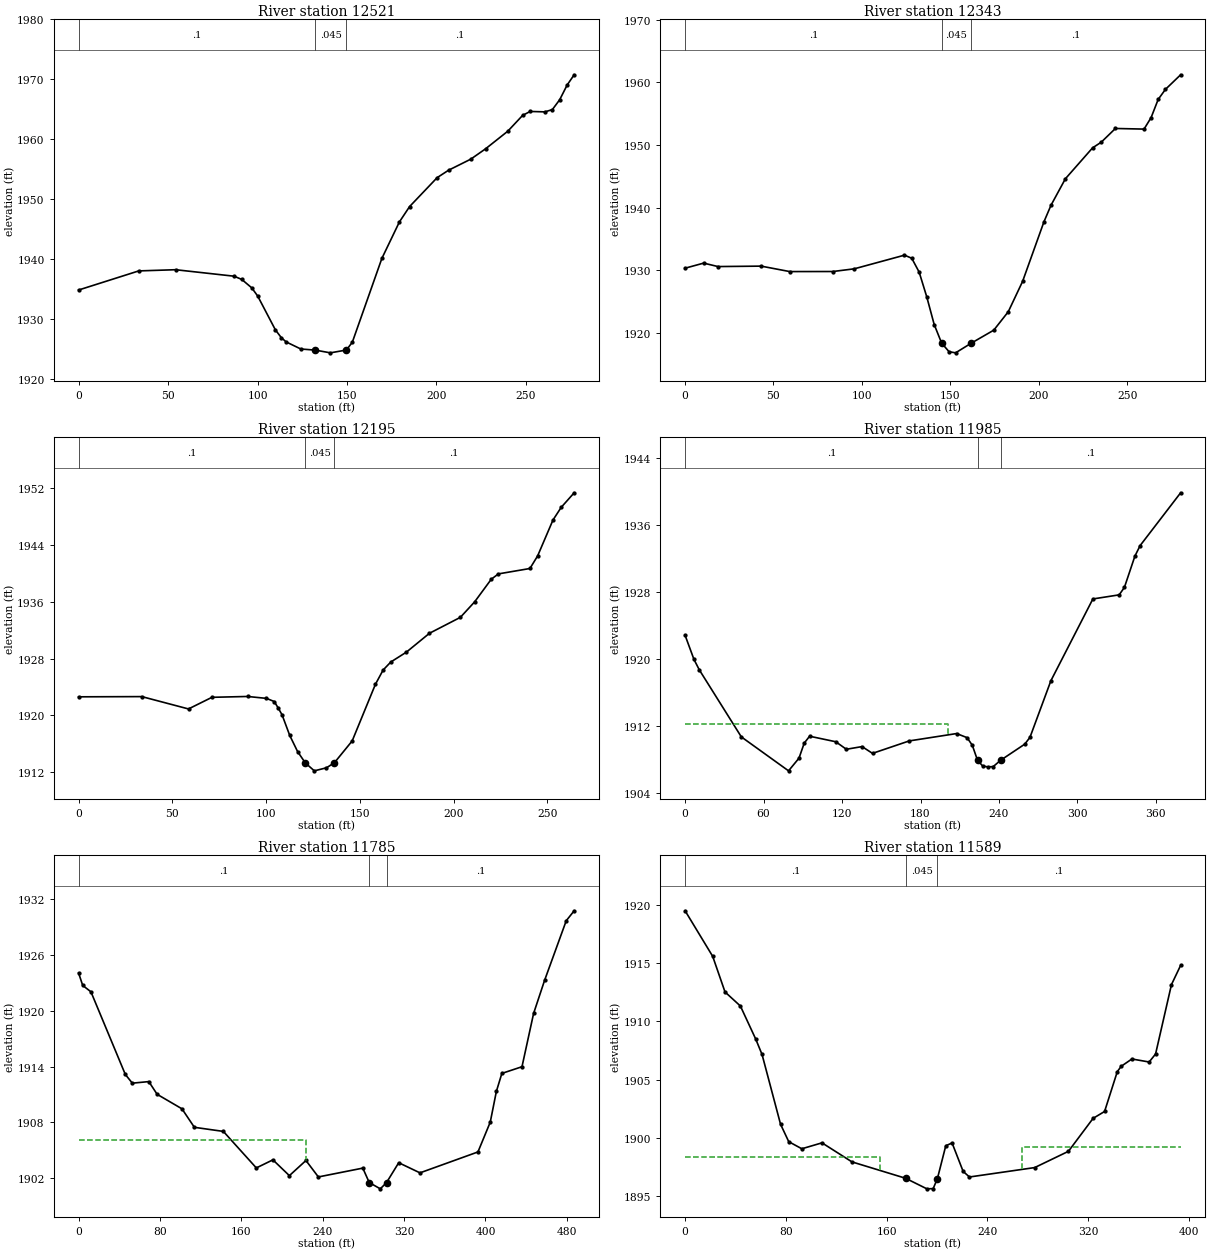
Type RM Length L Ch R = 1 ,12521   ,178.4,178.4,176.9
XS GIS Cut Line= 3
2199075.59167024673001.7397322692199242.87974442672960.498575092
2199343.94962257672933.198090764
#Sta/Elev= 30
       0 1934.89    33.6 1938.07    54.2 1938.27    86.9 1937.19    91.2 1936.65
    96.8 1935.24   100.1 1933.88     110 1928.24   113.3 1926.95     116 1926.24
   124.2 1925.06   132.4 1924.87   140.7 1924.42   149.7 1924.89     153  1926.2
   169.5 1940.15   179.3 1946.23     185 1948.79   200.4 1953.61   206.8 1954.85
   219.2 1956.69   227.5 1958.42   239.9 1961.35   248.2 1963.99   252.4 1964.64
   260.6 1964.57   264.8 1964.95   268.9 1966.59   273.1 1969.06     277 1970.75
#Mann= 3 ,-1,0
       0      .1       0   132.4    .045       0   149.7      .1       0
Bank Sta=132.4,149.7
XS Rating Curve= 0 ,0
Exp/Cntr(USF)=0,0
Exp/Cntr=0.3,0.1

Type RM Length L Ch R = 1 ,12343   ,147,147.9,148.1
XS GIS Cut Line= 4
2199113.80063053673154.6021331972199239.00852556673133.303883012
2199288.05904114673117.1688449932199388.74167838673102.970011536
#Sta/Elev= 30
       0 1930.34    10.5 1931.15    18.6  1930.6      43 1930.67    59.2  1929.8
    83.6 1929.81    95.7 1930.24   124.1 1932.42   128.2 1931.93   132.4 1929.71
   136.7 1925.76   140.9 1921.35   145.1 1918.39   149.3 1917.01     153 1916.83
   161.9 1918.38   174.6 1920.45   182.8 1923.39   190.9 1928.23     203 1937.76
     207  1940.4   215.1 1944.61   230.5 1949.55   235.4 1950.45   243.4 1952.64
   259.6 1952.54   263.6 1954.38   267.6 1957.28   271.7 1958.88   280.3 1961.21
#Mann= 3 ,-1,0
       0      .1       0   145.1    .045       0   161.9      .1       0
Bank Sta=145.1,161.9
XS Rating Curve= 0 ,0
Exp/Cntr(USF)=0,0
Exp/Cntr=0.3,0.1

Type RM Length L Ch R = 1 ,12195   ,207.2,210.5,213
XS GIS Cut Line= 3
 2199163.7729656673303.9215443892199308.62975137673263.046114741
 2199419.0651227673235.795828309
#Sta/Elev= 30
       0  1922.6    33.7 1922.63    58.6 1920.89    71.1 1922.53    90.1 1922.65
   100.2 1922.38   104.3 1921.94   106.3 1921.09   108.5 1920.06   112.6 1917.15
   116.8 1914.87   120.9 1913.28   125.7 1912.16   132.2 1912.59  136.44 1913.31
   145.9 1916.38   158.3 1924.37   162.4 1926.38   166.5 1927.51   174.8  1928.9
   187.1 1931.56   203.6 1933.81   211.2 1935.99   220.1 1939.19   223.9 1939.94
   240.7  1940.7   244.8 1942.47     253 1947.54   257.4 1949.33   264.3 1951.38
#Mann= 3 ,-1,0
       0      .1       0   120.9    .045       0  136.44      .1       0
Bank Sta=120.9,136.44
XS Rating Curve= 0 ,0
Exp/Cntr(USF)=0,0
Exp/Cntr=0.3,0.1

Type RM Length L Ch R = 1 ,11985   ,203.1,200.1,195.5
XS GIS Cut Line= 4
2199121.36178343673482.0392409152199334.10524768673463.713024894
 2199436.0946238673457.3386888862199499.04119188 673451.76114488
#Sta/Elev= 30
       0 1922.83     6.8 1919.94    10.9 1918.69      43 1910.68    79.1 1906.62
    87.1 1908.14    91.1 1909.94    95.2 1910.76   115.2  1910.1   123.3  1909.2
   135.3 1909.52   143.3 1908.71   171.4  1910.2   207.6 1911.08   215.6 1910.59
   219.6 1909.68   223.6 1907.88   227.6 1907.19   231.6 1907.09   235.6 1907.13
  241.21 1907.88   259.7 1909.81   263.7 1910.63   279.7  1917.4   311.8 1927.18
   331.9 1927.67   335.9 1928.56   343.9 1932.29   347.9 1933.56   378.9 1939.88
#Mann= 3 ,-1,0
       0      .1       0   223.6    .045       0  241.21      .1       0
#XS Ineff= 2 , 0
          201.26 1912.23
Permanent Ineff=
       F       F
Bank Sta=223.6,241.21
XS Rating Curve= 0 ,0
Exp/Cntr(USF)=0,0
Exp/Cntr=0.3,0.1

Type RM Length L Ch R = 1 ,11785   ,200.3,195.7,191.5
XS GIS Cut Line= 4
2199096.24715763673710.5886779862199366.50467256673661.609822742
2199405.70822425673647.553487698 2199534.0179502673534.667384997
#Sta/Elev= 30
       0 1924.06       4 1922.74    12.1 1922.05    45.9 1913.16    52.8 1912.22
      69 1912.39    77.2 1911.02   101.6 1909.46   113.8 1907.47   142.3 1907.03
   174.7  1903.1     191 1903.97   207.2 1902.27   223.5  1903.9   235.7 1902.13
   279.4 1903.08   285.7 1901.53   296.6 1900.85   302.71901.522   314.7 1903.66
   335.6 1902.57   392.6 1904.82   404.7 1908.03   410.7 1911.33   416.1 1913.27
   435.9 1913.99   447.3 1919.72   458.1 1923.28   479.4  1929.7   487.2 1930.77
#Mann= 3 ,-1,0
       0      .1       0   285.7    .045       0   302.7      .1       0
#XS Ineff= 2 , 0
          223.12 1906.14
Permanent Ineff=
       T       F
Bank Sta=285.7,302.7
XS Rating Curve= 0 ,0
Exp/Cntr(USF)=0,0
Exp/Cntr=0.3,0.1

Type RM Length L Ch R = 1 ,11589   ,201.9,203.3,198.8
XS GIS Cut Line= 4
2199314.04055539673945.939855204 2199441.1189112673835.692245295
2199478.58791708673807.7685264042199619.95757095673698.756586063
#Sta/Elev= 30
       0 1919.53    21.9 1915.61    31.7 1912.54    43.9 1911.33    56.1 1908.48
    61.1 1907.16    75.8 1901.15    82.3 1899.65    92.7 1899.04   108.7 1899.55
   132.5 1897.91   175.1  1896.5     192 1895.59     197 1895.61  200.38 1896.48
     207  1899.3     212 1899.54   220.8 1897.09   225.8 1896.61   277.6 1897.42
   304.4 1898.82     324 1901.66   333.1 1902.25   343.2 1905.68   346.3 1906.14
   354.8 1906.77   368.5 1906.51   373.6  1907.2   386.2 1913.17   393.5 1914.83
#Mann= 3 ,-1,0
       0      .1       0   175.1    .045       0  200.38      .1       0
#XS Ineff= 2 , 0
          154.99 1898.34  267.75         1899.15
Permanent Ineff=
       F       F
Bank Sta=175.1,200.38
XS Rating Curve= 0 ,0
Exp/Cntr(USF)=0,0
Exp/Cntr=0.3,0.1

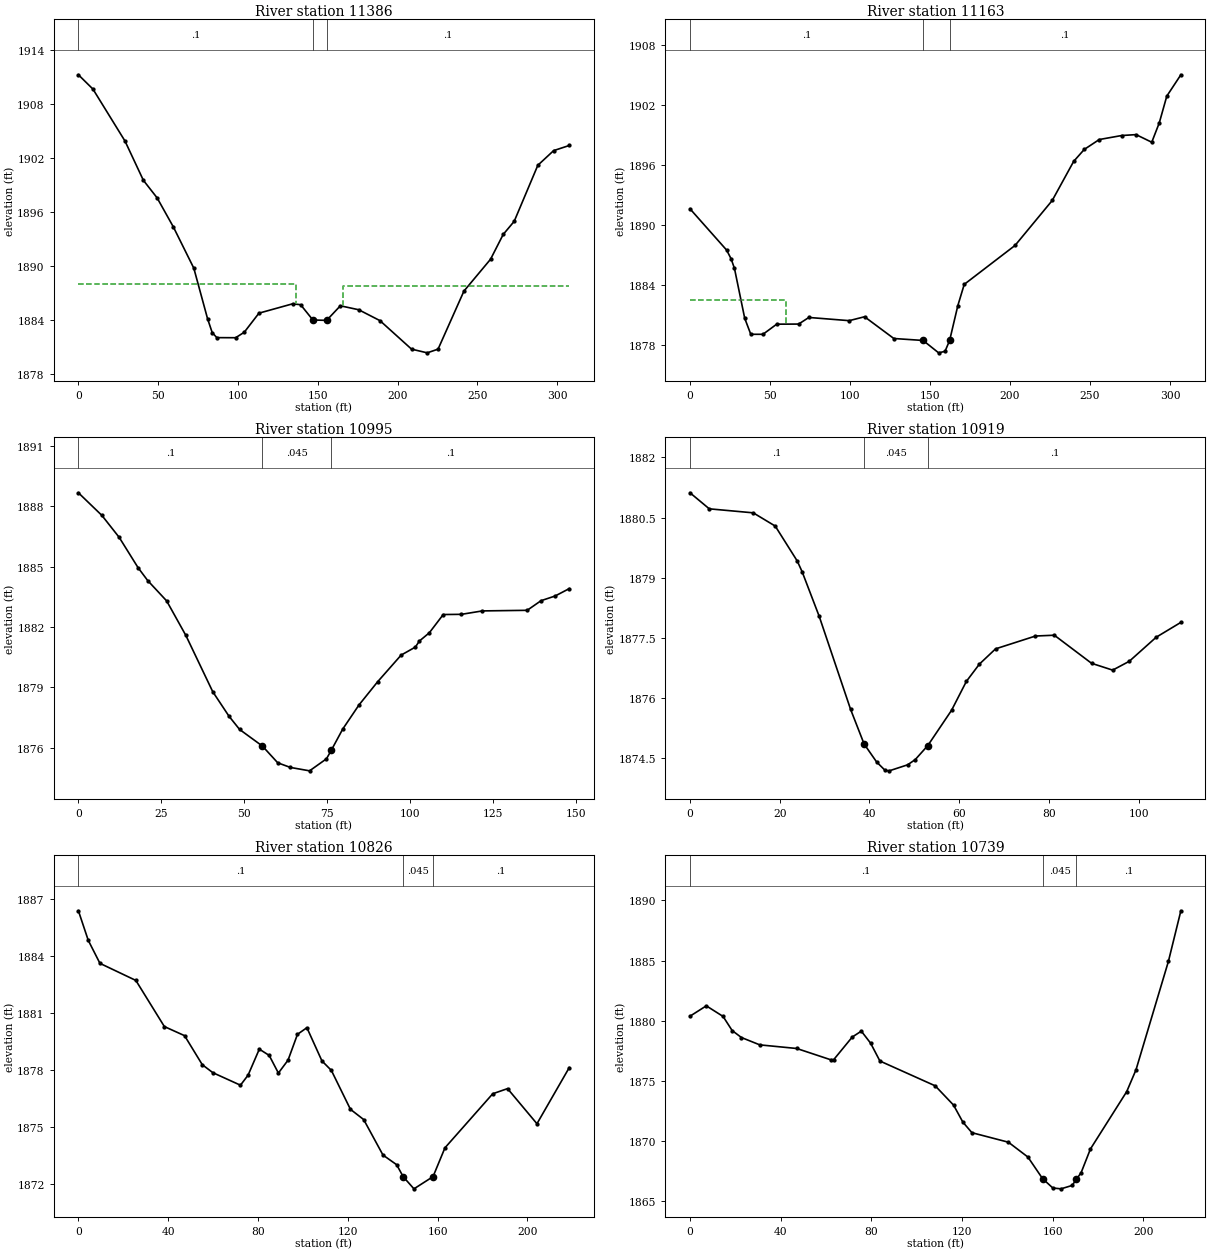
Type RM Length L Ch R = 1 ,11386   ,208.1,223,235.3
XS GIS Cut Line= 4
2199471.39414027674049.0576231482199571.07281958673979.497681465
2199605.49423403673931.4511238092199708.04136455 673856.87139252
#Sta/Elev= 30
       0 1911.23     9.1 1909.64    29.2 1903.86    40.7  1899.5    49.3 1897.55
    59.5 1894.31    72.3 1889.73    80.9 1884.12    83.8 1882.58    86.7 1882.01
    98.5    1882   103.9 1882.61   113.1 1884.73   134.2 1885.77   139.2 1885.67
   146.9 1883.97   155.5 1883.93   164.1 1885.55   175.6 1885.11   188.9  1883.9
   208.7 1880.73   218.5 1880.32   225.3 1880.73   241.5 1887.18   258.2 1890.73
   266.1 1893.48     273 1894.94   287.8 1901.17   297.7  1902.8   307.5 1903.37
#Mann= 3 ,-1,0
       0      .1       0   146.9    .045       0   155.5      .1       0
#XS Ineff= 2 , 0
          136.39 1887.92   165.7         1887.71
Permanent Ineff=
       T       F
Bank Sta=146.9,155.5
XS Rating Curve= 0 ,0
Exp/Cntr(USF)=0,0
Exp/Cntr=0.3,0.1

Type RM Length L Ch R = 1 ,11163   ,179.6,167.8,151.8
XS GIS Cut Line= 4
 2199653.7582622674126.8858770682199721.95766763674041.666786687
2199793.06317095674041.567737075 2199859.1404905673933.700143996
#Sta/Elev= 30
       0 1891.63    22.9 1887.51    25.7 1886.64    27.8 1885.68    34.2 1880.71
      38 1879.11    45.6 1879.11    54.2 1880.12    67.9 1880.13    74.3 1880.79
    99.5 1880.47   109.1 1880.86   127.4 1878.69   145.71878.495   155.4 1877.26
   159.4 1877.41  162.28  1878.5   167.4 1881.97   171.4 1884.09   203.2 1887.98
   226.4 1892.46   239.8 1896.36   246.4 1897.55   255.8 1898.54   269.8 1898.94
   278.8 1899.03   288.6 1898.27   293.3  1900.2     298 1902.87   306.8    1905
#Mann= 3 ,-1,0
       0      .1       0   145.7    .045       0  162.28      .1       0
#XS Ineff= 2 , 0
           59.86 1882.51
Permanent Ineff=
       T       F
Bank Sta=145.7,162.28
XS Rating Curve= 0 ,0
Exp/Cntr(USF)=0,0
Exp/Cntr=0.3,0.1

Type RM Length L Ch R = 1 ,10995   ,76,76.1,75.9
XS GIS Cut Line= 3
2199784.08054729674222.2007684332199833.47151475674152.436026893
2199853.22790174674093.166865939
#Sta/Elev= 30
       0 1888.68     7.1 1887.55    12.3 1886.46      18 1884.95    20.9 1884.31
    26.6  1883.3    32.4 1881.58    40.5 1878.78    45.4 1877.56    48.6  1876.9
    55.5 1876.07    60.1 1875.24    63.9 1875.01    69.7 1874.84    74.8 1875.44
    76.3 1875.88    79.7 1876.92    84.6 1878.12    90.2 1879.27    97.3  1880.6
   101.6    1881   102.8  1881.3   105.8 1881.71     110 1882.62   115.5 1882.63
   121.8  1882.8   135.3 1882.83   139.5 1883.31   143.7 1883.54     148 1883.91
#Mann= 3 ,-1,0
       0      .1       0    55.5    .045       0    76.3      .1       0
Bank Sta=55.5,76.3
XS Rating Curve= 0 ,0
Exp/Cntr(USF)=0,0
Exp/Cntr=0.3,0.1

Type RM Length L Ch R = 1 ,10919   ,112.9,93.2,72.9
XS GIS Cut Line= 3
2199857.66640165674248.6454989542199899.20664435674190.336717923
2199888.32691179674154.122772767
#Sta/Elev= 26
       0 1881.12     4.3 1880.72    14.1 1880.62      19 1880.29    23.9 1879.42
      25 1879.15    28.8 1878.04    35.8 1875.72    38.8 1874.86    41.6 1874.41
    43.5  1874.2    44.4 1874.19    48.5 1874.34    50.2 1874.47      53 1874.82
    58.3  1875.7    61.6 1876.42    64.5 1876.85    68.1 1877.23      77 1877.55
    81.2 1877.57    89.5 1876.87    94.2  1876.7    97.9 1876.92   103.9 1877.52
   109.4 1877.89
#Mann= 3 ,-1,0
       0      .1       0    38.8    .045       0      53      .1       0
Bank Sta=38.8,53
XS Rating Curve= 0 ,0
Exp/Cntr(USF)=0,0
Exp/Cntr=0.3,0.1

Type RM Length L Ch R = 1 ,10826   ,73.4,86.1,96.7
XS GIS Cut Line= 4
2199940.03656218674321.3090563742199975.83008204674218.860630897
2199918.00046406674186.014097166 2199891.3829779674151.344530848
#Sta/Elev= 30
       0 1886.37     4.4 1884.81     9.6  1883.6    25.6  1882.7    38.3 1880.27
    47.3 1879.79    55.2 1878.26    59.9 1877.84    72.2 1877.18    75.6 1877.71
    80.6 1879.08      85 1878.75    89.1 1877.82    93.4  1878.5    97.6 1879.86
   101.8 1880.21   108.5 1878.46   112.7 1877.96   121.2 1875.91   127.1 1875.37
   135.7  1873.5   141.8 1872.99   144.7 1872.36   149.5 1871.72     1581872.363
   163.3 1873.88   184.6 1876.73   191.2    1877   204.3 1875.15   218.7 1878.11
#Mann= 3 ,-1,0
       0      .1       0   144.7    .045       0     158      .1       0
Bank Sta=144.7,158
XS Rating Curve= 0 ,0
Exp/Cntr(USF)=0,0
Exp/Cntr=0.3,0.1

Type RM Length L Ch R = 1 ,10739   ,97.5,108.9,120.5
XS GIS Cut Line= 3
2199978.08898141674303.4960089192199999.96667877674187.183987633
2199989.80041054674089.468620577
#Sta/Elev= 30
       0 1880.38     7.2 1881.24    14.6 1880.36    18.6 1879.19    22.7 1878.61
    30.8    1878    47.1  1877.7      62 1876.77    63.4 1876.77    71.6 1878.65
    75.6 1879.14    79.7 1878.14    83.8 1876.66   108.2  1874.6   116.3    1873
   120.4 1871.59   124.4 1870.71   140.5 1869.92   149.1 1868.69   155.61866.891
   160.1 1866.12   163.7 1866.05   168.6 1866.33   170.51866.838   172.6  1867.4
   176.7 1869.36   192.7 1874.12   196.8 1875.93   211.1 1884.93   216.6 1889.13
#Mann= 3 ,-1,0
       0      .1       0   155.6    .045       0   170.5      .1       0
Bank Sta=155.6,170.5
XS Rating Curve= 0 ,0
Exp/Cntr(USF)=0,0
Exp/Cntr=0.3,0.1

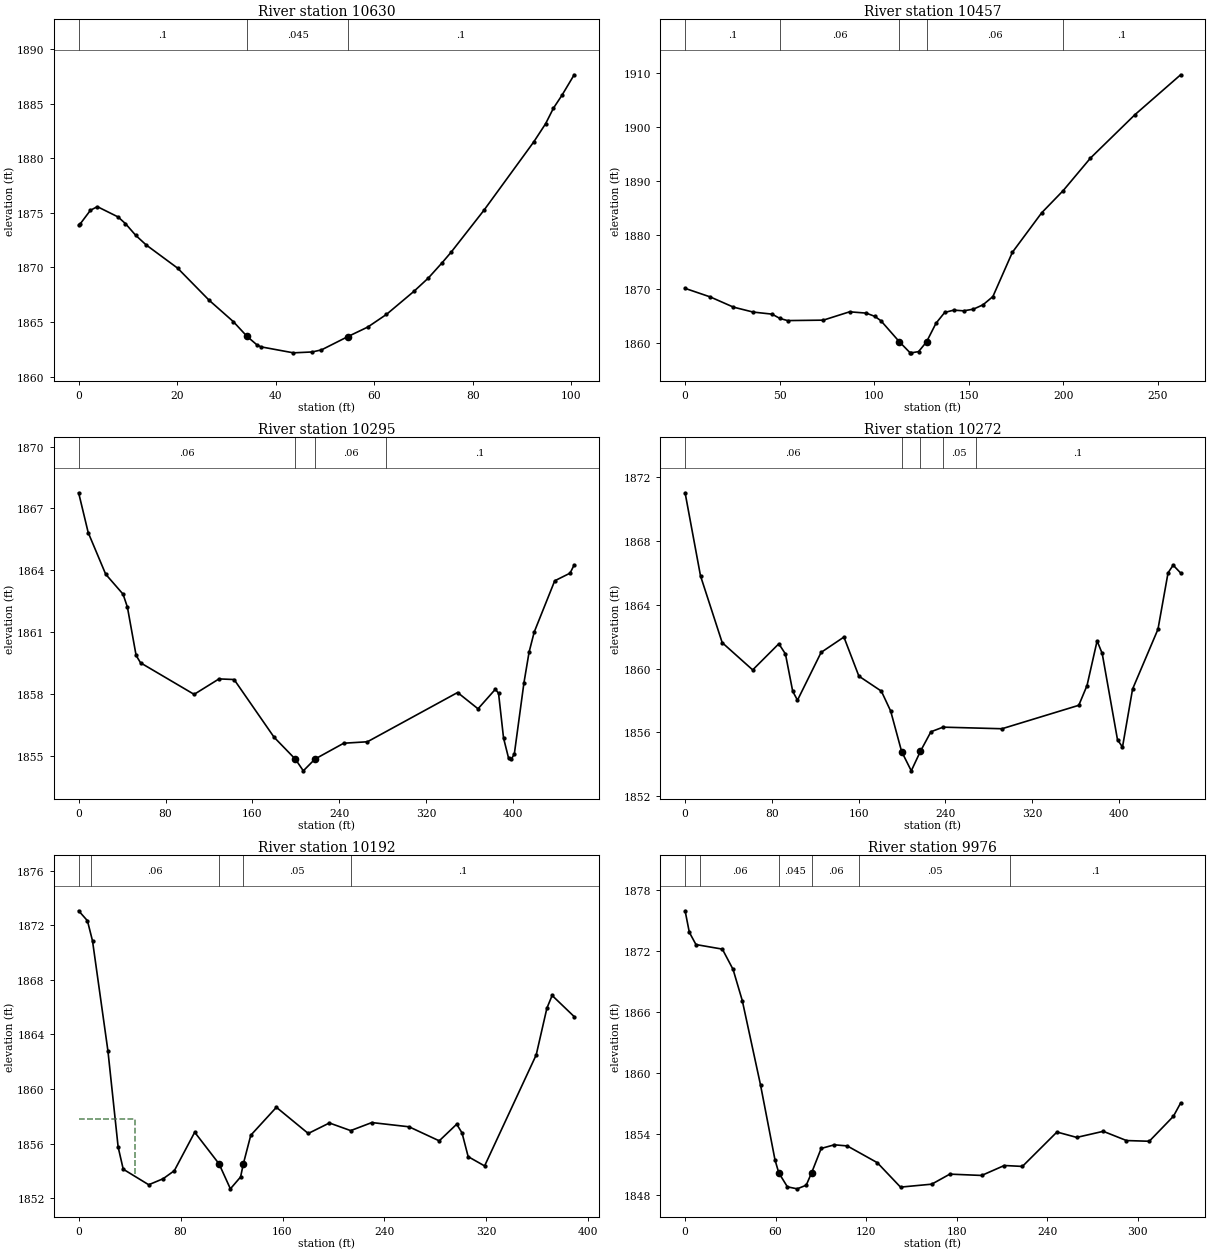
Type RM Length L Ch R = 1 ,10630   ,170.7,173.9,177.2
XS GIS Cut Line= 2
2200053.51326146674226.8911914322200124.27508315674155.379244418
#Sta/Elev= 30
       0 1873.87      .3 1873.97     2.4 1875.23     3.8 1875.56       8 1874.62
     9.5 1874.01    11.6 1872.93    13.7 1872.06    20.1 1869.93    26.5 1866.99
    31.4 1865.04    34.2 1863.68    36.2 1862.91      37 1862.73    43.6 1862.18
    47.4 1862.26    49.3 1862.45   54.67 1863.67    58.7 1864.54    62.5  1865.7
    68.1 1867.82      71 1869.03    73.8 1870.43    75.6 1871.38    82.3 1875.24
    92.4 1881.49    94.8 1883.15    96.4 1884.58    98.1 1885.74   100.6 1887.63
#Mann= 3 ,-1,0
       0      .1       0    34.2    .045       0   54.67      .1       0
Bank Sta=34.2,54.67
XS Rating Curve= 0 ,0
Exp/Cntr(USF)=0,0
Exp/Cntr=0.3,0.1

Type RM Length L Ch R = 1 ,10457   ,114.6,161.2,169
XS GIS Cut Line= 4
2200087.18607075674351.0515685142200174.97189583674332.034234513
2200218.61918328674306.9946402292200313.11264574674229.900755915
#Sta/Elev= 30
       0 1870.18    13.3  1868.6    25.6 1866.71      36  1865.8      46 1865.42
    50.1 1864.63    54.2 1864.23    73.1 1864.31      87 1865.85    95.8 1865.61
   100.4    1865   103.6 1864.19  113.39 1860.29   118.9 1858.32   119.7 1858.27
   123.5  1858.5   127.7  1860.3   132.7 1863.73   137.3 1865.73   142.1 1866.16
   147.3 1866.03   152.5 1866.34   157.6 1867.15   162.8 1868.67   173.1 1876.84
   188.6 1884.14     200 1888.25   214.4 1894.25   237.9 1902.26   262.1 1909.64
#Mann= 5 ,-1,0
       0      .1       0      50     .06       0  113.39    .045       0
   127.7     .06       0  200.14      .1       0
Bank Sta=113.39,127.7
XS Rating Curve= 0 ,0
Exp/Cntr(USF)=0,0
Exp/Cntr=0.3,0.1

Type RM Length L Ch R = 1 ,10295   ,47.9,23,23.1
XS GIS Cut Line= 6
2200107.40666158674376.2426109042200197.44969798674368.808719261
2200314.54806868674448.5541890492200361.60800724674469.988848381
2200389.86661105674470.6293118332200511.43607009674545.690772483
#Sta/Elev= 30
       0 1867.76     8.8 1865.83    24.9 1863.81    40.9 1862.84    44.9 1862.21
    52.9 1859.87      57 1859.51   106.3 1857.98   129.2 1858.73   143.1  1858.7
   179.9  1855.9  199.551854.832   206.8 1854.27   217.5 1854.84     244 1855.61
   265.8 1855.68   348.8 1858.07   367.6 1857.28   383.6 1858.23   386.5 1858.03
   391.1 1855.86   395.8 1854.87   398.1 1854.83     401 1855.08   409.9 1858.55
   414.6 1860.03   419.3    1861   438.2 1863.49   452.3 1863.86   456.1 1864.26
#Mann= 4 ,-1,0
       0     .06       0  199.55    .045       0   217.5     .06       0
  283.24      .1       0
Bank Sta=199.55,217.5
XS Rating Curve= 0 ,0
Exp/Cntr(USF)=0,0
Exp/Cntr=0.3,0.1

Type RM Length L Ch R = 1 ,10272   ,86.8,79.9,68.7
XS GIS Cut Line= 6
2200098.05385143674393.8331852752200188.09688783674386.399293631
2200226.60193621674403.5035510812200306.36248608674471.980901216
2200393.35330405674497.5577066772200502.08325993674563.281346853
#Sta/Elev= 30
       0 1871.03    14.2 1865.82    34.2 1861.63    62.3 1859.92    86.4 1861.56
    92.5 1860.92    99.2 1858.58   103.6 1858.02   125.4 1861.02   146.4 1861.98
   160.2 1859.53   180.9 1858.59   189.5 1857.34   199.6  1854.8   208.5 1853.59
  216.88 1854.81   226.6 1856.04   237.8 1856.33   292.1 1856.23   362.9  1857.7
   370.5 1858.94   379.8 1861.74   384.5 1860.95   398.6 1855.54   403.2 1855.08
   412.5 1858.72   435.9 1862.47   445.2 1866.01   449.9 1866.49   456.8    1866
#Mann= 5 ,-1,0
       0     .06       0   199.6    .045       0  216.88     .06       0
  237.77     .05       0  267.77      .1       0
Bank Sta=199.6,216.88
XS Rating Curve= 0 ,0
Exp/Cntr(USF)=0,0
Exp/Cntr=0.3,0.1

Type RM Length L Ch R = 1 ,10192   ,224.5,216.9,209.3
XS GIS Cut Line= 4
2200125.27410568674518.4454981142200216.16720552674512.271627182
2200278.86654835674514.6718808372200504.82853899674579.579319971
#Sta/Elev= 30
       0 1873.07     6.9 1872.34    10.9 1870.86      23 1862.79      31 1855.75
      35 1854.12      55 1852.98    66.3 1853.42    75.1 1854.01    91.1 1856.83
   110.21854.512   119.1 1852.68   127.1 1853.55  129.28 1854.52   135.1 1856.61
   155.2 1858.66   180.2 1856.74   196.8 1857.51   213.5 1856.95   230.1 1857.54
   259.3 1857.23     283  1856.2   296.7 1857.42   300.9 1856.78   305.7 1855.04
   318.6 1854.36   359.1  1862.5   367.5 1865.93   371.6 1866.86   388.9 1865.31
#Mann= 5 ,-1,0
       0      .1       0      10     .06       0   110.2    .045       0
  129.28     .05       0  213.85      .1       0
#XS Ineff= 2 , 0
           43.89 1857.82
Permanent Ineff=
       F       F
Bank Sta=110.2,129.28
XS Rating Curve= 0 ,0
Exp/Cntr(USF)=0,0
Exp/Cntr=0.3,0.1

Type RM Length L Ch R = 1 ,9976    ,283.6,292.9,308.7
XS GIS Cut Line= 3
2200129.56433331 674724.38768885 2200226.2777512674682.042895072
2200448.97999996674672.632940899
#Sta/Elev= 30
       0    1876     2.8 1873.88     7.2 1872.67    24.7 1872.22    31.8 1870.22
    37.9 1867.15      50 1858.83    59.6 1851.44    62.1 1850.17    67.8 1848.79
    74.3 1848.59    80.3 1848.95   83.89 1850.18    90.2 1852.57    98.9 1852.93
   107.5 1852.82   127.4 1851.17   142.8 1848.76   163.5 1849.05   175.5 1850.04
   196.6 1849.91   211.6 1850.89   223.6  1850.8   246.5 1854.19   259.6 1853.66
   277.2 1854.26   292.6 1853.35   307.7 1853.28   323.7 1855.74   328.5 1857.05
#Mann= 6 ,-1,0
       0     .05       0      10     .06       0    62.1    .045       0
   83.89     .06       0  115.58     .05       0  215.58      .1       0
Bank Sta=62.1,83.89
XS Rating Curve= 0 ,0
Exp/Cntr(USF)=0,0
Exp/Cntr=0.3,0.1

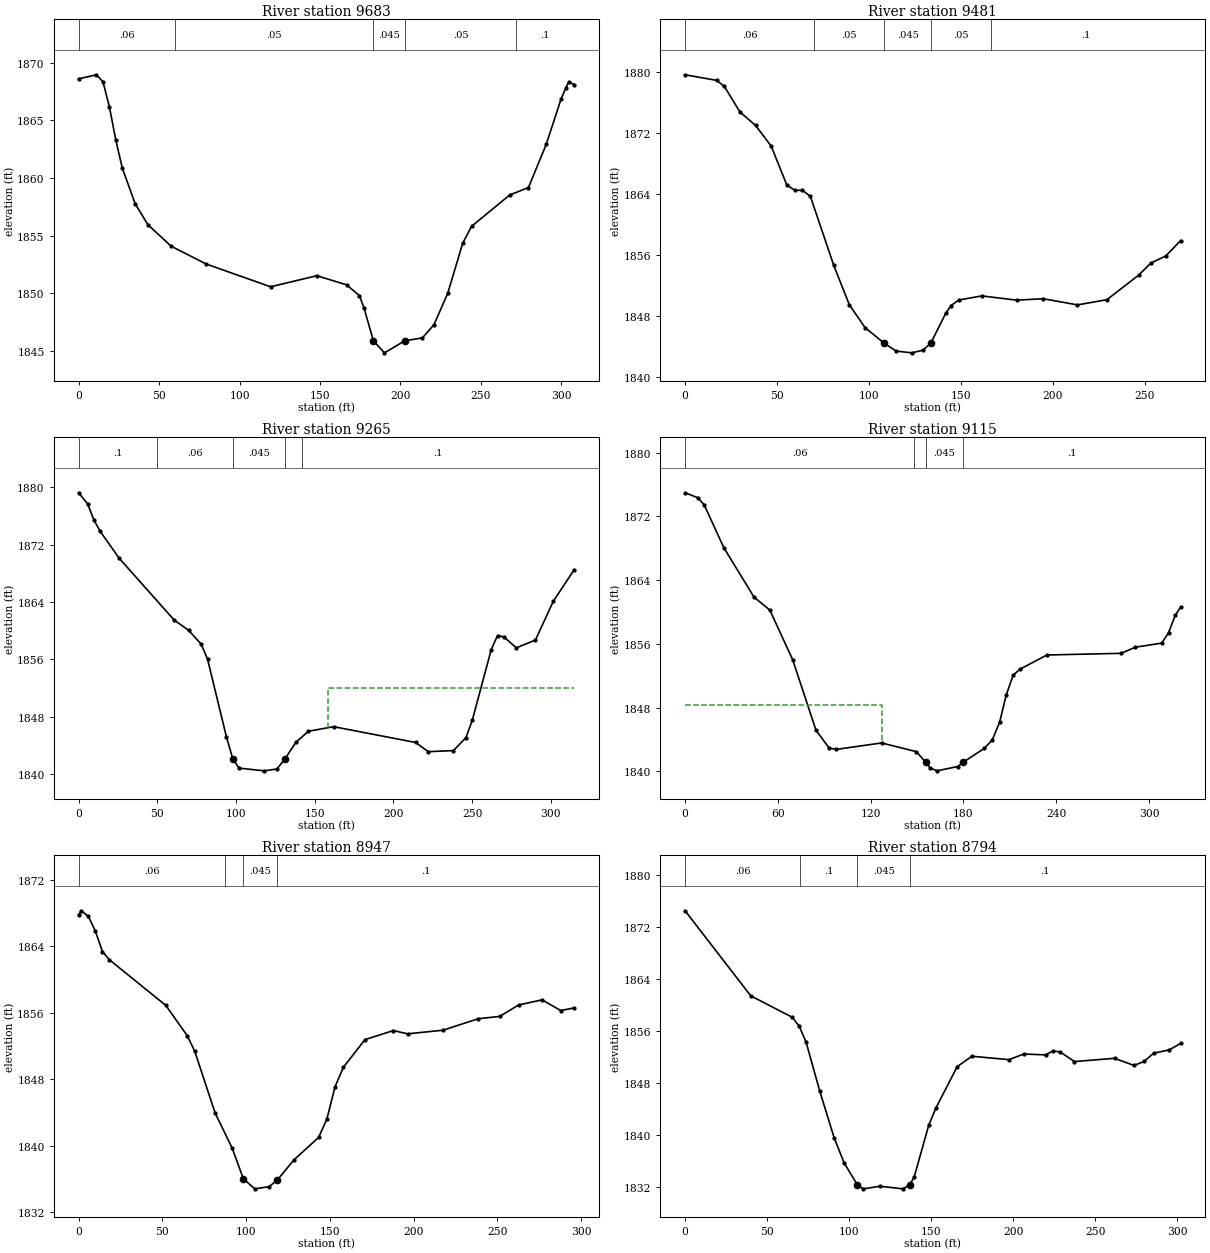
Type RM Length L Ch R = 1 ,9683    ,214.8,201.9,181.4
XS GIS Cut Line= 3
2200177.13687941   674799.1445472200328.74169664674789.734592827
2200463.09493122674869.196428064
#Sta/Elev= 30
       0 1868.61    11.1 1868.96    15.1 1868.36    19.1  1866.2    23.1  1863.3
    27.1 1860.89    35.1 1857.78    43.1 1855.95    57.5 1854.09    79.2 1852.55
   119.3 1850.57   148.1 1851.53   166.5 1850.74   174.5 1849.81   177.4 1848.73
   183.2 1845.88   190.1 1844.84  202.65 1845.88   213.7 1846.14   220.9 1847.29
   229.4    1850   238.7 1854.34   244.2 1855.81   267.9 1858.53   279.6 1859.18
   290.7 1862.95   299.9 1866.88   302.9 1867.84   304.6 1868.34     308 1868.11
#Mann= 5 ,-1,0
       0     .06       0      60     .05       0   183.2    .045       0
  202.65     .05       0   271.9      .1       0
Bank Sta=183.2,202.65
XS Rating Curve= 0 ,0
Exp/Cntr(USF)=0,0
Exp/Cntr=0.3,0.1

Type RM Length L Ch R = 1 ,9481    ,197.2,216.2,208.6
XS GIS Cut Line= 3
2200176.11309907674974.3747782512200323.26464581674921.451853548
2200436.20991194674924.678861152
#Sta/Elev= 30
       0  1879.6    17.1 1878.87    21.3 1878.09    29.8 1874.72    38.3 1872.96
    46.8 1870.24    55.3 1865.14    59.6 1864.45    63.8 1864.44    68.1 1863.66
    80.8  1854.6    89.3 1849.42    97.8 1846.44  108.39 1844.35   114.8 1843.35
   123.3 1843.12   129.2 1843.46   133.5 1844.36   141.7 1848.31   144.6 1849.33
   148.8 1850.05   161.3 1850.59   180.3 1850.03   194.7 1850.22   213.3 1849.41
   229.3 1850.09   246.5  1853.3   253.3 1854.91   261.3 1855.82   269.4 1857.85
#Mann= 5 ,-1,0
       0     .06       0      70     .05       0  108.39    .045       0
   133.5     .05       0  166.38      .1       0
Bank Sta=108.39,133.5
XS Rating Curve= 0 ,0
Exp/Cntr(USF)=0,0
Exp/Cntr=0.3,0.1

Type RM Length L Ch R = 1 ,9265    ,144.1,150,160.8
XS GIS Cut Line= 4
2200190.53710235675127.0033747112200262.05275407675121.357402207
  2200350.976821675115.7114297042200504.82957173675122.298397625
#Sta/Elev= 30
       0 1879.26     5.7 1877.71     9.7 1875.47    13.7 1873.87    25.7 1870.13
    60.8 1861.45    69.9 1860.05    77.9 1858.09    81.9 1856.01    93.9 1845.15
    97.9 1842.11   101.9 1840.79     118 1840.41     126 1840.67  131.28 1842.13
     138  1844.4     146 1845.94     162 1846.58   214.1 1844.37   222.1 1843.09
   238.1 1843.24   246.1 1845.06   250.1  1847.5   262.1 1857.34   266.1  1859.3
   270.1 1859.13   278.1 1857.59   290.2 1858.69   301.6 1864.12   314.8 1868.51
#Mann= 5 ,-1,0
       0      .1       0      50     .06       0    97.9    .045       0
  131.28     .06       0  141.74      .1       0
#XS Ineff= 2 , 0
                          158.73         1851.96
Permanent Ineff=
       F       T
Bank Sta=97.9,131.28
XS Rating Curve= 0 ,0
Exp/Cntr(USF)=0,0
Exp/Cntr=0.3,0.1

Type RM Length L Ch R = 1 ,9115    ,161.3,167.8,159.7
XS GIS Cut Line= 4
2200168.59691058675203.6579314762200289.27957285675247.273069067
2200365.07675371675285.3833834672200463.31667528 675328.57507312
#Sta/Elev= 30
       0 1874.97     8.1 1874.36    12.3 1873.47    25.1 1868.06    44.6 1861.87
    54.8 1860.25    69.6 1854.01    84.6 1845.19    93.1 1842.94    97.7 1842.76
   127.1 1843.57   149.5 1842.48   155.7 1841.14   158.4 1840.46   162.9 1840.07
   176.3 1840.61   179.6 1841.12   193.6  1842.9   198.7 1843.96   203.4 1846.16
   207.7 1849.59   212.2 1852.08   216.5 1852.82     234 1854.61   282.1 1854.82
   291.2 1855.59   308.3  1856.1   312.7 1857.42     317 1859.58   320.5 1860.64
#Mann= 4 ,-1,0
       0     .06       0  148.32      .1       0   155.7    .045       0
   179.6      .1       0
#XS Ineff= 2 , 0
          127.09 1848.32
Permanent Ineff=
       T       F
Bank Sta=155.7,179.6
XS Rating Curve= 0 ,0
Exp/Cntr(USF)=0,0
Exp/Cntr=0.3,0.1

Type RM Length L Ch R = 1 ,8947    ,153.6,152.5,148.8
XS GIS Cut Line= 4
2200154.64668579675337.9619219192200218.42526408675358.872931192
2200293.70489746675413.2415553012200422.30760449675457.154674775
#Sta/Elev= 30
       0 1867.79     1.6 1868.29     5.8 1867.62      10 1865.84    14.2 1863.38
    18.4 1862.39    52.1 1856.89    64.8 1853.27    69.3  1851.4    81.5 1843.95
    91.6 1839.76    98.4 1836.02   105.2 1834.82   113.7 1835.08   118.6 1835.87
   128.5 1838.29   143.3 1841.01   148.2  1843.2   153.1  1847.1   158.1 1849.46
     171 1852.78   187.9 1853.87   196.4 1853.48   217.5 1853.91   238.7  1855.3
   251.4 1855.57   262.7 1856.95   276.7 1857.57   287.9 1856.28   295.9  1856.6
#Mann= 4 ,-1,0
       0     .06       0   87.12      .1       0    98.4    .045       0
   118.6      .1       0
Bank Sta=98.4,118.6
XS Rating Curve= 0 ,0
Exp/Cntr(USF)=0,0
Exp/Cntr=0.3,0.1

Type RM Length L Ch R = 1 ,8794    ,176.5,171.7,165.3
XS GIS Cut Line= 3
 2200074.1733359675476.087021292  2200154.848526675502.548483644
2200350.40518679675596.777105676
#Sta/Elev= 30
       0 1874.48      40 1861.38    65.3 1858.07    69.5 1856.72    73.7 1854.28
    82.1 1846.67    90.8 1839.53    96.9 1835.65  104.94 1832.27   108.6 1831.64
   118.6 1832.04   132.8 1831.64     137 1832.27   139.7 1833.54   148.5 1841.47
     153 1844.16   165.8 1850.46   174.8 1852.07   197.4 1851.54   206.3 1852.41
   219.7 1852.28     224 1852.87   228.5 1852.74   237.3 1851.25   261.7 1851.75
   273.6 1850.65   279.6 1851.26   285.6 1852.54   295.1 1853.05     302 1854.05
#Mann= 4 ,-1,0
       0     .06       0      70      .1       0  104.94    .045       0
     137      .1       0
Bank Sta=104.94,137
XS Rating Curve= 0 ,0
Exp/Cntr(USF)=0,0
Exp/Cntr=0.3,0.1