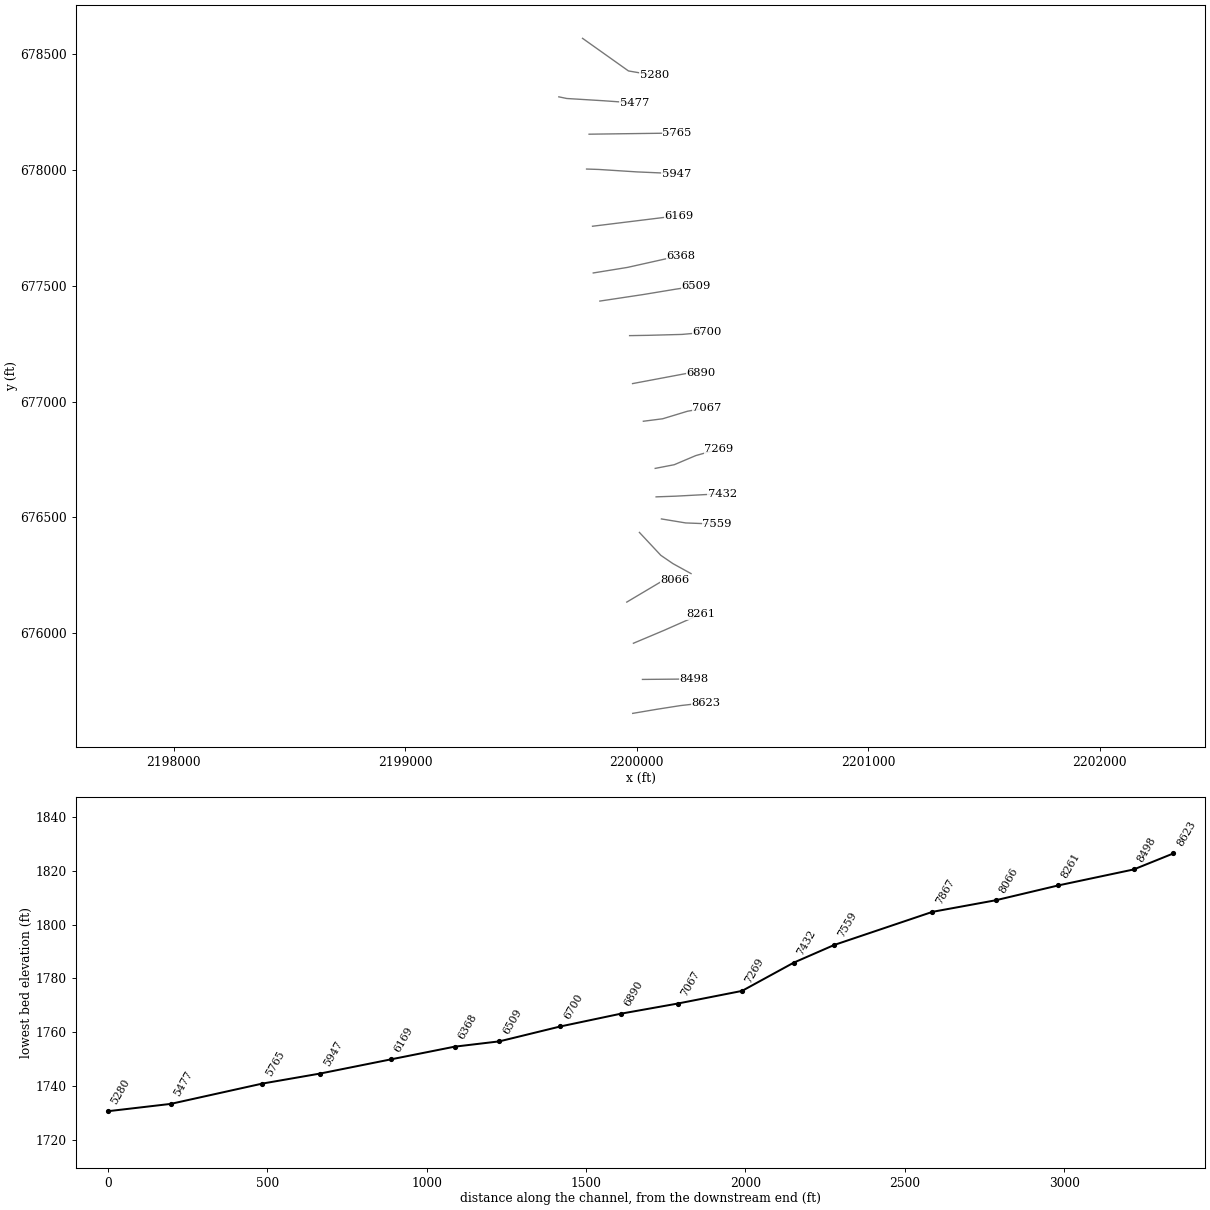
HEC-RAS study RFTENMILCK.prj: RFTENMILCK

--- RFTENMILCK.g01 (geometry) --- (continued)

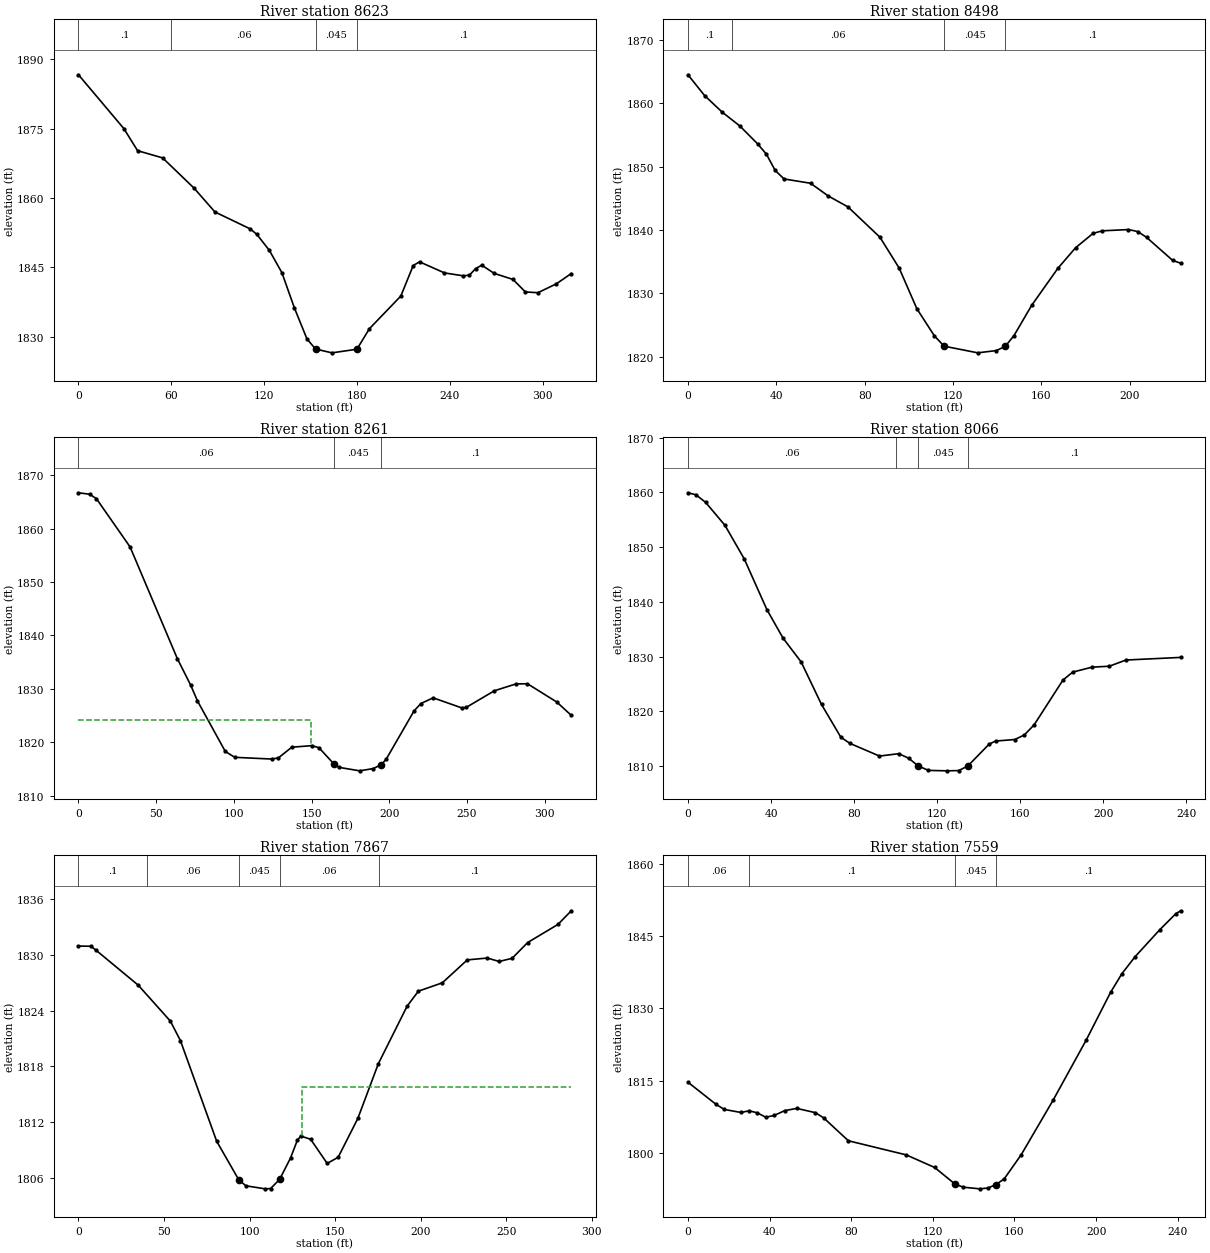
Type RM Length L Ch R = 1 ,8623    ,125.7,124.8,120
XS GIS Cut Line= 4
 2199982.5107448675653.1154372112200086.97902937675670.821926121
 2200188.7913406 675686.75776614 2200297.6862474675699.152308377
#Sta/Elev= 30
       0 1886.64    29.3 1875.02    38.2 1870.24    54.4 1868.68    74.7 1862.15
    88.2    1857   111.2 1853.31   115.3 1852.15   123.4  1848.7   131.5 1843.88
   139.6 1836.25   147.7 1829.57  153.24 1827.38   163.9 1826.56     180 1827.34
   188.1 1831.78   208.4 1838.83   216.4 1845.43   220.5 1846.22   236.6 1843.83
   248.6 1843.21   252.7 1843.33   256.7 1844.75   260.7  1845.5   268.8 1843.72
   280.9 1842.42   288.9 1839.72     297 1839.55     309 1841.48   318.6  1843.7
#Mann= 4 ,-1,0
       0      .1       0      60     .06       0  153.24    .045       0
     180      .1       0
Bank Sta=153.24,180
XS Rating Curve= 0 ,0
Exp/Cntr(USF)=0,0
Exp/Cntr=0.3,0.1

Type RM Length L Ch R = 1 ,8498    ,224.9,236.6,241.6
XS GIS Cut Line= 3
2200024.62836945675799.7372893152200208.68732167675801.330873316
2200247.73012971675801.330873316
#Sta/Elev= 30
       0 1864.54     7.5 1861.26    15.5 1858.63    23.5 1856.44    31.5 1853.63
    35.5 1851.99    39.5 1849.41    43.5 1848.07    55.5 1847.39    63.5 1845.38
    72.4 1843.66    86.9 1838.86    95.6 1833.99   103.6 1827.57   111.6 1823.24
     116 1821.63   131.2 1820.58   139.6 1820.94   143.6 1821.59   147.6 1823.31
   155.6 1828.09   167.5 1833.96   175.5  1837.2   183.4 1839.47   187.6 1839.87
   199.4 1840.07   203.6 1839.76   207.6 1838.84   219.4  1835.2   223.1 1834.74
#Mann= 4 ,-1,0
       0      .1       0      20     .06       0     116    .045       0
   143.6      .1       0
Bank Sta=116,143.6
XS Rating Curve= 0 ,0
Exp/Cntr(USF)=0,0
Exp/Cntr=0.3,0.1

Type RM Length L Ch R = 1 ,8261    ,192.6,195.6,196.9
XS GIS Cut Line= 3
2199985.59716003 675955.982872022200116.42843919676011.069726405
2200276.77053321676081.895682044
#Sta/Elev= 30
       0 1866.71     7.1 1866.44    11.5 1865.62    33.2 1856.57    63.6 1835.66
    72.2 1830.69    76.6 1827.71    94.5 1818.26   100.6 1817.16   124.3 1816.84
   128.7 1817.06   137.3 1819.06   150.4 1819.35   154.8 1818.95   164.6 1815.86
   167.9 1815.27     181 1814.63   189.8 1815.06   194.9  1815.8     198 1816.78
     216 1825.86   220.4 1827.24   228.3  1828.3   246.6 1826.43   249.5  1826.5
   267.7 1829.63   281.6 1830.91     289 1830.94   307.8 1827.53   317.2 1825.02
#Mann= 3 ,-1,0
       0     .06       0   164.6    .045       0   194.9      .1       0
#XS Ineff= 2 , 0
          149.36 1824.21
Permanent Ineff=
       F       F
Bank Sta=164.6,194.9
XS Rating Curve= 0 ,0
Exp/Cntr(USF)=0,0
Exp/Cntr=0.3,0.1

Type RM Length L Ch R = 1 ,8066    ,218.6,198.7,172
XS GIS Cut Line= 3
2199956.88240851676133.7464266232200125.80231271676234.142218741
2200166.43870476676230.158258736
#Sta/Elev= 30
       0 1859.91     3.8 1859.55     8.5 1858.16    17.8 1853.97    27.1 1847.83
      38 1838.57    45.8 1833.35    54.5 1829.01    64.3 1821.24    73.6 1815.27
    77.9 1814.15    92.2 1811.82   101.5 1812.25   106.2 1811.44   110.9 1810.01
   115.8  1809.2   124.8 1809.12   130.4 1809.17  134.77 1810.01     145 1813.99
   148.1 1814.56   157.4 1814.84     162 1815.68   166.7 1817.53   180.6 1825.72
   185.3 1827.16   194.6 1828.06   202.9 1828.23   210.9 1829.36   237.3 1829.84
#Mann= 4 ,-1,0
       0     .06       0     100      .1       0   110.9    .045       0
  134.77      .1       0
Bank Sta=110.9,134.77
XS Rating Curve= 0 ,0
Exp/Cntr(USF)=0,0
Exp/Cntr=0.3,0.1

Type RM Length L Ch R = 1 ,7867    ,290,308,313.9
XS GIS Cut Line= 4
2200011.47198745676434.6399699882200103.97953876676335.678403471
2200156.32877322676299.8227634292200234.49406852676256.795995378
#Sta/Elev= 30
       0 1830.95     7.2 1830.93      10 1830.54    34.9 1826.74    53.7 1822.87
    59.6 1820.76    80.8 1809.92   93.65 1805.79    97.8 1805.13   109.1  1804.8
   112.3 1804.83   117.6 1805.82     124 1808.14   127.9 1810.01   129.9 1810.49
   135.7 1810.14   145.4 1807.54   151.8  1808.2   163.3 1812.38   175.3 1818.28
   192.1 1824.47   198.7 1826.09   212.7 1826.99   227.3 1829.46     239 1829.66
   245.9 1829.29   253.5 1829.63   262.6 1831.33   280.3 1833.28   288.1 1834.75
#Mann= 5 ,-1,0
       0      .1       0      40     .06       0   93.65    .045       0
   117.6     .06       0  175.47      .1       0
#XS Ineff= 2 , 0
                          130.65         1815.74
Permanent Ineff=
       F       T
Bank Sta=93.65,117.6
XS Rating Curve= 0 ,0
Exp/Cntr(USF)=0,0
Exp/Cntr=0.3,0.1

Type RM Length L Ch R = 1 ,7559    ,125.1,126.9,127.1
XS GIS Cut Line= 3
2200106.58656251676492.8989310412200211.14160887676475.647348391
2200346.54039391676470.419596073
#Sta/Elev= 30
       0 1814.65    13.8 1810.03    17.8 1808.99    25.9 1808.36      30  1808.7
      34 1808.28    38.1 1807.37    42.2 1807.73    47.4 1808.74    53.3 1809.21
    62.4 1808.32    66.5 1807.23    78.6 1802.47     107 1799.53   120.9 1796.91
     131 1793.41     135 1792.81     143 1792.47     147 1792.64     151 1793.37
     155 1794.56   163.3 1799.56   179.1 1811.04   195.1 1823.38   207.1 1833.35
   212.7 1837.26   219.1 1840.76   231.1 1846.33   239.1 1849.73   241.5 1850.32
#Mann= 4 ,-1,0
       0     .06       0      30      .1       0     131    .045       0
     151      .1       0
Bank Sta=131,151
XS Rating Curve= 0 ,0
Exp/Cntr(USF)=0,0
Exp/Cntr=0.3,0.1

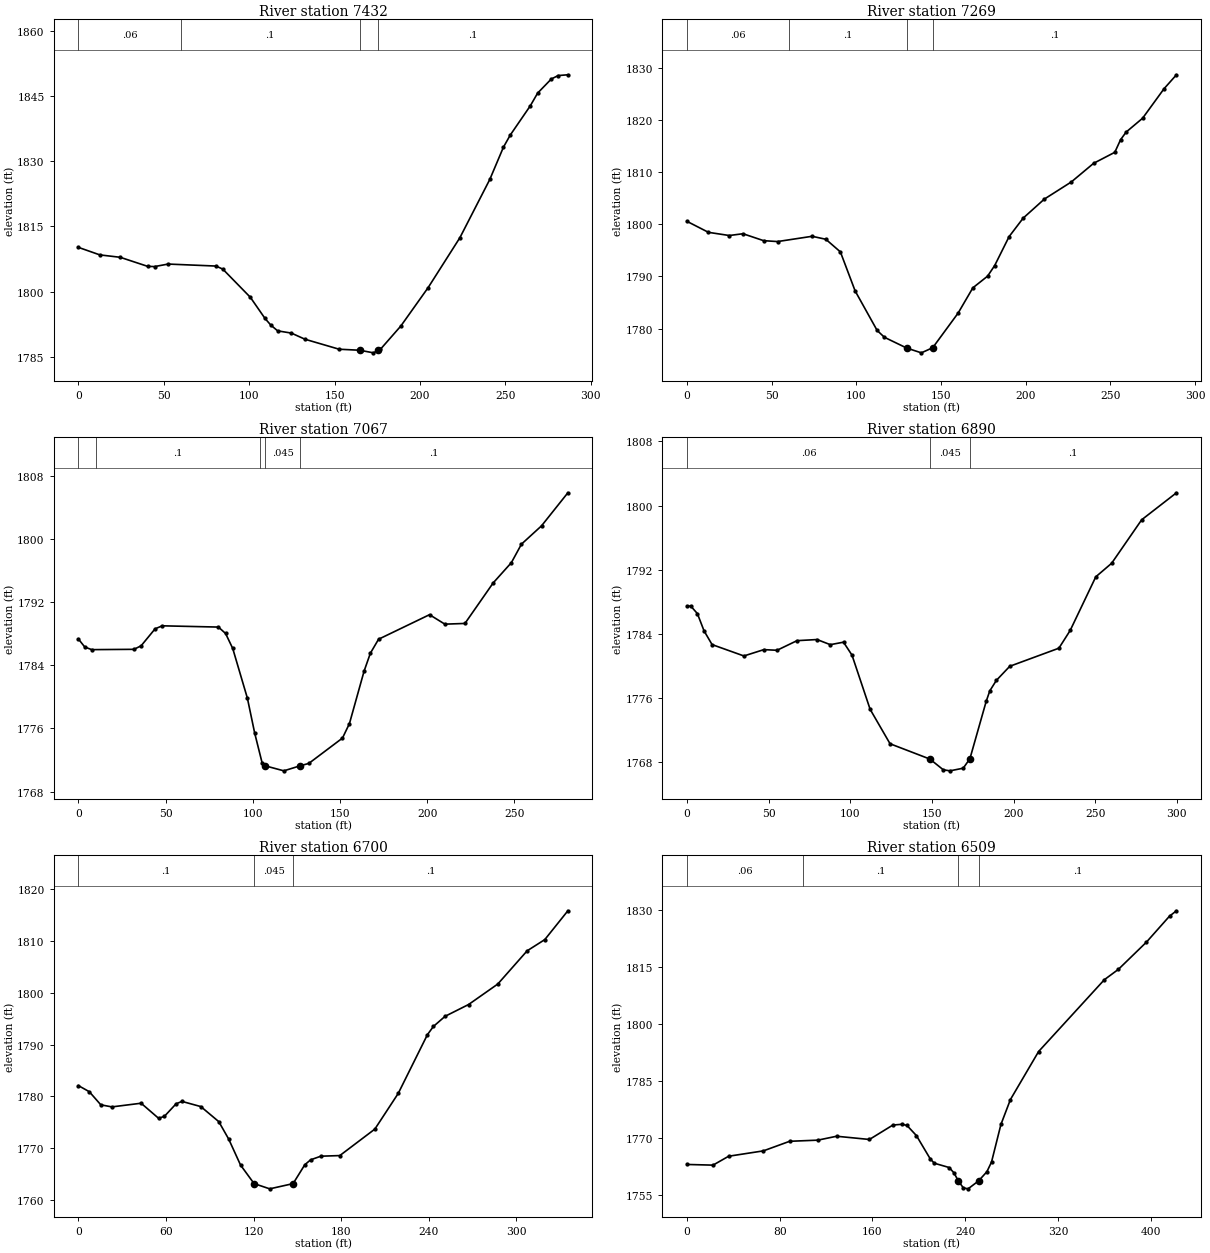
Type RM Length L Ch R = 1 ,7432    ,157.6,162.5,165.5
XS GIS Cut Line= 3
 2200083.5937368676588.2523530882200167.20771221676591.203434573
2200369.84864084676602.024066685
#Sta/Elev= 30
       0 1810.18    12.6 1808.44    24.5 1807.89    40.6  1805.8    44.6 1805.75
    52.6 1806.33    80.6 1805.87    84.6 1805.16   100.7 1798.68   109.3  1793.8
   112.7 1792.27   116.7 1790.95   124.7 1790.44   132.7 1789.02   152.7 1786.72
   164.7 1786.49   172.8 1785.89  175.67 1786.49   176.8 1786.68   188.8 1792.06
   204.8 1800.91   223.4 1812.41   240.9 1825.82   248.9 1833.26   252.9 1836.05
   264.6 1842.76   268.9 1845.69   276.9 1848.94   280.9 1849.73   286.6 1849.91
#Mann= 4 ,-1,0
       0     .06       0      60      .1       0   164.7    .045       0
  175.67      .1       0
Bank Sta=164.7,175.67
XS Rating Curve= 0 ,0
Exp/Cntr(USF)=0,0
Exp/Cntr=0.3,0.1

Type RM Length L Ch R = 1 ,7269    ,202.9,202.2,199.9
XS GIS Cut Line= 4
2200079.65896148676711.2140816282200161.77798015 676727.05438595
2200254.68239727676766.4021390832200355.23776639 676794.81996079
#Sta/Elev= 30
       0 1800.56    12.7 1798.45      25 1797.84    33.1 1798.18    45.3 1796.85
    53.5 1796.68    73.9 1797.69      82 1797.12    90.6  1794.7    99.3 1787.22
   112.3 1779.64   116.6 1778.33   129.8 1776.26   138.4 1775.35   145.1 1776.33
   160.1 1782.97   168.8 1787.81   177.5 1790.05   181.7 1792.09   190.2 1797.63
   198.5 1801.17     211 1804.82   226.9  1808.1   240.1 1811.68   252.6 1813.79
     256  1816.2   259.3 1817.67     269 1820.32   281.7 1825.99     289 1828.65
#Mann= 4 ,-1,0
       0     .06       0      60      .1       0   129.8    .045       0
   145.1      .1       0
Bank Sta=129.8,145.1
XS Rating Curve= 0 ,0
Exp/Cntr(USF)=0,0
Exp/Cntr=0.3,0.1

Type RM Length L Ch R = 1 ,7067    ,176.3,177.1,173.6
XS GIS Cut Line= 4
2200028.50688241 676914.838704092200111.93494253676925.501257008
2200219.50186266676958.1697290472200302.36823076676972.511985063
#Sta/Elev= 30
       0 1787.35     3.7 1786.32     7.7 1785.99    31.9 1786.03      36 1786.48
      44 1788.63    48.1 1789.01    80.3 1788.85    84.4 1788.04    88.5 1786.14
    96.9 1779.84   101.1  1775.4   105.3 1771.68  107.21 1771.26   117.8 1770.63
     127 1771.26   132.1 1771.57   151.4 1774.78   155.4 1776.62   163.8 1783.27
   167.4 1785.54   172.1 1787.31   201.3 1790.42   210.1 1789.22   221.6 1789.31
   237.8 1794.45   248.2 1797.01     254 1799.36   265.5 1801.68   280.6 1805.87
#Mann= 5 ,-1,0
       0     .06       0      10      .1       0  104.11     .06       0
  107.21    .045       0     127      .1       0
Bank Sta=107.21,127
XS Rating Curve= 0 ,0
Exp/Cntr(USF)=0,0
Exp/Cntr=0.3,0.1

Type RM Length L Ch R = 1 ,6890    ,191.8,190.5,185.4
XS GIS Cut Line= 3
2199981.89322306677077.4396572642200216.31469466677121.512089239
 2200277.5030554 677125.24717732
#Sta/Elev= 30
       0  1787.4     2.3 1787.46     6.4 1786.51    10.5 1784.35    15.4 1782.64
    34.9 1781.22    47.1 1782.01    55.2 1781.93    67.4 1783.13    79.7 1783.27
    87.8 1782.63    95.9 1782.94   101.1 1781.32   112.2 1774.56   124.4 1770.26
   148.8 1768.35     157 1767.01   161.1 1766.88   169.2 1767.21   173.3 1768.39
   183.3 1775.57   185.5 1776.87   189.5 1778.17   197.7 1779.93   227.8 1782.19
   234.7  1784.4   250.4  1791.1   260.1 1792.79   278.5 1798.22   299.8 1801.59
#Mann= 3 ,-1,0
       0     .06       0   148.8    .045       0   173.3      .1       0
Bank Sta=148.8,173.3
XS Rating Curve= 0 ,0
Exp/Cntr(USF)=0,0
Exp/Cntr=0.3,0.1

Type RM Length L Ch R = 1 ,6700    ,187.4,190.9,191.4
XS GIS Cut Line= 4
2199969.14455104677284.6055775082200049.17628206677285.900509109
2200195.74666248677289.835284422 2200303.9529836677299.672222705
#Sta/Elev= 30
       0 1782.07     7.5 1780.89    15.4 1778.35      23 1777.95      43 1778.66
      55 1775.74      59 1776.14      67 1778.56      71 1779.01    83.9 1778.01
    96.2  1775.1     103 1771.72   111.1 1766.71  120.38 1763.12   131.1 1762.11
   147.1 1763.12   155.1 1766.76   159.1 1767.72   166.1 1768.42   179.1 1768.54
   203.1 1773.66   219.1 1780.55   239.1 1791.91   243.2  1793.5   251.2 1795.46
   267.3 1797.74   287.3  1801.7   307.4 1808.12   319.5 1810.29   335.3 1815.86
#Mann= 3 ,-1,0
       0      .1       0  120.38    .045       0   147.1      .1       0
Bank Sta=120.38,147.1
XS Rating Curve= 0 ,0
Exp/Cntr(USF)=0,0
Exp/Cntr=0.3,0.1

Type RM Length L Ch R = 1 ,6509    ,138.8,140.9,139.5
XS GIS Cut Line= 4
2199840.53740379677433.8218299382200027.53501784677461.981704377
2200170.17062295677485.5903562572200257.71937367677498.378376025
#Sta/Elev= 30
       0    1763    22.5 1762.82      36 1765.17    65.9 1766.58    88.6 1769.11
   112.9 1769.41   129.1 1770.44   157.4 1769.59   177.6 1773.39   185.7  1773.6
   189.8 1773.28   197.9 1770.62   209.8  1764.5   213.3 1763.33   226.2 1762.19
   230.3 1760.78   234.2  1758.6   238.4 1756.82   242.5 1756.57   251.51758.659
   258.7 1761.08   262.7 1763.64   270.8 1773.54     279 1780.12   303.3 1792.78
     360 1811.72   372.1 1814.45   396.3 1821.63   416.2 1828.48   422.2  1829.9
#Mann= 4 ,-1,0
       0     .06       0     100      .1       0   234.2    .045       0
   251.5      .1       0
Bank Sta=234.2,251.5
XS Rating Curve= 0 ,0
Exp/Cntr(USF)=0,0
Exp/Cntr=0.3,0.1

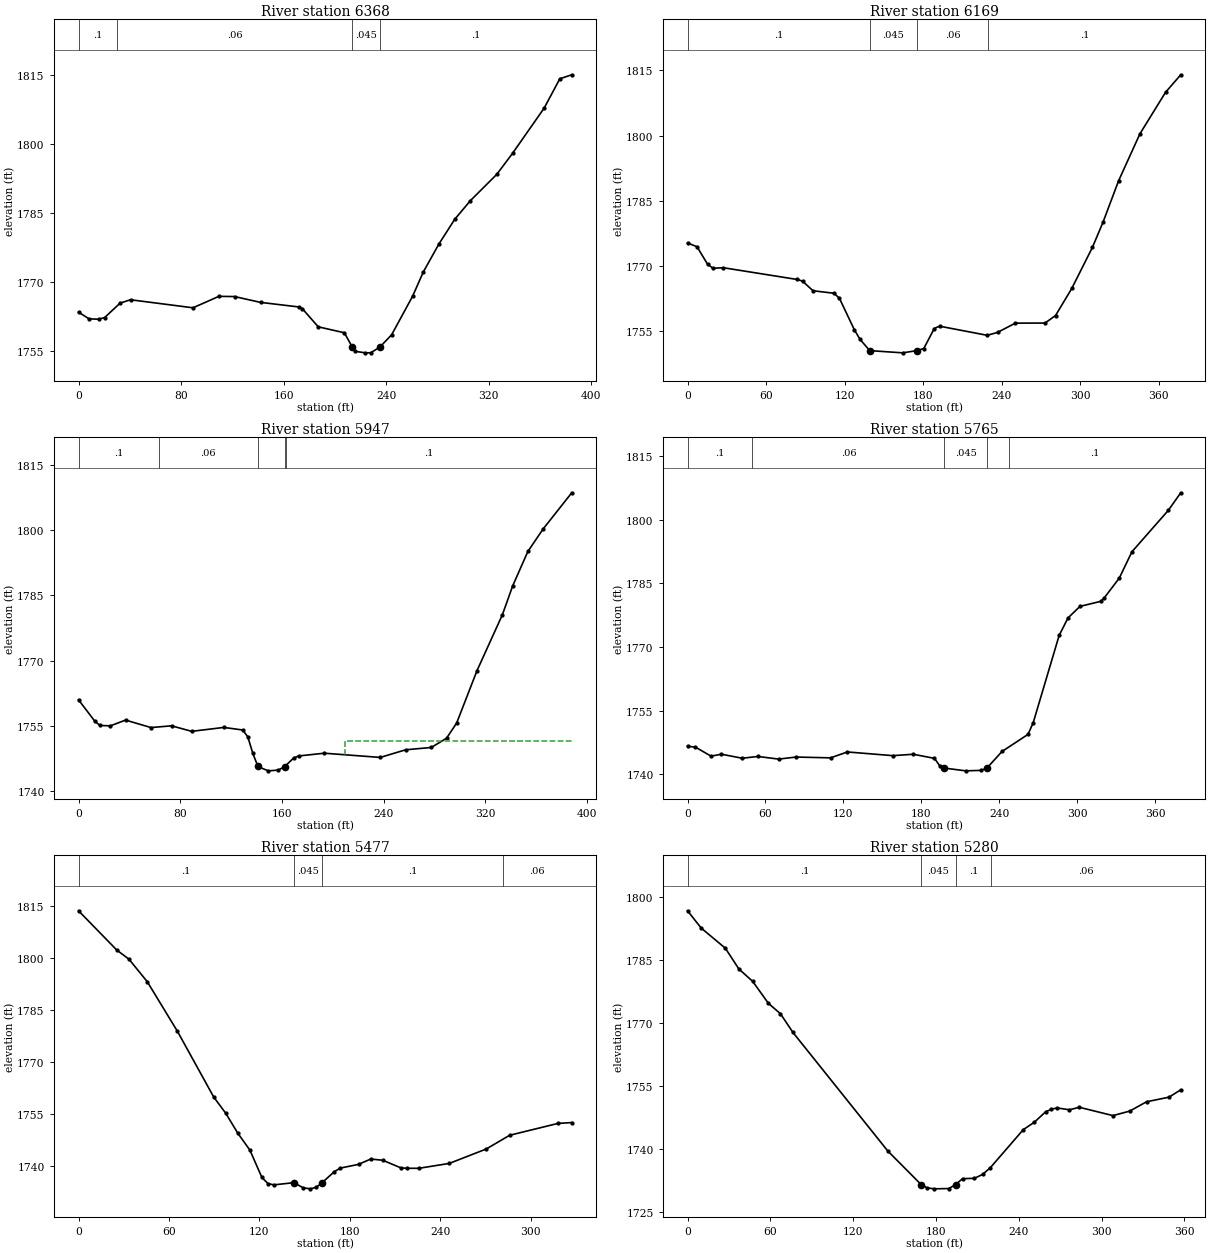
Type RM Length L Ch R = 1 ,6368    ,198.8,198.6,191.3
XS GIS Cut Line= 3
2199812.05061406677555.2655124462199959.88205968677579.254388003
 2200189.2756822677630.530609507
#Sta/Elev= 30
       0 1763.44     8.2 1761.99    15.7  1761.9    20.4 1762.27    32.5 1765.42
    40.6 1766.14    89.3 1764.39   109.5 1766.88   121.7 1766.84     142 1765.57
   171.7 1764.58   174.7 1764.17     187 1760.25   207.4 1758.95   213.6 1755.83
   215.6 1754.92   223.8 1754.58   227.9 1754.59  235.04 1755.81   244.3 1758.52
   260.7 1766.94   268.9 1772.14   281.2  1778.3   293.5 1783.66   305.8 1787.75
   326.3 1793.45   338.6 1798.03   363.2 1807.85   375.5 1814.27   384.8 1815.14
#Mann= 4 ,-1,0
       0      .1       0      30     .06       0   213.6    .045       0
  235.04      .1       0
Bank Sta=213.6,235.04
XS Rating Curve= 0 ,0
Exp/Cntr(USF)=0,0
Exp/Cntr=0.3,0.1

Type RM Length L Ch R = 1 ,6169    ,225.4,222.3,220.2
XS GIS Cut Line= 2
2199808.96919636 677757.06873395 2200183.1130711677803.104864175
#Sta/Elev= 30
       0 1775.23     7.3 1774.34    15.3 1770.32    19.4 1769.39    27.4 1769.51
    83.8  1766.8    87.9 1766.42    95.9  1764.2     112 1763.62   116.1 1762.46
   127.6 1755.15   131.9 1752.97   139.3 1750.39   164.4 1749.88  175.34 1750.39
   180.6 1750.88   188.6 1755.49   192.6 1756.03   229.1 1753.92     237  1754.6
   250.6 1756.73   273.3 1756.75   281.3 1758.49   293.7 1764.73   309.5 1774.21
   317.6 1780.02   329.5 1789.57   345.8  1800.4   365.4 1809.98     377 1814.01
#Mann= 4 ,-1,0
       0      .1       0   139.3    .045       0  175.34     .06       0
     230      .1       0
Bank Sta=139.3,175.34
XS Rating Curve= 0 ,0
Exp/Cntr(USF)=0,0
Exp/Cntr=0.3,0.1

Type RM Length L Ch R = 1 ,5947    ,177.7,181.8,185.9
XS GIS Cut Line= 4
2199783.23617962678004.0838347982199836.27366029678002.295669585
2199999.69787503677991.8005365292200170.61861337677984.304012918
#Sta/Elev= 30
       0 1760.96    12.9 1755.99    16.9 1755.05      25 1754.95      37 1756.28
      57 1754.56    73.2 1754.96      89 1753.69   114.3 1754.59   129.1    1754
   133.1 1752.44   137.1 1748.61   141.1 1745.59   149.2 1744.59   157.2 1744.76
  162.08 1745.56   169.2 1747.55   173.2 1748.02   193.3 1748.65   237.3 1747.68
   257.3 1749.44   277.4 1749.97   289.4 1752.09   297.4 1755.61   313.4 1767.68
   333.4 1780.58   341.4 1787.16   353.4 1795.13   365.4 1800.31   387.9 1808.64
#Mann= 5 ,-1,0
       0      .1       0   63.07     .06       0   141.1    .045       0
  162.08     .06       0  163.07      .1       0
#XS Ineff= 2 , 0
                          209.57         1751.53
Permanent Ineff=
       F       F
Bank Sta=141.1,162.08
XS Rating Curve= 0 ,0
Exp/Cntr(USF)=0,0
Exp/Cntr=0.3,0.1

Type RM Length L Ch R = 1 ,5765    ,278.6,287.7,290.8
XS GIS Cut Line= 3
2199794.05681173 678154.588990532199941.61088598678156.556378187
2200173.76262946678159.507459672
#Sta/Elev= 30
       0 1746.62     6.1 1746.43    18.1  1744.3    26.1 1744.76    42.1 1743.81
    54.1 1744.23    70.1 1743.61    83.6 1744.09   110.1  1743.9   123.1 1745.29
   158.1 1744.42   173.8 1744.75   190.1 1743.78   194.1 1742.06  197.79 1741.49
   214.1 1740.84   226.1 1740.95   230.6 1741.53   242.1  1745.4   262.1 1749.43
   266.1 1752.17   286.1 1772.77   292.9 1776.88   302.1  1779.6   318.1 1780.79
   320.6 1781.52   332.4 1786.28   342.1 1792.47   370.1 1802.23   379.7 1806.38
#Mann= 5 ,-1,0
       0      .1       0      50     .06       0  197.79    .045       0
   230.6     .06       0  247.57      .1       0
Bank Sta=197.79,230.6
XS Rating Curve= 0 ,0
Exp/Cntr(USF)=0,0
Exp/Cntr=0.3,0.1

Type RM Length L Ch R = 1 ,5477    ,203.1,197.2,186.8
XS GIS Cut Line= 4
2199663.35988526678315.956508523 2199697.6219413678308.785380514
2199853.79317348678299.2238765032199989.24781364678289.662372492
#Sta/Elev= 30
       0 1813.62    25.4 1802.27    33.5 1799.62    45.6 1793.14    65.6 1778.82
    89.7 1759.81    97.7 1755.11   105.7 1749.35   113.7 1744.47   121.7 1736.56
   125.7 1734.78   129.7 1734.42   142.8 1735.05   149.1 1733.58   153.8 1733.27
   157.8 1733.72  161.57 1735.02   169.8 1738.26   173.8 1739.27   185.8 1740.34
   193.9 1741.88   201.9 1741.53   213.9 1739.33   217.9 1739.21   225.9 1739.21
     246 1740.61   270.5 1744.77   286.1 1748.75   318.2 1752.18   327.3 1752.42
#Mann= 4 ,-1,0
       0      .1       0   142.8    .045       0  161.57      .1       0
  281.47     .06       0
Bank Sta=142.8,161.57
XS Rating Curve= 0 ,0
Exp/Cntr(USF)=0,0
Exp/Cntr=0.3,0.1

Type RM Length L Ch R = 1 ,5280    ,204.7,205.3,204.6
XS GIS Cut Line= 3
2199765.83597499678568.6052785992199964.14865078678427.838691767
2200076.58485536678408.361553966
#Sta/Elev= 30
       0 1796.72     9.9 1792.61    27.4 1787.81    37.2 1782.87    47.2 1779.92
    58.6 1774.69    67.3 1772.22    76.4 1767.75   145.1 1739.54  169.26 1731.55
   173.4 1730.79   178.7 1730.54   189.3 1730.61   194.2 1731.55   199.2 1732.96
   207.8 1733.04   213.8 1733.98   219.3 1735.55   243.2 1744.62   251.3 1746.41
   259.4 1748.88   263.5 1749.47   267.6  1749.8   276.7 1749.36   283.8 1749.95
   308.2 1747.97   320.4 1749.05   332.5 1751.26   348.8 1752.36   357.3 1754.11
#Mann= 4 ,-1,0
       0      .1       0  169.26    .045       0   194.2      .1       0
     220     .06       0
Bank Sta=169.26,194.2
XS Rating Curve= 0 ,0
Exp/Cntr(USF)=0,0
Exp/Cntr=0.3,0.1