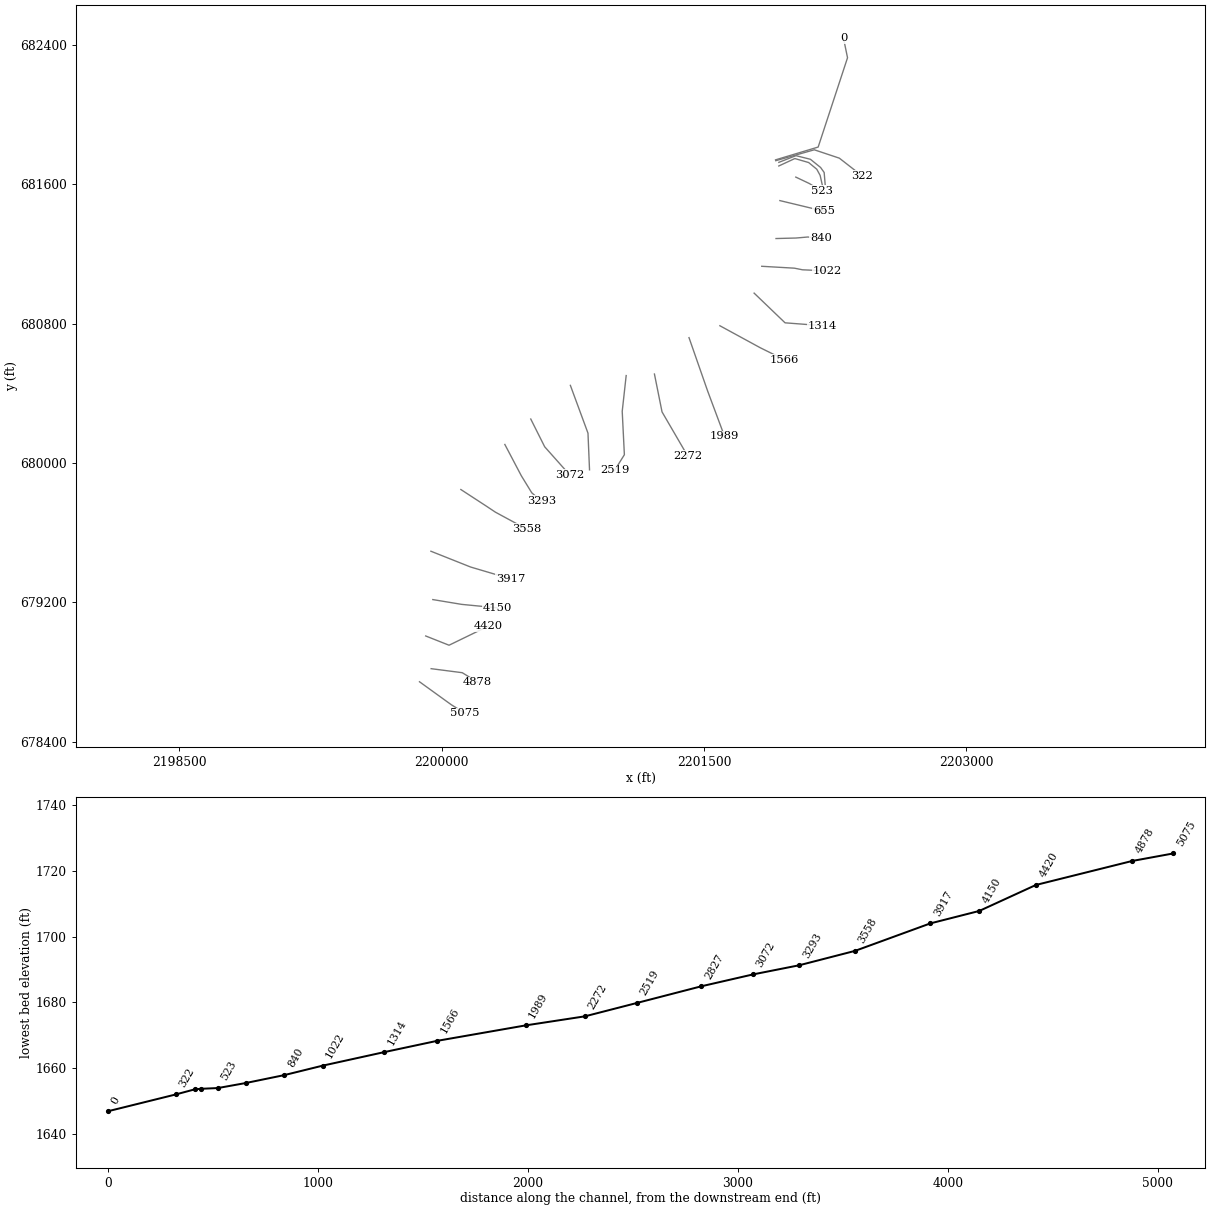
HEC-RAS study RFTENMILCK.prj: RFTENMILCK

--- RFTENMILCK.g01 (geometry) --- (continued)

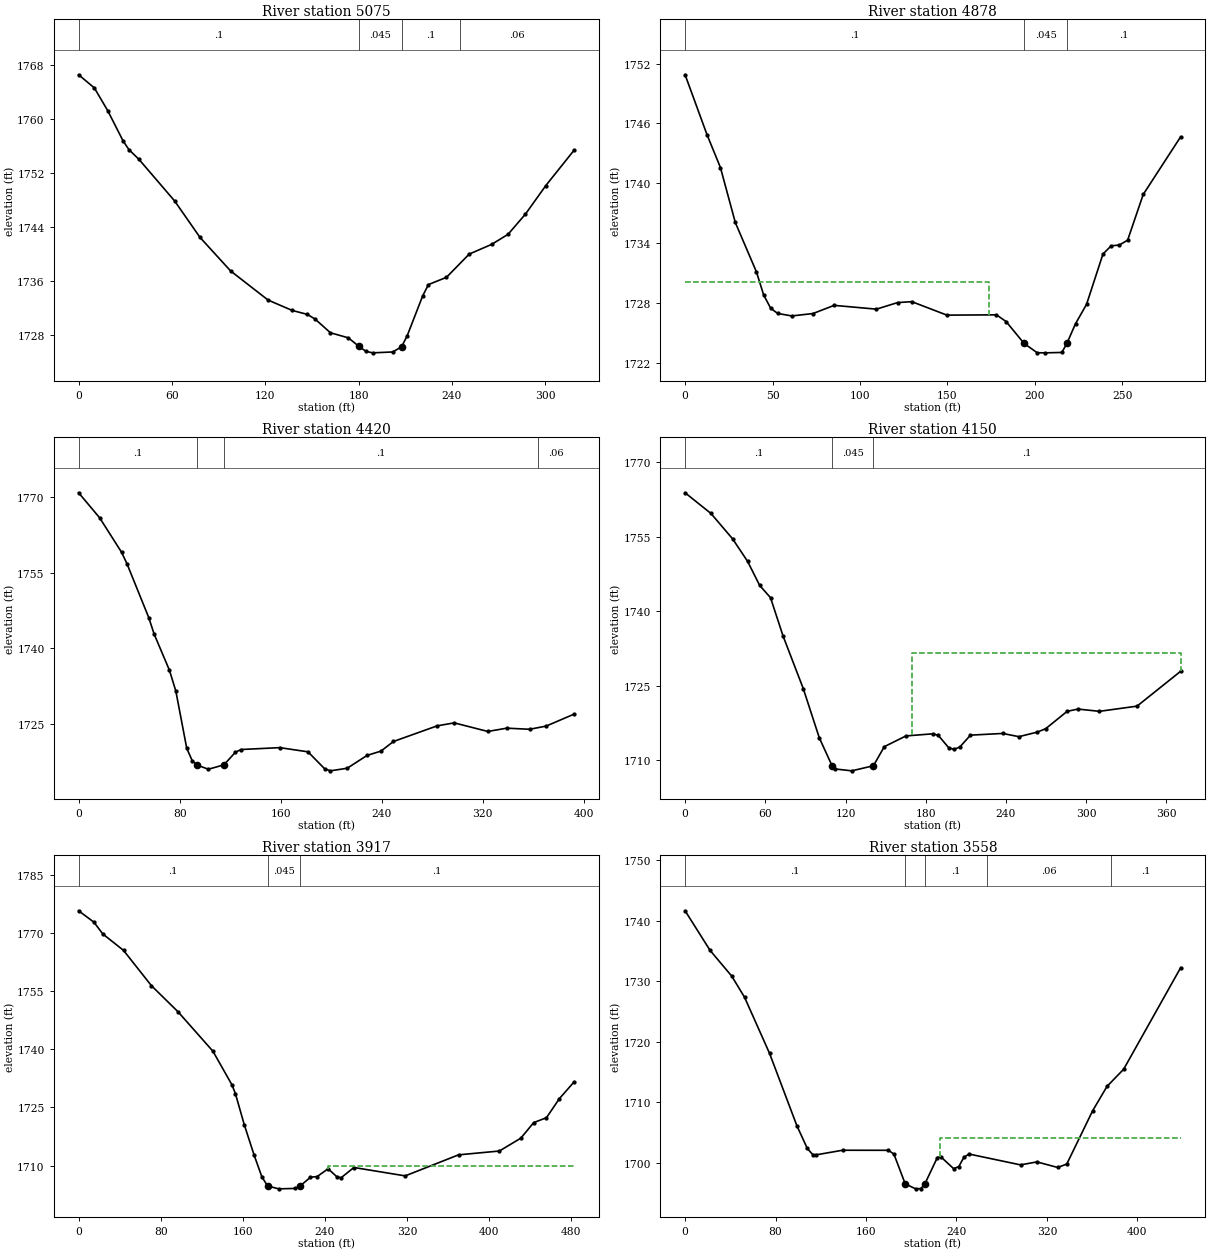
Type RM Length L Ch R = 1 ,5075    ,193.3,197.2,197.1
XS GIS Cut Line= 3
2199873.02422547678744.1433748712200055.17087689678612.194619516
2200134.77039778678562.713836258
#Sta/Elev= 30
       0 1766.61    10.1 1764.66    18.7 1761.28    28.6 1756.78    32.3  1755.5
    38.8 1754.04    61.7 1747.87      78 1742.46    97.7 1737.47   121.8 1733.14
   137.3  1731.6   147.1 1731.01   152.1  1730.3   161.9 1728.28   173.4 1727.53
   180.1 1726.28   184.8 1725.51   189.1  1725.3     202 1725.43   207.7 1726.22
   211.3 1727.87   221.2 1733.76   224.9 1735.44   236.5 1736.52   251.1 1739.97
   265.6 1741.42   276.1 1742.91   287.3 1745.92   300.4 1750.16   318.6 1755.42
#Mann= 4 ,-1,0
       0      .1       0   180.1    .045       0   207.7      .1       0
  244.92     .06       0
Bank Sta=180.1,207.7
XS Rating Curve= 0 ,0
Exp/Cntr(USF)=0,0
Exp/Cntr=0.3,0.1

Type RM Length L Ch R = 1 ,4878    ,447.6,458,455.7
XS GIS Cut Line= 3
2199939.66982073678819.2619447172200117.51795459678796.207556994
2200205.97152382678741.629822792
#Sta/Elev= 30
       0 1750.87    12.6 1744.83    20.2 1741.57    28.7 1736.06    40.8  1731.1
    44.9  1728.8    48.9 1727.47    52.9 1726.94      61 1726.69    73.1 1726.93
    85.2 1727.75   109.4 1727.37   121.5 1728.03   129.6 1728.12   149.7 1726.77
     178  1726.8   183.5 1726.13  193.81 1723.93   201.3    1723     206 1722.99
   215.4 1723.03   218.3 1723.95   223.2 1725.91   229.5 1727.85   238.9  1732.9
   243.6 1733.72   248.3  1733.8     253 1734.29   261.9 1738.87   283.3 1744.65
#Mann= 3 ,-1,0
       0      .1       0  193.81    .045       0   218.3      .1       0
#XS Ineff= 2 , 0
          173.91 1730.13
Permanent Ineff=
       T       F
Bank Sta=193.81,218.3
XS Rating Curve= 0 ,0
Exp/Cntr(USF)=0,0
Exp/Cntr=0.3,0.1

Type RM Length L Ch R = 1 ,4420    ,263.6,269.8,268.5
XS GIS Cut Line= 3
2199908.61459014679006.977043625 2200041.9975711678953.910696363
2200265.73676496679062.911842091
#Sta/Elev= 30
       0 1770.83    16.7 1765.85      34 1759.03    38.3 1756.75    55.5  1746.1
    59.8 1742.81    71.9 1735.65      77 1731.49    85.6 1720.18    89.9 1717.74
   93.56 1716.87   102.7 1716.02     115 1716.88   124.2  1719.4   128.7 1719.93
   159.3  1720.3   181.6 1719.47   194.9 1716.09   199.4  1715.7   212.7 1716.22
   228.4 1718.76   239.4 1719.61   249.3 1721.52   283.9 1724.62   297.4 1725.21
     324 1723.51   339.1 1724.16   357.1 1723.94   370.2 1724.57   392.4 1726.95
#Mann= 4 ,-1,0
       0      .1       0   93.56    .045       0     115      .1       0
  363.55     .06       0
Bank Sta=93.56,115
XS Rating Curve= 0 ,0
Exp/Cntr(USF)=0,0
Exp/Cntr=0.3,0.1

Type RM Length L Ch R = 1 ,4150    ,237.2,233.3,228.5
XS GIS Cut Line= 4
2199949.18180015679215.8821297822200016.04860673679204.739064693
2200114.41798956679188.3441675552200316.62172094679168.670290988
#Sta/Elev= 30
       0 1763.88    19.3 1759.72    35.5  1754.6    46.7 1750.07    55.8 1745.19
    63.9 1742.72    73.3 1734.98    88.4 1724.39   100.4 1714.45   109.9 1708.85
   112.5 1708.17   124.7  1707.8   140.9 1708.83     149 1712.67   165.2 1714.84
   185.4 1715.27   189.4 1714.95   197.4  1712.4   201.4 1712.16   205.5  1712.6
   213.5    1715   237.6 1715.34   249.7 1714.69   263.6 1715.62   269.8 1716.31
   285.8  1719.8   293.9 1720.26   309.9  1719.8   338.1 1720.85   370.7 1727.88
#Mann= 3 ,-1,0
       0      .1       0   109.9    .045       0   140.9      .1       0
#XS Ineff= 2 , 0
                        169.8999          1731.6
Permanent Ineff=
       F       T
Bank Sta=109.9,140.9
XS Rating Curve= 0 ,0
Exp/Cntr(USF)=0,0
Exp/Cntr=0.3,0.1

Type RM Length L Ch R = 1 ,3917    ,359.8,358.3,354.7
XS GIS Cut Line= 3
2199938.29766244679493.397204272 2200165.6402361679402.678773439
 2200394.0758029679334.913198599
#Sta/Elev= 30
       0 1775.68    14.9 1772.74    23.6  1769.7    43.8 1765.46    70.9 1756.39
    96.8 1749.67   130.9 1739.48   149.4 1730.83   152.8 1728.56   161.4 1720.58
   170.9 1712.82   178.6 1707.09  184.14 1704.77   194.9 1704.01   210.9 1704.11
     2161704.767     226 1707.01   232.5 1707.18   243.2 1709.18   251.6 1707.14
   255.8 1706.86   268.3 1709.51   318.3 1707.35   370.3 1712.77   410.1 1713.76
     431 1717.07   443.5 1721.07     456 1722.35   468.5 1727.23     483  1731.6
#Mann= 3 ,-1,0
       0      .1       0  184.14    .045       0     216      .1       0
#XS Ineff= 2 , 0
                          242.98         1709.93
Permanent Ineff=
       F       T
Bank Sta=184.14,216
XS Rating Curve= 0 ,0
Exp/Cntr(USF)=0,0
Exp/Cntr=0.3,0.1

Type RM Length L Ch R = 1 ,3558    ,271.4,265.5,259.3
XS GIS Cut Line= 4
2200109.69068178679847.5494720362200251.77979031679754.645054917
2200307.52244058 679717.483288072200484.58732968679621.299891524
#Sta/Elev= 30
       0 1741.62    22.1 1735.07    41.2 1730.83    52.6 1727.32    74.7 1718.05
    98.9 1706.08   108.1 1702.33   112.9 1701.32   116.2 1701.29   139.3 1702.04
   179.9 1702.03   184.7  1701.4   194.7 1696.48   203.9 1695.66   208.5 1695.71
     2121696.452   223.1 1700.83   225.9    1701   237.5    1699   242.1 1699.34
   246.6 1700.88   251.2 1701.41   296.7 1699.62   311.2 1700.11   329.6 1699.19
   337.6 1699.76   360.4 1708.54   373.2  1712.6   387.9 1715.43   438.3 1732.21
#Mann= 5 ,-1,0
       0      .1       0   194.7    .045       0     212      .1       0
  266.76     .06       0  376.76      .1       0
#XS Ineff= 2 , 0
                          225.15         1704.04
Permanent Ineff=
       F       F
Bank Sta=194.7,212
XS Rating Curve= 0 ,0
Exp/Cntr(USF)=0,0
Exp/Cntr=0.3,0.1

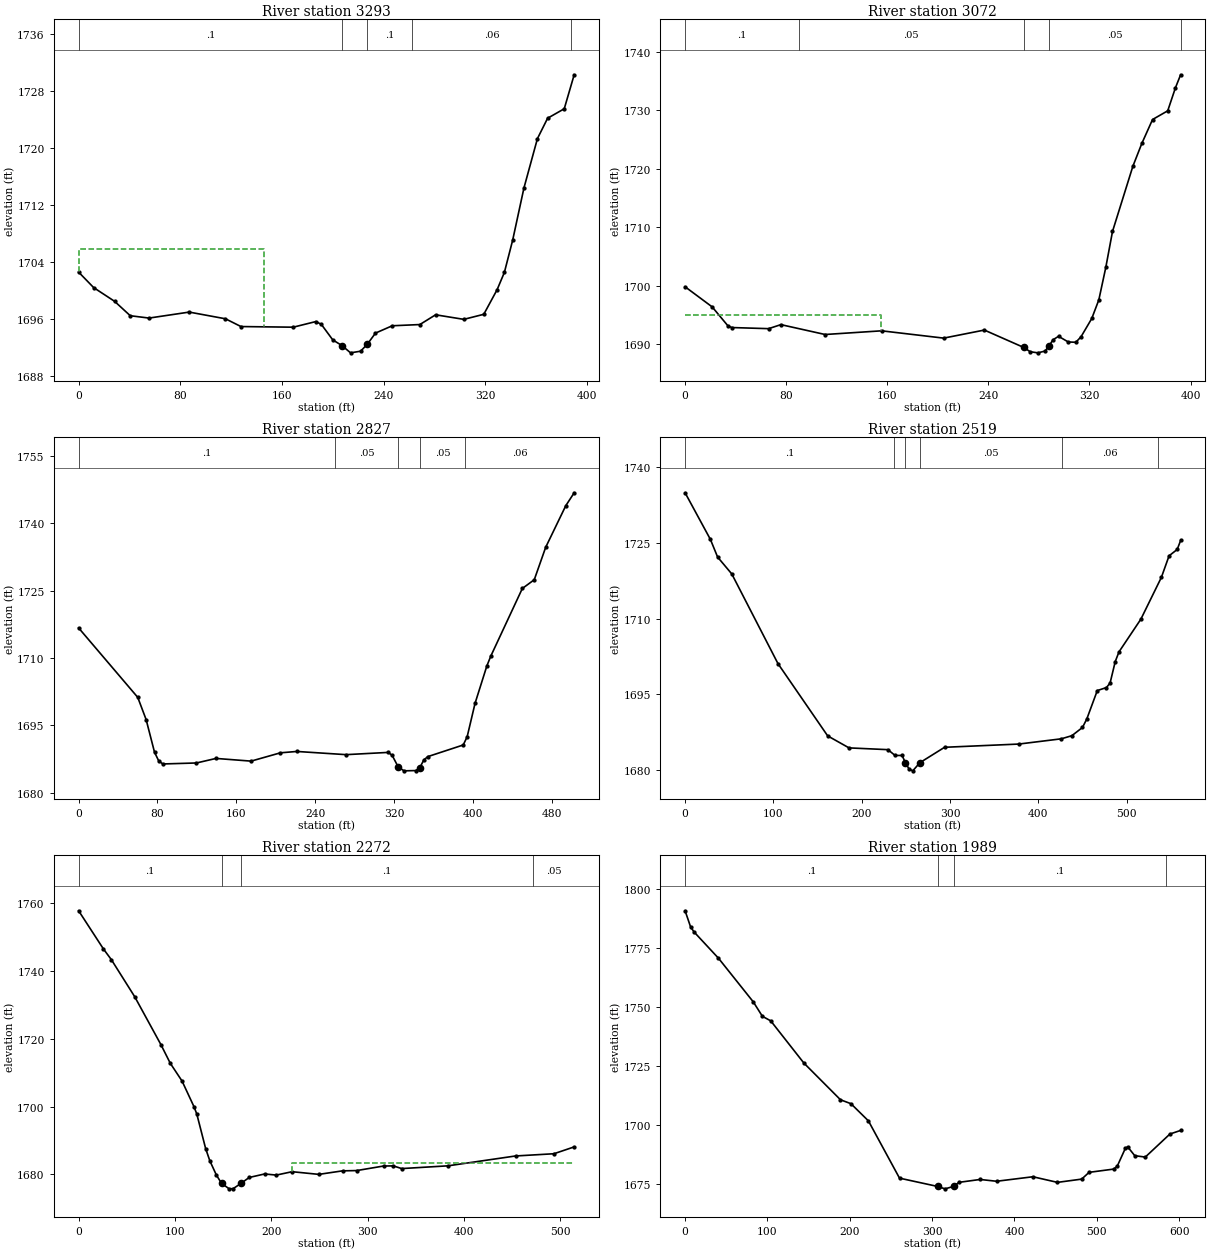
Type RM Length L Ch R = 1 ,3293    ,217.6,220.5,223
XS GIS Cut Line= 4
2200361.30783183680106.2526693882200455.30524209679927.001794007
2200515.41986493679828.6324111752200570.06952206679781.633706045
#Sta/Elev= 30
       0 1702.62    11.8 1700.45    28.3 1698.52    40.6  1696.5    55.4 1696.17
      87 1697.01   115.5 1696.07   127.7 1694.98   168.8 1694.89   186.6 1695.68
   190.9 1695.29   199.9 1693.11   207.3 1692.29   213.9 1691.29   221.8 1691.52
   227.1  1692.5   233.5 1694.06   246.7 1695.09   268.4 1695.26   280.8 1696.63
     303 1695.99   318.7  1696.7   329.2 1700.16   334.9 1702.58   341.4 1707.09
   350.3 1714.44   360.9 1721.36   368.9 1724.22     382 1725.55   389.8 1730.32
#Mann= 5 ,-1,0
       0      .1       0   207.3    .045       0   227.1      .1       0
   262.4     .06       0  387.69      .1       0
#XS Ineff= 2 , 0
          145.61 1705.82
Permanent Ineff=
       T       F
Bank Sta=207.3,227.1
XS Rating Curve= 0 ,0
Exp/Cntr(USF)=0,0
Exp/Cntr=0.3,0.1

Type RM Length L Ch R = 1 ,3072    ,254.5,245.5,233
XS GIS Cut Line= 4
2200509.51770196680252.2765532362200589.19690206680092.918153049
 2200705.2727738679962.0868738832200730.84881333679932.576059034
#Sta/Elev= 30
       0 1699.81    21.4 1696.37    34.1 1693.07    37.1 1692.83    66.1 1692.64
    75.8 1693.33   110.8 1691.64   155.5 1692.27   204.6 1691.02   236.8  1692.4
   267.9 1689.43   273.1 1688.69   279.1  1688.5   284.8  1688.8   287.8 1689.62
   291.1 1690.73   295.5 1691.33   303.2 1690.36   309.2 1690.31   313.3 1691.25
   321.8 1694.38   327.4 1697.58   332.9 1703.13   338.2 1709.28   354.3 1720.43
   361.4 1724.35   369.9 1728.45   381.9 1729.94     388 1733.88   392.1 1736.11
#Mann= 5 ,-1,0
       0      .1       0      90     .05       0   267.9    .045       0
   287.8     .05       0  392.12     .06       0
#XS Ineff= 2 , 0
           154.9  1694.9
Permanent Ineff=
       F       F
Bank Sta=267.9,287.8
XS Rating Curve= 0 ,0
Exp/Cntr(USF)=0,0
Exp/Cntr=0.3,0.1

Type RM Length L Ch R = 1 ,2827    ,304.5,308.1,308.1
XS GIS Cut Line= 3
2200736.12321742 680445.46301622 2200836.9214739680171.000293752
2200845.70739957679960.662834258
#Sta/Elev= 30
       0 1716.68      60 1701.24    68.5  1696.3      77 1689.05    81.3  1687.1
    85.5 1686.43   119.6 1686.65   139.4 1687.66     175 1687.06   204.8 1688.91
   221.5 1689.21   271.4  1688.5   314.2    1689   318.2 1688.34   324.3 1685.77
   330.2  1684.9   342.3 1684.96   346.3 1685.64   350.3 1687.31   354.3 1688.06
   390.3 1690.65   394.3 1692.48   402.3 1699.91   414.3 1708.24   418.3 1710.42
   450.3 1725.46   462.4  1727.4     474 1734.62   494.4 1743.87   502.9 1746.74
#Mann= 5 ,-1,0
       0      .1       0     260     .05       0   324.3    .045       0
   346.3     .05       0  392.39     .06       0
Bank Sta=324.3,346.3
XS Rating Curve= 0 ,0
Exp/Cntr(USF)=0,0
Exp/Cntr=0.3,0.1

Type RM Length L Ch R = 1 ,2519    ,243.9,246.5,246.5
XS GIS Cut Line= 4
2201055.41379132680501.723382113 2201032.7622261680296.458935168
2201045.11187413680047.3377466632200989.44499851679957.882722481
#Sta/Elev= 30
       0 1734.95    28.7 1725.69    36.8 1722.21    52.9 1718.85   105.2 1701.07
   161.5 1686.74   185.7 1684.36   229.8 1684.01   237.8 1682.86   245.8 1682.86
  249.56 1681.41   253.8 1680.14   257.9 1679.81   265.9 1681.42   293.9 1684.48
     378 1685.12   426.1 1686.16   438.1 1686.78   450.1 1688.41     455 1690.09
   466.9 1695.73   477.3 1696.33   481.4 1697.23   487.2 1701.47   491.5 1703.41
   516.3  1709.9   539.5 1718.18   548.2 1722.45   557.4 1723.71   561.3 1725.49
#Mann= 6 ,-1,0
       0      .1       0  236.51     .05       0  249.56    .045       0
   265.9     .05       0  426.51     .06       0  535.94      .1       0
Bank Sta=249.56,265.9
XS Rating Curve= 0 ,0
Exp/Cntr(USF)=0,0
Exp/Cntr=0.3,0.1

Type RM Length L Ch R = 1 ,2272    ,280.1,283.6,284.3
XS GIS Cut Line= 3
2201217.07148194680510.5132206372201260.55131888680293.114035901
2201407.48318167680039.731537829
#Sta/Elev= 30
       0 1757.83    25.8 1746.54      34  1743.4    58.2 1732.48    85.4 1718.35
    95.2 1712.81   107.4 1707.57   119.7 1700.06   122.7 1697.86   131.9 1687.64
   136.3    1684   143.1  1679.8  148.42 1677.38   156.4 1675.76   160.5 1675.82
   168.6 1677.37   177.1 1679.11   193.1 1680.15   205.3 1679.82   221.7 1680.82
   249.4 1680.03   274.1 1681.07   288.7 1681.15   316.6 1682.49   326.7 1682.54
   335.5 1681.74   383.5 1682.55   453.7 1685.46   493.6 1686.12   514.6 1688.14
#Mann= 4 ,-1,0
       0      .1       0  148.42    .045       0   168.6      .1       0
   471.7     .05       0
#XS Ineff= 2 , 0
                          222.01         1683.25
Permanent Ineff=
       F       F
Bank Sta=148.42,168.6
XS Rating Curve= 0 ,0
Exp/Cntr(USF)=0,0
Exp/Cntr=0.3,0.1

Type RM Length L Ch R = 1 ,1989    ,407.1,422.3,430.3
XS GIS Cut Line= 3
2201414.83803906680719.3944074682201521.45526375680412.869886461
2201618.07712364 680152.99040126
#Sta/Elev= 30
       0 1790.81     6.6 1784.05    10.8 1781.87    40.5 1770.72    82.8 1752.21
    93.9 1746.09     104 1744.17   144.2 1726.31   188.7 1710.73   201.4 1709.07
   222.6  1701.8   260.4 1677.52   306.6 1674.01   315.7 1672.99  325.98 1674.01
   332.7 1675.75   358.3 1676.96   378.3  1676.2   422.4 1678.11   452.2 1675.73
   481.6 1677.11   490.6 1679.98   520.5 1681.36   524.8 1682.58   534.8 1690.27
   537.6 1690.74   546.1 1687.03   558.9 1686.45   588.8 1696.22   601.8 1697.74
#Mann= 4 ,-1,0
       0      .1       0   306.6    .045       0  325.98      .1       0
  584.54     .06       0
Bank Sta=306.6,325.98
XS Rating Curve= 0 ,0
Exp/Cntr(USF)=0,0
Exp/Cntr=0.3,0.1

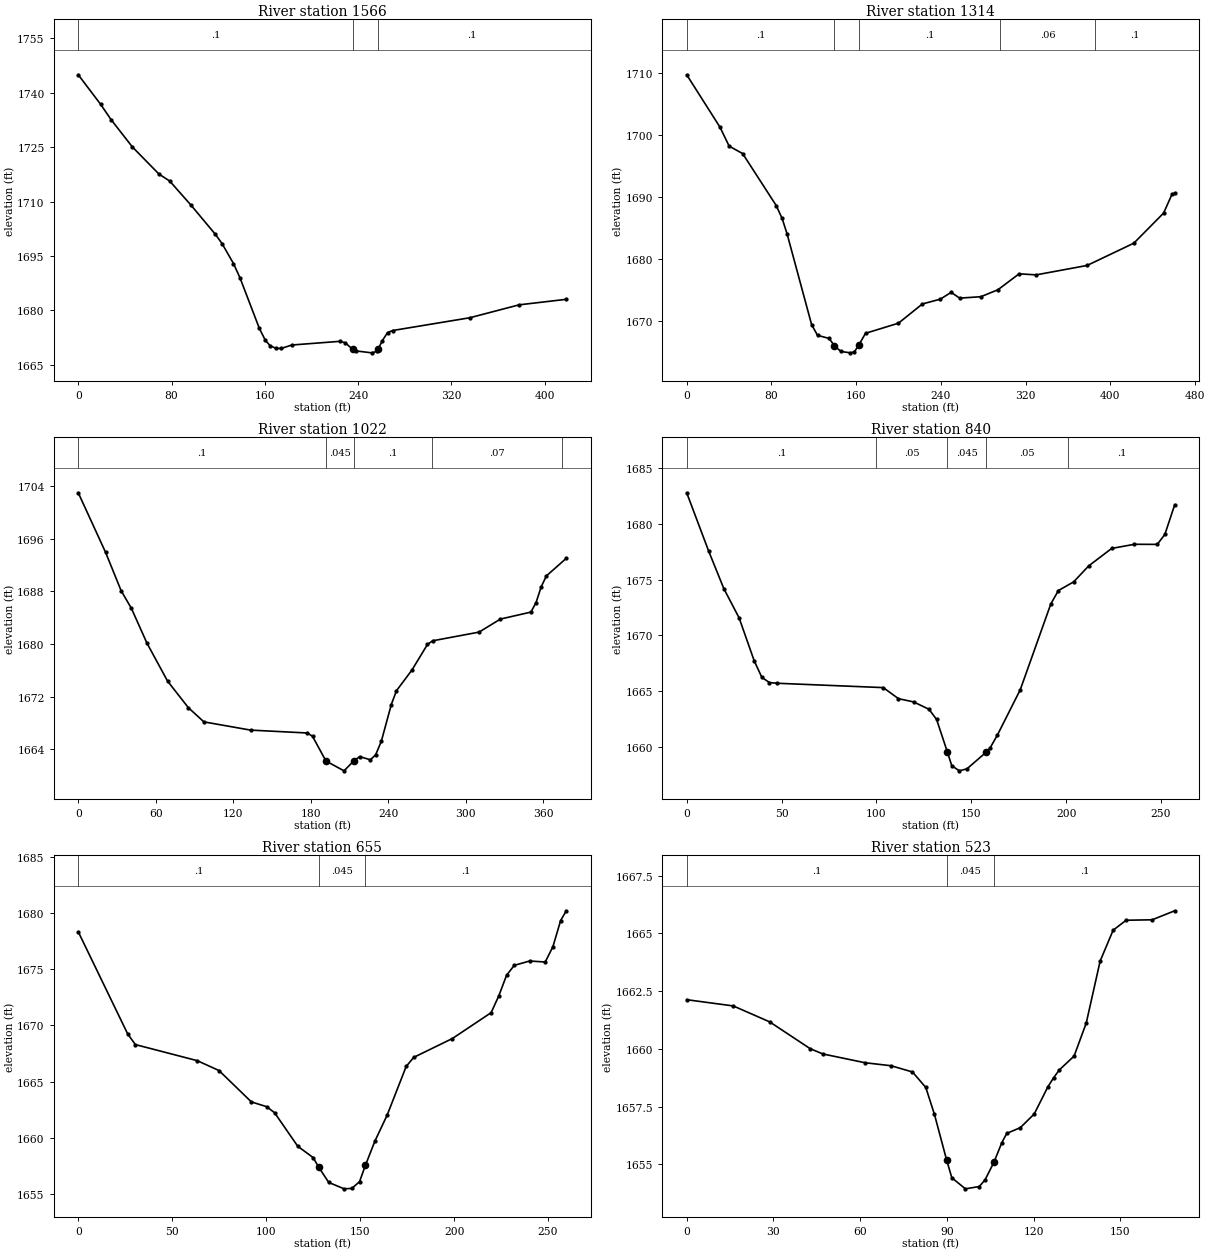
Type RM Length L Ch R = 1 ,1566    ,255.5,252.6,246.9
XS GIS Cut Line= 3
2201591.42281746 680787.696067042201822.98210235680661.088112711
2201961.43641498680592.416254442
#Sta/Elev= 30
       0 1744.96    19.1 1736.85    28.2 1732.57    46.4 1725.06    69.2 1717.58
    78.4 1715.66    96.6 1709.04   117.4 1701.03   123.3 1698.42   133.1 1692.91
   138.7 1688.96   155.3 1675.02   160.4 1671.75   164.5 1670.26   169.5 1669.52
   174.1  1669.5   183.2 1670.44   224.2 1671.45   228.8 1671.09   235.2 1669.28
   238.2 1668.81   251.6 1668.28   255.9 1668.66   257.1 1669.28   260.7  1671.6
   265.2 1673.86   269.7 1674.44   335.7 1677.95   378.1 1681.52   418.5 1683.04
#Mann= 3 ,-1,0
       0      .1       0   235.2    .045       0   257.1      .1       0
Bank Sta=235.2,257.1
XS Rating Curve= 0 ,0
Exp/Cntr(USF)=0,0
Exp/Cntr=0.3,0.1

Type RM Length L Ch R = 1 ,1314    ,279.6,292.1,298.6
XS GIS Cut Line= 3
2201787.28999691680974.962632959  2201964.354886680804.455702718
2202178.58154195 680788.06080558
#Sta/Elev= 30
       0 1709.67    31.4 1701.23    40.1 1698.16    52.8 1696.97    84.5 1688.59
    90.1  1686.5    94.8    1684   117.9  1669.4   123.5 1667.66   134.5 1667.16
  139.45 1665.97   145.6 1665.06   154.6 1664.84   158.3    1665   162.3 1666.03
   168.8 1667.99   199.9 1669.62   222.5 1672.72   239.5  1673.5   249.6 1674.59
   257.7 1673.66   277.7 1673.89   293.8 1675.01   313.8 1677.58   329.9 1677.41
     378 1678.93   422.1 1682.52   450.2 1687.37   458.3 1690.47   460.7 1690.56
#Mann= 5 ,-1,0
       0      .1       0  139.45    .045       0   162.3      .1       0
  295.81     .06       0  385.81      .1       0
Bank Sta=139.45,162.3
XS Rating Curve= 0 ,0
Exp/Cntr(USF)=0,0
Exp/Cntr=0.3,0.1

Type RM Length L Ch R = 1 ,1022    ,177.6,181.8,186.3
XS GIS Cut Line= 4
2201831.05956178681128.928851399   2202017.50889681118.172159387
2202064.12122206681108.8496929762202207.54378222681102.395677768
#Sta/Elev= 30
       0 1702.99    21.2 1693.92    33.2 1688.11    41.2 1685.41    53.2 1680.14
    69.2 1674.36    85.3 1670.33    97.3 1668.18   133.4 1666.93   177.4 1666.49
   181.4 1665.99   191.8 1662.23   205.8 1660.74   213.51662.273     218  1662.9
   226.2 1662.42   230.3 1663.18   234.7 1665.24   242.4 1670.81   246.4 1672.91
   258.4 1676.06   270.4 1679.94   274.4  1680.5   310.4 1681.82   326.9  1683.8
   350.5 1684.86   354.5 1686.31   358.5 1688.71   362.5 1690.36   377.9 1693.03
#Mann= 5 ,-1,0
       0      .1       0   191.8    .045       0   213.5      .1       0
  274.29     .07       0  374.29     .06       0
Bank Sta=191.8,213.5
XS Rating Curve= 0 ,0
Exp/Cntr(USF)=0,0
Exp/Cntr=0.3,0.1

Type RM Length L Ch R = 1 ,840     ,188.9,184.5,178.2
XS GIS Cut Line= 4
2201912.60421276681288.2674537352202027.03390239681291.171760579
2202093.25209841681296.9803742662202169.34493771681291.752621947
#Sta/Elev= 30
       0 1682.77    11.6 1677.54    19.6 1674.18    27.6 1671.58    35.6 1667.72
    39.6 1666.25    43.6 1665.78    47.6 1665.72   103.6 1665.33   111.6 1664.34
   119.6 1664.05   127.7 1663.39   131.7 1662.48   137.4 1659.56   139.7 1658.34
   143.7 1657.88   147.7 1658.06   157.7 1659.53   159.8  1659.9   163.8  1661.1
   175.8 1665.14   191.9 1672.82   195.9 1674.02   203.9 1674.79   211.9 1676.23
     224 1677.79     236 1678.16     248 1678.15     252 1679.04   257.2  1681.7
#Mann= 5 ,-1,0
       0      .1       0     100     .05       0   137.4    .045       0
   157.7     .05       0  200.94      .1       0
Bank Sta=137.4,157.7
XS Rating Curve= 0 ,0
Exp/Cntr(USF)=0,0
Exp/Cntr=0.3,0.1

Type RM Length L Ch R = 1 ,655     ,136.4,132.3,127.3
XS GIS Cut Line= 2
2201934.64444188681506.0380304492202187.10697259  681445.0564264
#Sta/Elev= 30
       0 1678.34    26.3 1669.25    30.4  1668.3    63.3 1666.87    74.9 1665.99
    92.1  1663.2   100.3 1662.77   104.5 1662.23   116.8 1659.25     125 1658.24
   127.9  1657.4   133.3 1656.03   141.5 1655.46   145.6  1655.5   149.7  1656.1
   152.8 1657.55   157.9 1659.72   164.4 1662.03   174.5 1666.35   178.5 1667.16
   199.1 1668.84   219.7 1671.14   223.8 1672.64   227.9 1674.46     232 1675.35
   240.2 1675.74   248.5 1675.65   252.6 1677.02   256.7 1679.34   259.7 1680.21
#Mann= 3 ,-1,0
       0      .1       0   127.9    .045       0   152.8      .1       0
Bank Sta=127.9,152.8
XS Rating Curve= 0 ,0
Exp/Cntr(USF)=0,0
Exp/Cntr=0.3,0.1

Type RM Length L Ch R = 1 ,523     ,88.2,81.1,73.6
XS GIS Cut Line= 4
2202025.65815798681640.9297488332202103.99602647 681603.66633031
2202137.87186149681582.0704854842202175.13528002681563.015328284
#Sta/Elev= 30
       0 1662.13    16.1 1661.86    28.7 1661.17    42.7 1660.01    47.1 1659.78
    61.7  1659.4    70.7 1659.27    78.1    1659    82.7 1658.33    85.7 1657.16
    89.91655.191    91.7 1654.42    96.4 1653.94   101.2 1654.04   103.2 1654.33
   106.3  1655.1     109 1655.94   110.7 1656.34   115.4 1656.59   120.2 1657.18
   124.9 1658.35   126.9 1658.75   128.9 1659.09     134 1659.69   138.2 1661.12
     143  1663.8   147.5 1665.14     152 1665.57     161 1665.59   168.8 1665.98
#Mann= 3 ,-1,0
       0      .1       0    89.9    .045       0   106.3      .1       0
Bank Sta=89.9,106.3
XS Rating Curve= 0 ,0
Exp/Cntr(USF)=0,0
Exp/Cntr=0.3,0.1

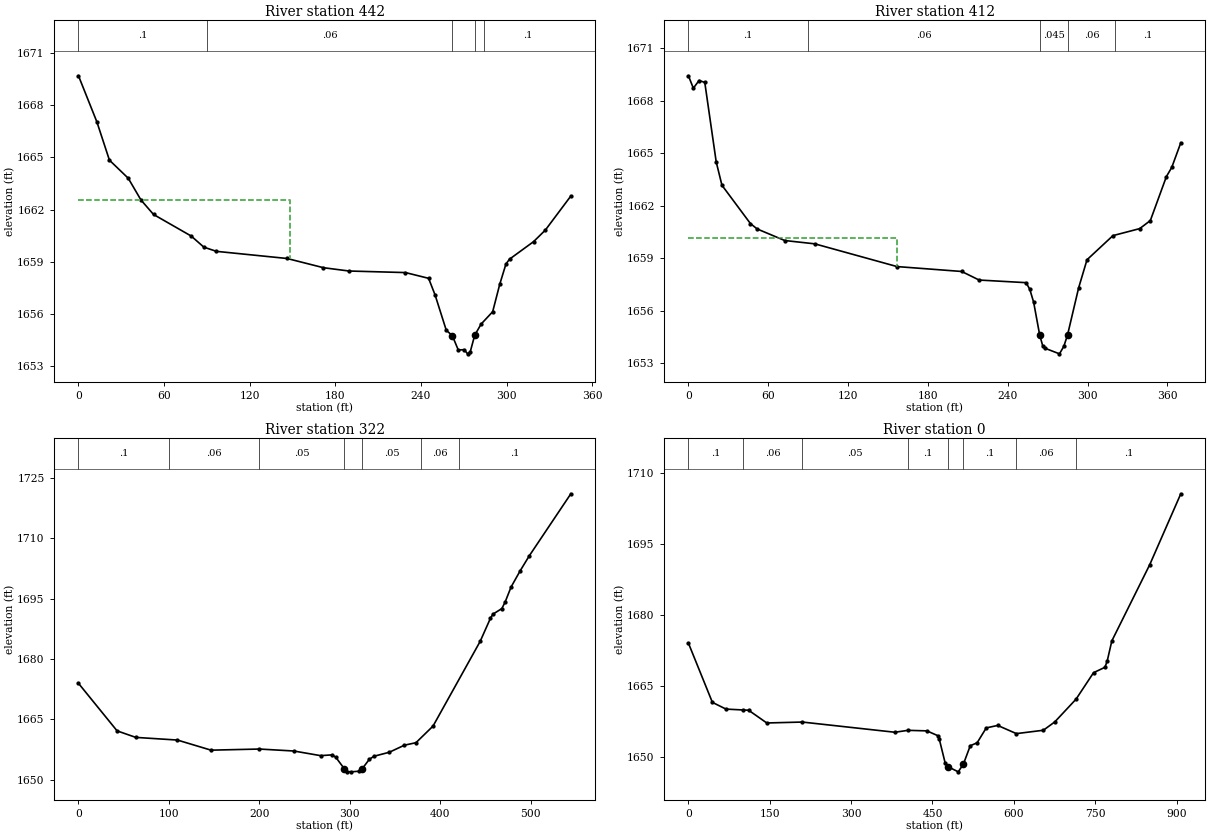
Type RM Length L Ch R = 1 ,442     ,27,29.8,31.5
XS GIS Cut Line= 6
2201928.49293306681704.7100907572202020.30708813681747.389091642
2202099.29642455681724.4394871412202145.70227289681686.165708361
2202165.04495647681650.6169925982202178.18804857 681591.74884207
#Sta/Elev= 30
       0 1669.69    12.9 1667.04    21.7 1664.84    34.9  1663.8    43.8 1662.55
    52.6 1661.72      79 1660.48    87.9 1659.84    96.7  1659.6   146.2 1659.19
   171.7 1658.66   189.6 1658.47   229.2 1658.38   245.4 1658.05     250 1657.08
   257.8 1655.06     262 1654.76   266.2 1653.93   270.4 1653.95   272.7 1653.71
   274.6 1653.83   277.71654.776   282.2 1655.42   290.3 1656.13   295.3 1657.72
   299.6 1658.87   302.1 1659.15     319 1660.16   327.2 1660.82   345.1 1662.78
#Mann= 5 ,-1,0
       0      .1       0      90     .06       0     262    .045       0
   277.7     .06       0   284.3      .1       0
#XS Ineff= 2 , 0
          147.98 1662.55
Permanent Ineff=
       F       F
Bank Sta=262,277.7
XS Rating Curve= 0 ,0
Exp/Cntr(USF)=0,0
Exp/Cntr=0.3,0.1

Type RM Length L Ch R = 1 ,412     ,82.4,90.3,99.2
XS GIS Cut Line= 6
2201928.75231879681725.5587217432202026.71162892681763.934155351
2202109.43694747681743.1193977812202167.65883263681696.098437766
2202188.04706667681667.3458000162202193.79759422681598.339469417
#Sta/Elev= 30
       0 1669.43     3.7 1668.72       8 1669.16    12.3 1669.05    20.9  1664.5
    25.2 1663.17    46.6 1660.98    51.7 1660.67    72.4 1660.01      95 1659.82
   156.8 1658.52   205.4 1658.24   218.5 1657.75   253.8  1657.6   256.6 1657.22
   259.5 1656.48     264 1654.62   266.3 1653.99     268 1653.85   278.9 1653.53
   282.2 1653.96     285 1654.62   293.3  1657.3   299.6 1658.91   319.1 1660.29
   339.2 1660.69   347.2 1661.15   359.3 1663.67   363.3 1664.19   370.1  1665.6
#Mann= 5 ,-1,0
       0      .1       0      90     .06       0     264    .045       0
     285     .06       0  320.88      .1       0
#XS Ineff= 2 , 0
          156.83 1660.18
Permanent Ineff=
       F       F
Bank Sta=264,285
XS Rating Curve= 0 ,0
Exp/Cntr(USF)=0,0
Exp/Cntr=0.3,0.1

Type RM Length L Ch R = 1 ,322     ,286,321.9,345.7
XS GIS Cut Line= 4
2201911.13677183681735.1213734822202131.49974774681797.613960777
2202274.89672324681749.5741470742202404.27556351681648.450428239
#Sta/Elev= 30
       0 1673.95    42.7 1662.15    63.4 1660.53   109.4 1659.87   146.6 1657.36
   200.1 1657.64   238.2 1657.15   267.7    1656   280.4 1656.19   284.6 1655.59
  293.89 1652.77   297.3 1652.06   301.5 1651.98   309.9 1652.13   313.91652.785
   321.6 1655.08   326.8 1655.85   343.7 1656.84   360.5  1658.6   373.2 1659.21
   392.1 1663.34   444.2 1684.36   455.6 1690.11   458.4 1691.13   468.2 1692.51
   471.9 1694.17   478.4 1697.86   488.5  1701.9   498.7 1705.66   544.5    1721
#Mann= 7 ,-1,0
       0      .1       0     100     .06       0     200     .05       0
  293.89    .045       0   313.9     .05       0  379.05     .06       0
  420.28      .1       0
Bank Sta=293.89,313.9
XS Rating Curve= 0 ,0
Exp/Cntr(USF)=0,0
Exp/Cntr=0.3,0.1

Type RM Length L Ch R = 1 ,0       ,,,
XS GIS Cut Line= 4
2201909.85943627681739.8363117612202153.76258522681813.333500098
2202321.70641365682326.004134256 2202298.7246266682437.377409953
#Sta/Elev= 30
       0 1674.07    44.2 1661.56    69.3 1660.14     1001659.961     111  1659.9
   144.5 1657.21     2101657.404   380.8 1655.25  404.741655.655   439.8 1655.54
   459.4 1654.55   462.6 1653.79   473.4 1648.76   478.5 1647.99   497.5 1646.89
     507 1648.51   519.7  1652.4   532.4 1653.03   549.2 1656.17   570.3 1656.69
  604.741654.962   654.4 1655.67   675.5 1657.43  714.741662.237     747 1667.83
   768.1 1668.97   772.3 1670.33   780.7 1674.53   850.6 1690.63   907.9 1705.61
#Mann= 8 ,-1,0
       0      .1       0     100     .06       0     210     .05       0
  404.74      .1       0   478.5    .045       0     507      .1       0
  604.74     .06       0  714.74      .1       0
Bank Sta=478.5,507
XS Rating Curve= 0 ,0
Exp/Cntr=0.3,0.1
LCMann Table=0

Chan Stop Cuts=-1
Use User Specified Reach Order=0
Composite Channel Slope=5